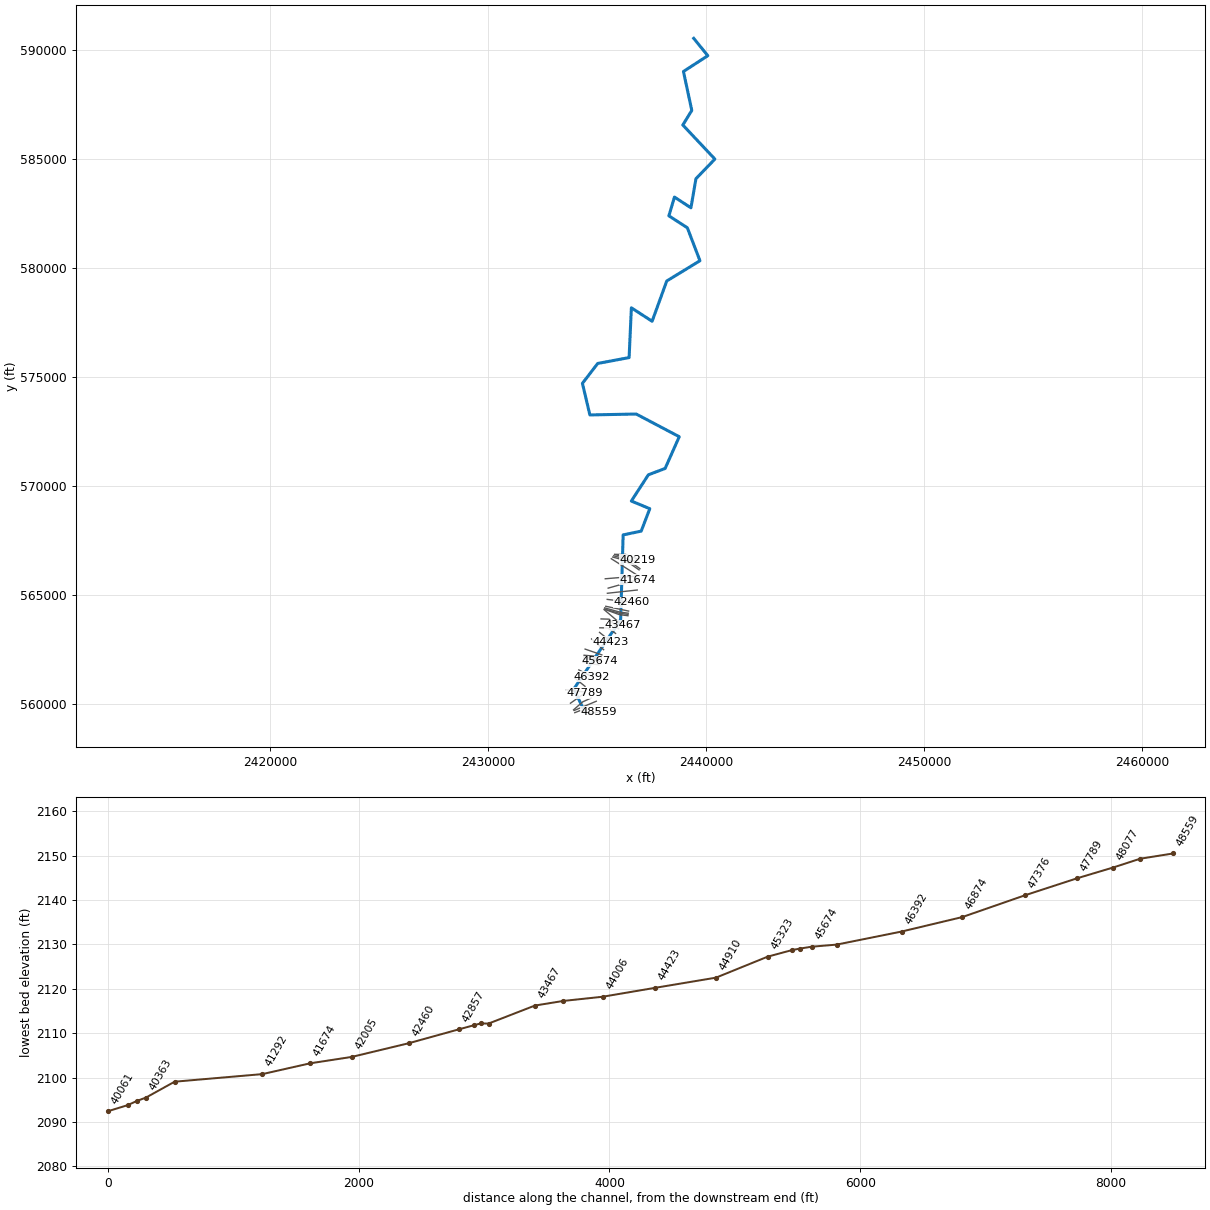
--- THORNCK.prj (project) ---

Proj Title=THORNCK
Current Plan=p01
Default Exp/Contr=0,0
English Units
Geom File=g01
Flow File=f01
Plan File=p01
Background Map Layer=THORNCK_River
BEGIN DESCRIPTION:
Stream Name: Thorn Creek
Flood Zone: Zone A
Pendleton County, WV
WVDHSEM Flood Warning & Analysis Mapping
HEC-RAS Version: 5.0.7
Hydrology Method:
Regression
Model Notes:
Upstream WSEL used as KWSEL for both Blackthorn and Whitethorn Creeks (coincident peaks).
END DESCRIPTION:
DSS Export Rating Curves= 0
DSS Export Rating Curve Sorted= 0
DSS Export Volume Flow Curves= 0
DXF OffsetX= 0
DXF OffsetY= 0
DXF ScaleX= 0
DXF ScaleY= 0

--- THORNCK.p01 (plan) ---

Plan Title=Floodplain
Program Version=4.00
Geom File=g01
Flow File=f01
K Sum by GR=0
Std Step Tol=0.01
Critical Tol=0.01
Num of Std Step Trials=20
Max Error Tol=0.3
Flow Tol Ratio=0.001
Split Flow NTrial=30
Split Flow Tol=0.02
Split Flow Ratio=0.02
Log Output Level=0
Friction Slope Method=1
Unsteady Friction Slope Method=2
Unsteady Bridges Friction Slope Method=1
Global Log Level=0
CheckData=False
Run HTab=0
Run UNet=0
Run PostProcess=0
UNET Theta=0
UNET Theta Warmup=0
UNET ZTol=0
UNET ZSATol=0
UNET MxIter=0
UNET MaxInSteps=0
UNET DtIC=0
UNET DtMin=0
UNET MaxCRTS=0
UNET WFStab=0
UNET SFStab=0
UNET WFX=0
UNET SFX=0
UNET DSS MLevel=0
UNET DZMax Abort=0
UNET Convert EG Bridges=0
UNET Use Existing IB Tables=0
UNET Froude Limit=0
UNET Froude Power=0
Write IC File=0
Echo Input=False
Echo Output=False
Write Detailed=0

--- THORNCK.f01 (steady flow) ---

Flow Title=Flows
Program Version=5.07
Number of Profiles= 6
Profile Names=P100yr,P10yr,P25yr,P50yr,P500yr,P101yr
River Rch & RM=THORNCK,Main            ,48559
    6178    2788    4006    5058    9285    7519
River Rch & RM=THORNCK,Main            ,47789
    6949    3130    4501    5687   10456    8457
River Rch & RM=THORNCK,Main            ,31714
    7963    3579    5152    6514   11999    9691
River Rch & RM=THORNCK,Main            ,5614
    8899    3993    5752    7276   13424   10830
Boundary for River Rch & Prof#=THORNCK,Main            , 1
Up Type= 0
Dn Type= 3
Dn Slope=0.04825
Boundary for River Rch & Prof#=THORNCK,Main            , 2
Up Type= 0
Dn Type= 3
Dn Slope=0.04825
Boundary for River Rch & Prof#=THORNCK,Main            , 3
Up Type= 0
Dn Type= 3
Dn Slope=0.04825
Boundary for River Rch & Prof#=THORNCK,Main            , 4
Up Type= 0
Dn Type= 3
Dn Slope=0.04825
Boundary for River Rch & Prof#=THORNCK,Main            , 5
Up Type= 0
Dn Type= 3
Dn Slope=0.04825
Boundary for River Rch & Prof#=THORNCK,Main            , 6
Up Type= 0
Dn Type= 3
Dn Slope=0.04825
DSS Import GetInterval= 0
DSS Import GetPeak= 0
DSS Import FillOption= 0

--- THORNCK.g01 (geometry) ---

Geom Title=Geometry
Program Version=5.07

River Reach=THORNCK         ,Main
Reach XY= 30
     2434436.132559634.0949999992433930.46900004560675.860555559
2436080.55200002563861.1345555482436195.71000004 567753.46855557
2437024.03300002567927.4205555622437418.43206212568956.307412282
2436572.06600007569308.9605555532437353.37000003570514.016555563
2438120.16100001570803.0725555572438770.43900004572260.996555582
2436794.60781118 573303.039372282434669.14700007573261.394555554
2434327.18467581574711.7749613672435028.75194234575624.873907849
2436469.03700003 575894.527555572436572.90947017578179.365261376
2437525.01300004 577560.826555552438196.09600002579410.797555551
2439719.30888259580341.2722024622439140.81600004581853.281555563
2438294.31300002582401.6755555572438550.02552947583263.288908258
2439305.11376479582770.1784381272439536.30300003584106.792555556
2440405.00300002585007.2925555712438933.38500005 586572.05955556
2439344.72999999587242.034555569     2438961.995589029.060555577
2440080.14200002589754.0355555862439433.45000005590550.939999998

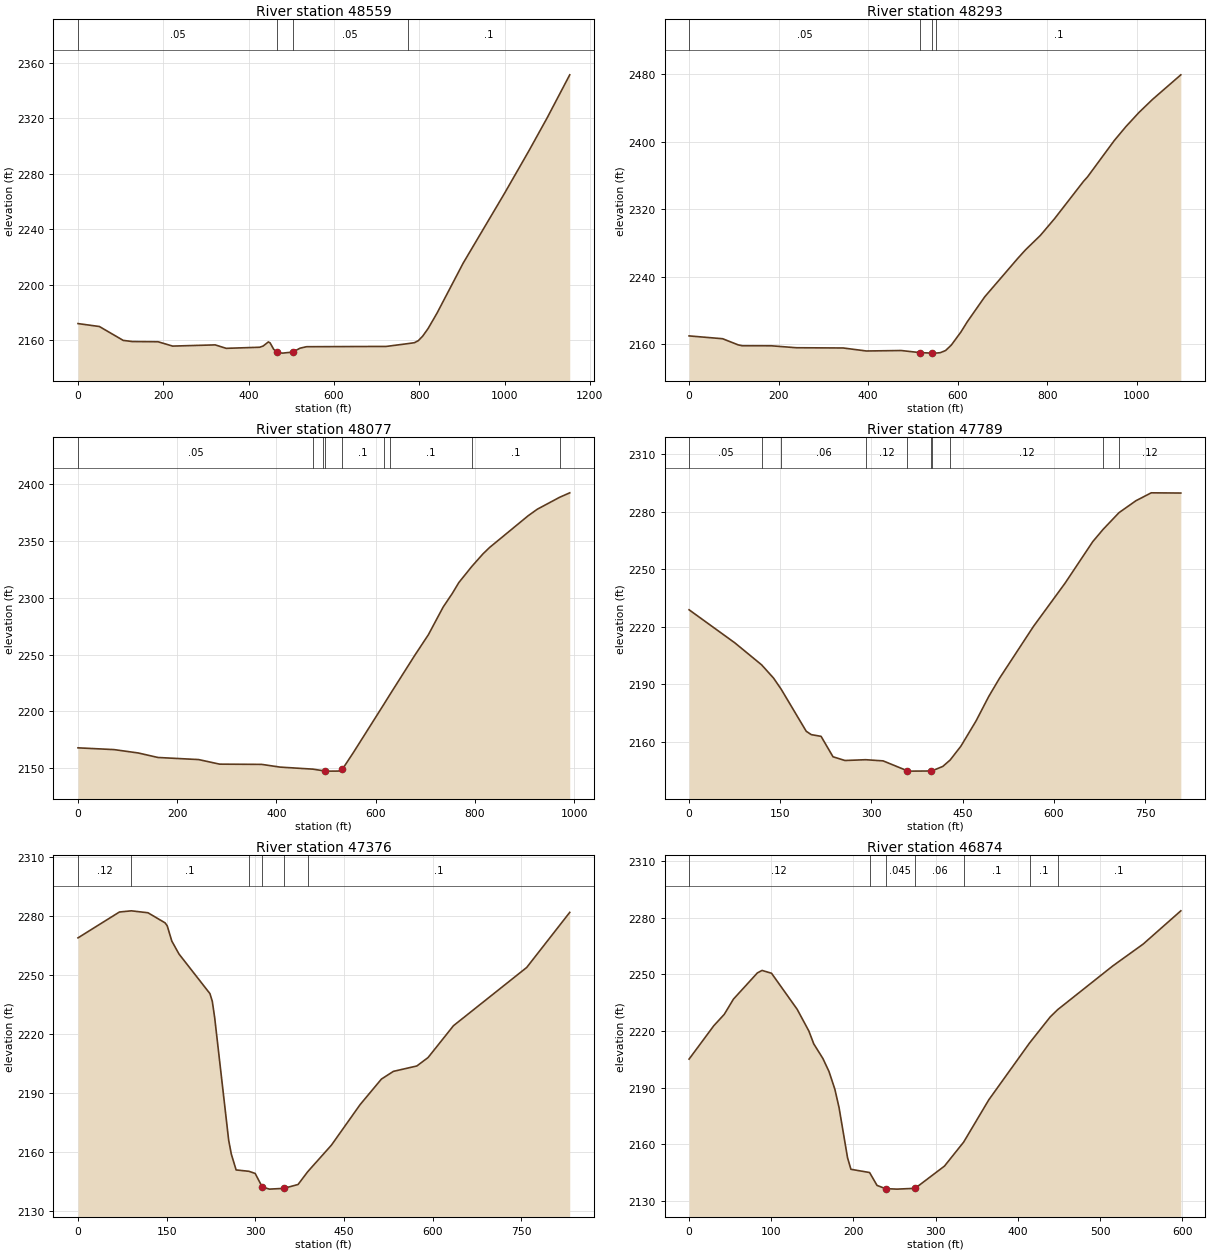
Type RM Length L Ch R = 1 ,48559   ,249.7,265.6,279.6
XS GIS Cut Line= 5
2433976.08830333559591.6046787652434222.04131848559687.914099455
     2434436.132559634.0949999992434730.50560495559560.093132839
2435087.59210983559632.377850413
#Sta/Elev= 30
       0 2171.83    50.1 2169.72     106  2159.7   127.4 2158.86   187.6 2158.71
   221.9 2155.58   321.6 2156.45   347.4 2153.96   425.7 2154.74     434 2155.61
   446.3  2158.6   450.5 2157.83   458.7  2153.3   467.32151.034   479.8  2150.5
   503.32151.267   520.6 2154.07   535.8 2155.13   722.7 2155.34   773.1 2157.35
   788.7 2158.03   797.8  2159.5     808 2162.75     821 2168.39   841.9 2179.52
   902.9 2215.45  1000.1 2266.01    1058 2297.11  1099.9 2320.44  1152.8 2351.48
#Mann= 4 ,-1 , 0
       0     .05       0   467.3    .045       0   503.3     .05       0
   773.1      .1       0
Bank Sta=467.3,503.3
XS Rating Curve= 0 ,0
Exp/Cntr(USF)=0,0
Exp/Cntr=0.3,0.1

Type RM Length L Ch R = 1 ,48293   ,208.7,215.8,219.9
XS GIS Cut Line= 2
2433949.93616929559693.9408865632434963.47832261560116.576224628
#Sta/Elev= 30
       0 2169.73    74.8 2166.39   109.8 2159.06   118.5 2158.07   183.5 2158.01
   239.8 2155.69   344.1  2155.4   395.8 2151.84   473.8 2152.38   515.1 2149.94
   541.5 2149.33   547.5  2149.3  550.86 2149.31     561 2149.85   572.7 2152.35
   585.5 2158.81   606.9 2174.27   621.1  2186.4   660.1 2216.03   733.8  2261.6
   751.1 2271.77   784.3 2288.88   816.1 2308.82   881.1 2353.33   889.8 2358.44
   949.4 2401.48   975.4 2418.01  1004.4 2434.72    1035 2450.39  1098.1 2479.51
#Mann= 4 ,-1 , 0
       0     .05       0   515.1    .045       0   541.5     .05       0
  550.86      .1       0
Bank Sta=515.1,541.5
XS Rating Curve= 0 ,0
Exp/Cntr(USF)=0,0
Exp/Cntr=0.3,0.1

Type RM Length L Ch R = 1 ,48077   ,291.1,288.9,285.8
XS GIS Cut Line= 3
2433919.58816976559722.6622649282434343.45834262560090.381001119
 2434734.4387165 560269.23372534
#Sta/Elev= 30
       0 2167.85    72.8 2166.29   121.4 2163.32   161.2 2159.35   243.2  2157.5
   285.5 2153.47   370.3 2153.26   407.3 2150.87  473.282149.071  494.632147.623
   497.3 2147.51   504.3 2147.32   524.1 2147.35   529.8 2147.75   532.6 2148.82
     555 2163.68  616.432206.219  629.372215.299   678.6 2249.28   706.1  2267.5
     736 2291.98   754.1 2303.74   767.6 2313.55  793.55 2327.66     816 2338.73
   829.5 2344.45   907.1 2372.37   925.6 2378.17  970.662388.715   991.1 2392.65
#Mann= 9 ,-1 , 0
       0     .05       0  473.28      .1       0  494.63      .1       0
   497.3    .045       0   532.6      .1       0  616.43      .1       0
  629.37      .1       0  793.55      .1       0  970.66      .1       0
Bank Sta=497.3,532.6
XS Rating Curve= 0 ,0
Exp/Cntr(USF)=0,0
Exp/Cntr=0.3,0.1

Type RM Length L Ch R = 1 ,47789   ,426,412.7,391.4
XS GIS Cut Line= 2
2433777.75140193560026.570550781 2434439.0974402560492.252080687
#Sta/Elev= 30
       0 2228.89    75.3 2211.66  119.252200.235   138.9 2193.33  151.492187.525
   192.7 2165.63     201 2163.88   217.1 2162.99   236.7 2152.36   256.4 2150.41
  290.412150.823   319.1 2150.22     359 2145.05   363.9 2144.88   397.1 2144.95
  400.142145.111   417.2 2147.31  429.322150.641   447.1 2157.89     472 2171.02
   492.8 2183.71   510.6 2193.24   566.4 2220.22   618.3  2242.7     664 2264.39
  681.032270.786  707.162279.474   734.9 2285.66   760.1 2289.79   808.8 2289.68
#Mann= 10 ,-1 , 0
       0     .05       0  119.25      .1       0  151.49     .06       0
  290.41     .12       0     359    .045       0   397.1     .12       0
  400.14     .05       0  429.32     .12       0  681.03      .1       0
  707.16     .12       0
Bank Sta=359,397.1
XS Rating Curve= 0 ,0
Exp/Cntr(USF)=0,0
Exp/Cntr=0.3,0.1

Type RM Length L Ch R = 1 ,47376   ,510.7,501.4,484.6
XS GIS Cut Line= 2
2433593.82676406560640.9571070432434419.53098936560539.211562694
#Sta/Elev= 30
       0 2268.95      70  2282.1   90.31 2282.71   118.4 2281.72   147.3 2276.59
   150.9 2275.11   158.7 2267.32   170.8 2260.76   223.2 2240.58   227.2 2236.67
   231.2  2228.4   254.9 2165.97   259.4 2158.87   267.5 2150.84  289.092150.155
   299.7 2149.06   311.8 2142.11   323.9 2141.08   348.1 2141.47   372.3 2143.44
  388.482149.905   428.7 2163.46   477.3 2184.11   513.3 2197.08   533.5    2201
   573.2 2203.75   592.2 2208.03   635.2 2224.25   759.1 2253.89   831.9 2281.92
#Mann= 6 ,-1 , 0
       0     .12       0   90.31      .1       0  289.09     .06       0
   311.8    .045       0   348.1     .06       0  388.48      .1       0
Bank Sta=311.8,348.1
XS Rating Curve= 0 ,0
Exp/Cntr(USF)=0,0
Exp/Cntr=0.3,0.1

Type RM Length L Ch R = 1 ,46874   ,478.4,482.6,486.1
XS GIS Cut Line= 2
2433981.24249063561177.0778599592434446.92402053560801.402003901
#Sta/Elev= 30
       0 2205.11      30 2222.77    42.8 2228.84      54 2236.93    83.1 2250.81
    88.8 2252.12   100.3 2250.63   131.5 2231.52   145.7 2220.03   151.7 2213.18
   162.8 2205.43   170.2 2198.56   177.4 2189.08   182.5 2179.33   192.8 2152.78
   196.9 2146.68  219.632144.957   228.7 2138.12     239 2136.42     253 2136.16
     275 2136.58   310.7 2148.37  334.072161.102   364.7 2183.54  414.312213.693
   439.4 2227.48  448.392231.302   515.5 2254.51   552.4 2266.07   598.3 2283.73
#Mann= 7 ,-1 , 0
       0     .12       0  219.63     .06       0     239    .045       0
     275     .06       0  334.07      .1       0  414.31      .1       0
  448.39      .1       0
Bank Sta=239,275
XS Rating Curve= 0 ,0
Exp/Cntr(USF)=0,0
Exp/Cntr=0.3,0.1

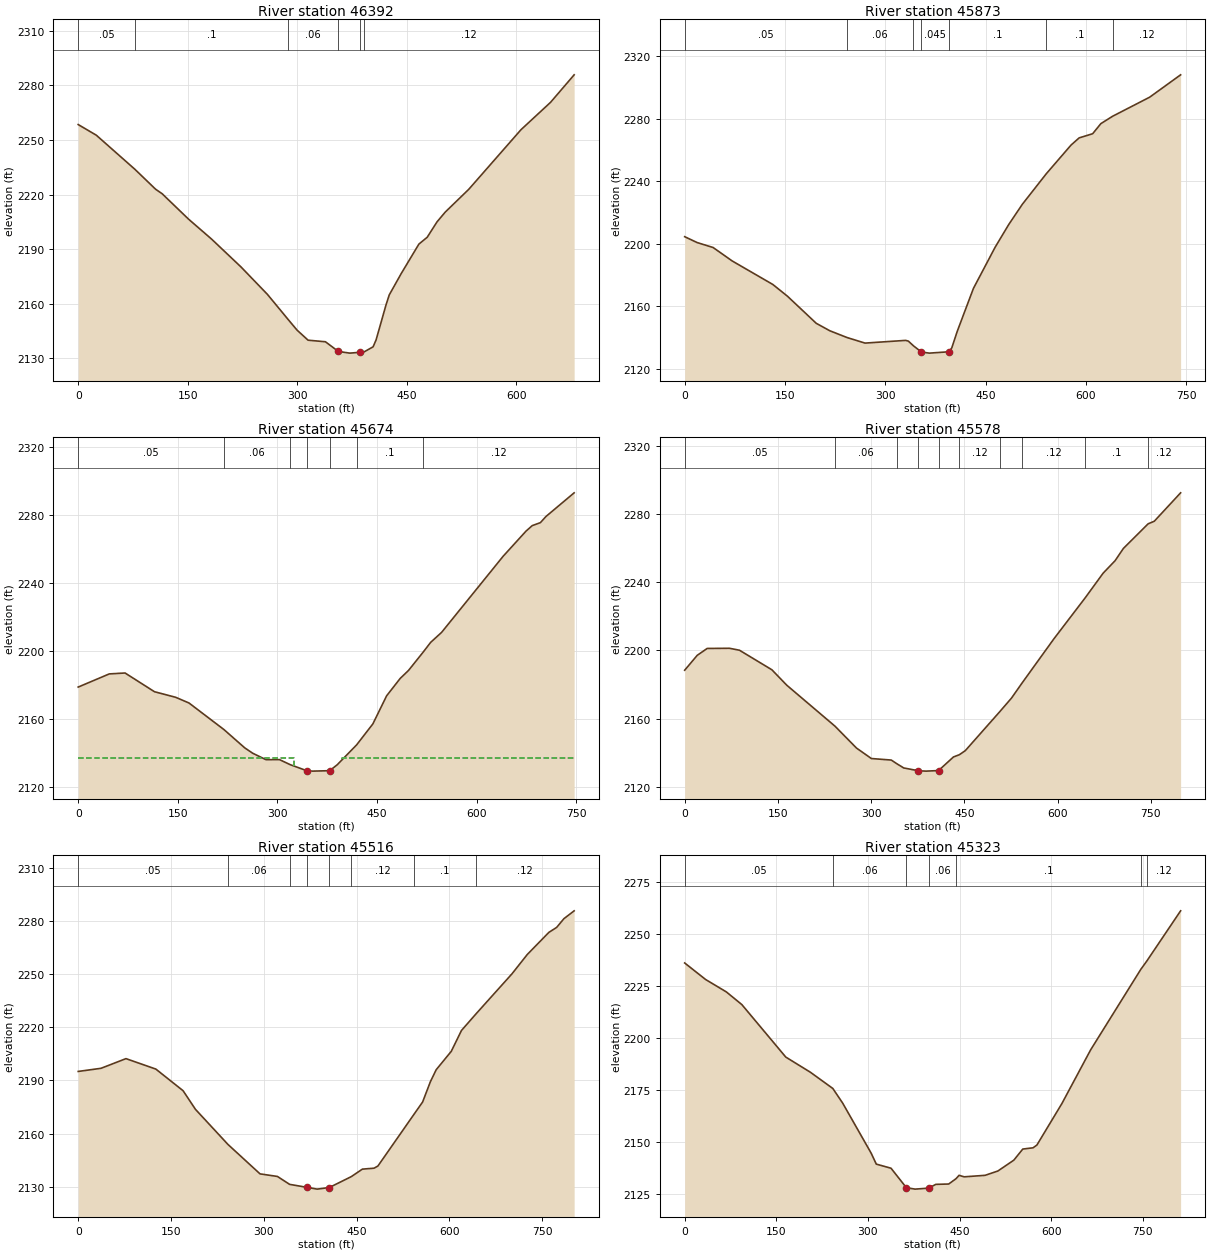
Type RM Length L Ch R = 1 ,46392   ,511.8,519.3,527.2
XS GIS Cut Line= 2
2434161.25383832561556.6670061842434763.90052408561243.603792803
#Sta/Elev= 30
       0 2258.51    24.8 2252.66   77.892233.829   105.9    2223     115 2220.48
     151 2206.57   182.6 2195.58   222.9 2180.27   259.2 2165.15  287.042151.602
   299.7 2145.54   314.8 2140.01   338.5 2139.16   356.3 2133.82   371.9 2132.91
   385.4 2133.35  391.612133.625   403.8 2136.38   407.9 2140.18   421.4 2159.29
   425.9 2164.89   442.3 2176.63   466.5 2192.82   477.9 2196.59   491.3 2205.03
   502.6 2210.42   534.7 2222.89   606.2 2255.64   646.8 2270.73   679.1 2285.84
#Mann= 6 ,-1 , 0
       0     .05       0   77.89      .1       0  287.04     .06       0
   356.3    .045       0   385.4     .06       0  391.61     .12       0
Bank Sta=356.3,385.4
XS Rating Curve= 0 ,0
Exp/Cntr(USF)=0,0
Exp/Cntr=0.3,0.1

Type RM Length L Ch R = 1 ,45873   ,200.6,198.5,196.1
XS GIS Cut Line= 2
2434349.09176635561908.8631212392435080.87702763561787.551126053
#Sta/Elev= 30
       0 2204.47    18.7  2200.7    42.5 2197.55    71.1 2188.93   131.9 2173.88
   153.8 2166.35   196.8 2149.04   217.1 2144.27  242.892139.931   269.8 2136.38
   330.6 2138.12   334.6 2137.63  342.212134.639   354.1 2130.67   365.9 2129.96
   395.4 2130.83   399.5 2133.29   407.6 2143.79   431.9 2171.38   464.4 2197.75
   484.6 2212.18     505 2225.17  540.852244.725   577.9 2263.09     590 2267.68
   610.3 2270.37   622.5 2276.81  640.172281.552   695.5 2293.73   741.8 2308.04
#Mann= 7 ,-1 , 0
       0     .05       0  242.89     .06       0  342.21      .1       0
   354.1    .045       0   395.4      .1       0  540.85      .1       0
  640.17     .12       0
Bank Sta=354.1,395.4
XS Rating Curve= 0 ,0
Exp/Cntr(USF)=0,0
Exp/Cntr=0.3,0.1

Type RM Length L Ch R = 1 ,45674   ,91.2,96,100.4
XS GIS Cut Line= 3
2434400.44165243562068.1593817552434694.30083769562058.800808976
2435132.28204375561942.754506516
#Sta/Elev= 30
       0 2178.92    46.8 2186.65    70.6 2187.19   114.9 2176.18   146.9 2172.89
   166.9 2169.55  219.522153.937   250.9 2143.16   262.9    2140   282.9 2136.22
   303.2 2136.27  319.582133.254   344.4 2129.73   352.9 2129.49   378.8 2129.75
   390.2 2133.24  419.382144.913   443.9 2157.27   464.6 2173.77     485 2183.97
   497.7 2188.74  519.182199.228   530.9 2205.18   547.4 2211.07   640.2 2255.86
   674.7 2270.66   683.9 2273.83   696.3 2275.61   704.6  2279.2   747.1 2293.13
#Mann= 7 ,-1 , 0
       0     .05       0  219.52     .06       0  319.58      .1       0
   344.4    .045       0   378.8      .1       0  419.38      .1       0
  519.18     .12       0
#XS Ineff= 2 , 0
             325    2137     398            2137
Permanent Ineff=
       F       F
Bank Sta=344.4,378.8
XS Rating Curve= 0 ,0
Exp/Cntr(USF)=0,0
Exp/Cntr=0.5,0.3

Type RM Length L Ch R = 1 ,45578   ,62.8,62.2,60.8
XS GIS Cut Line= 3
2434391.08307965 562150.514822212434830.93600027562131.797676652
2435165.97290575562006.392801413
#Sta/Elev= 30
       0  2188.4    20.2 2197.16    36.2  2201.2    72.2  2201.3    88.2 2200.15
   140.3 2188.67   164.3 2179.58  241.812155.512   276.4 2142.65   300.4 2136.47
   332.4 2135.57  341.832133.306   352.5 2130.93     376 2129.29   388.4 2129.06
   408.5 2129.39   432.5 2137.39  441.862138.687   451.5 2141.09  507.062164.047
   525.9 2172.02  543.152181.012     594 2206.81  644.432230.954   673.3 2245.46
   692.5 2252.78   705.9 2260.01  745.722274.489   755.6 2276.01     798 2292.72
#Mann= 10 ,-1 , 0
       0     .05       0  241.81     .06       0  341.83      .1       0
     376    .045       0   408.5      .1       0  441.86     .12       0
  507.06      .1       0  543.15     .12       0  644.43      .1       0
  745.72     .12       0
Bank Sta=376,408.5
XS Rating Curve= 0 ,0
Exp/Cntr(USF)=0,0
Exp/Cntr=0.5,0.3

Type RM Length L Ch R = 1 ,45516   ,199.3,193,187.8
XS GIS Cut Line= 3
2434402.31336699562229.1268335542434849.65314582562189.820827882
2435182.81833676562073.774525422
#Sta/Elev= 30
       0 2195.09    36.9 2196.86    77.2 2202.31   125.5 2196.43   169.6 2184.21
   189.6 2173.71  242.272153.873     294 2137.32   322.1 2135.87  341.852131.407
   370.3  2129.7   386.4 2128.72   405.9 2129.61  441.432135.746   459.5    2140
   478.3 2140.52   484.6 2141.75  542.192170.546   556.9 2177.86   569.4 2189.26
   578.8 2196.04   603.2 2206.42   619.7 2218.19  643.03 2227.48   701.4 2250.15
     726    2261     761 2273.51   773.6 2276.32   785.3 2281.22   801.9 2285.67
#Mann= 8 ,-1 , 0
       0     .05       0  242.27     .06       0  341.85      .1       0
   370.3    .045       0   405.9      .1       0  441.43     .12       0
  542.19      .1       0  643.03     .12       0
Bank Sta=370.3,405.9
XS Rating Curve= 0 ,0
Exp/Cntr(USF)=0,0
Exp/Cntr=0.5,0.3

Type RM Length L Ch R = 1 ,45323   ,422.2,412.4,405.2
XS GIS Cut Line= 2
 2434450.8373107562511.5098069992435217.84218348562245.406075624
#Sta/Elev= 30
       0 2235.91    34.3 2227.96    68.2 2222.01    93.6 2215.91   165.5  2190.7
   205.8 2183.41  242.552175.602   258.7 2168.56   305.2 2144.58   313.7 2139.26
   337.8  2137.3   362.9 2127.96   377.2 2127.25   399.42127.726   411.1 2129.54
   432.2  2129.7   444.22132.255   449.2 2133.88   457.6 2133.16   491.8 2133.88
   512.7 2135.95   538.9 2141.18   553.5  2146.5   570.3  2147.1   576.6 2148.42
   617.5 2168.34   664.6 2194.16  746.682232.816  756.712236.903   811.9 2260.96
#Mann= 7 ,-1 , 0
       0     .05       0  242.55     .06       0   362.9    .045       0
   399.4     .06       0   444.2      .1       0  746.68      .1       0
  756.71     .12       0
Bank Sta=362.9,399.4
XS Rating Curve= 0 ,0
Exp/Cntr(USF)=0,0
Exp/Cntr=0.3,0.1

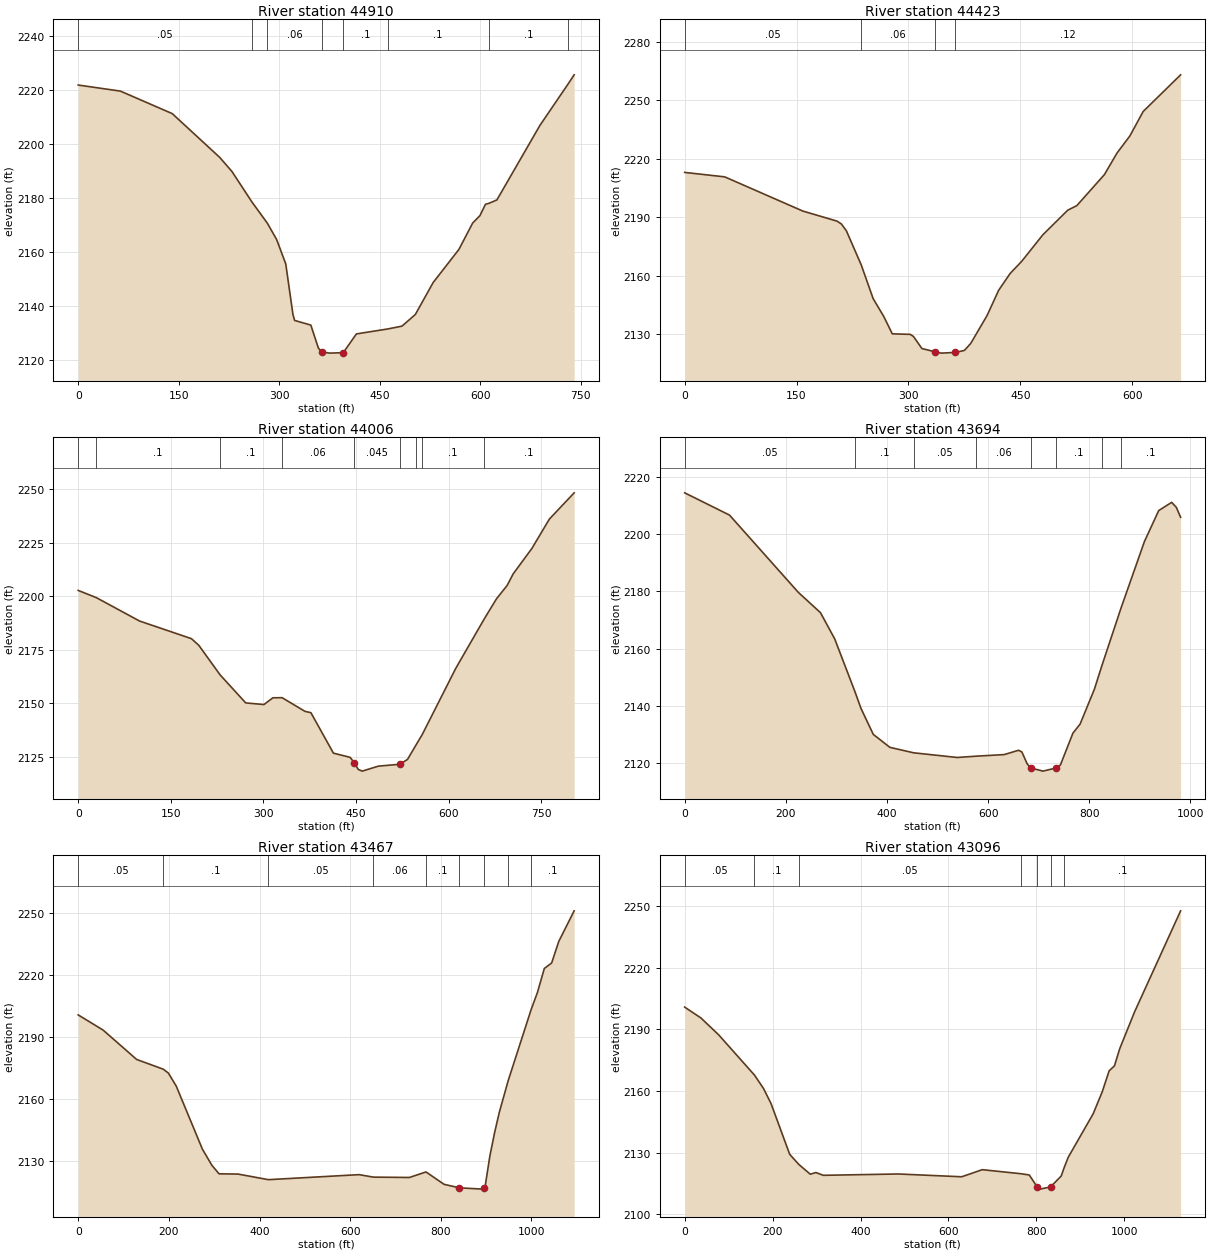
Type RM Length L Ch R = 1 ,44910   ,486.8,487.5,488.1
XS GIS Cut Line= 2
2434748.24736341562977.191336904  2435300.021277562484.116775828
#Sta/Elev= 30
       0 2221.76      63 2219.51   140.3 2211.18   211.1 2194.99   229.3 2189.79
  259.312178.446  282.242170.611   296.1 2164.57   309.7 2155.53   320.4 2136.85
   322.9 2134.62   347.1  2132.9   358.4 2124.37   363.4 2122.96   375.4 2122.52
   395.5  2122.7   415.1 2129.63  461.522131.452   483.1 2132.51     503 2136.81
   529.6 2148.64     568 2160.89   588.6 2170.68   599.4 2173.41   607.7 2177.62
  612.882177.981   624.7 2179.22     689 2206.85  730.742222.062     740 2225.54
#Mann= 8 ,-1 , 0
       0     .05       0  259.31    .055       0  282.24     .06       0
   363.4    .045       0   395.5      .1       0  461.52      .1       0
  612.88      .1       0  730.74     .12       0
Bank Sta=363.4,395.5
XS Rating Curve= 0 ,0
Exp/Cntr(USF)=0,0
Exp/Cntr=0.3,0.1

Type RM Length L Ch R = 1 ,44423   ,416.2,417.1,413.8
XS GIS Cut Line= 2
2435112.18334897563278.5146797842435628.73765105562859.792631886
#Sta/Elev= 30
       0 2213.01    53.7 2210.73   158.3 2193.18   204.4 2187.98   210.1 2186.54
   216.8 2183.03  236.812165.427   252.7 2148.18     267 2138.98   278.3 2130.14
   302.5 2129.85   306.8 2128.74   318.1 2122.56   335.2 2120.96   343.7 2120.22
   362.9 2120.58     375  2121.6   383.5 2125.19   405.4 2139.51   420.9 2152.45
   436.3  2161.1   451.8 2167.34   480.2 2180.98   513.6 2193.62   525.7 2195.94
   562.7 2211.87   579.7 2222.99   596.8  2231.7   614.7  2244.3   664.9 2263.12
#Mann= 4 ,-1 , 0
       0     .05       0  236.81     .06       0   335.2    .045       0
   362.9     .12       0
Bank Sta=335.2,362.9
XS Rating Curve= 0 ,0
Exp/Cntr(USF)=0,0
Exp/Cntr=0.3,0.1

Type RM Length L Ch R = 1 ,44006   ,315.5,312,301.3
XS GIS Cut Line= 3
2435123.92321947563489.8323488172435491.77249519563482.005768482
2435847.88190041563231.555197777
#Sta/Elev= 30
       0  2202.7   29.342199.331    99.3  2188.4   183.3 2180.16   195.3 2177.05
  229.932163.183   271.3 2150.12   300.8 2149.34   315.3  2152.5  330.222152.551
   367.3 2146.17   376.9 2145.54   413.4 2126.62   440.5 2124.66   447.5    2122
   453.6 2119.01   460.1 2118.22   486.2 2120.55     521 2121.43   533.4  2123.7
  547.242130.479  557.152135.266   611.6  2166.3  657.662189.372   677.5 2198.77
   694.8 2205.04   704.5 2210.41     735  2222.4   763.2 2236.06   803.3 2248.33
#Mann= 9 ,-1 , 0
       0     .05       0   29.34      .1       0  229.93      .1       0
  330.22     .06       0   447.5    .045       0     521     .06       0
  547.24      .1       0  557.15      .1       0  657.66      .1       0
Bank Sta=447.5,521
XS Rating Curve= 0 ,0
Exp/Cntr(USF)=0,0
Exp/Cntr=0.3,0.1

Type RM Length L Ch R = 1 ,43694   ,227.8,227.2,235.1
XS GIS Cut Line= 3
2435182.62257198563896.8145262132435554.38513787563885.074655711
2435977.02047593563446.786156977
#Sta/Elev= 30
       0 2214.39    88.6 2206.63   224.8 2179.65   268.6 2172.56   296.7 2163.43
  337.022144.883   348.7 2139.15     373  2130.1   405.8 2125.58  452.762123.675
   538.8 2122.04  576.842122.502   631.9 2123.05   660.4 2124.56   666.9 2123.95
   677.4  2119.8   684.2  2118.4   708.5 2117.28   733.9 2118.35     743  2119.4
   767.9 2130.56     782 2133.69   810.3 2145.87  825.012154.038  862.472173.933
   909.3 2197.43   937.5  2208.2   963.1 2211.07   972.3 2209.33   980.8 2205.87
#Mann= 8 ,-1 , 0
       0     .05       0  337.02      .1       0  452.76     .05       0
  576.84     .06       0   684.2    .045       0   733.9      .1       0
  825.01     .12       0  862.47      .1       0
Bank Sta=684.2,733.9
XS Rating Curve= 0 ,0
Exp/Cntr(USF)=0,0
Exp/Cntr=0.3,0.1

Type RM Length L Ch R = 1 ,43467   ,357.8,370.2,388.3
XS GIS Cut Line= 2
2435326.05866266564318.424212057 2436160.9451138563611.144344002
#Sta/Elev= 30
       0  2200.6    55.1 2193.22   128.9 2179.03   187.72174.307   198.9 2172.44
   216.3 2166.12     274  2135.6     295 2127.76   310.7 2123.65   352.6 2123.53
  419.582120.822   619.6 2123.25  651.462122.048   730.5 2121.88   767.4 2124.56
   807.1 2118.57   841.2 2116.87   892.2 2116.24   895.1 2116.73   898.1 2117.96
   908.3 2132.34   918.8  2143.7   929.2 2153.52  948.542168.672  999.28 2203.16
  1013.1  2211.4  1028.4 2223.08  1044.6 2225.75  1060.3 2236.18  1094.2 2250.99
#Mann= 9 ,-1 , 0
       0     .05       0   187.7      .1       0  419.58     .05       0
  651.46     .06       0   767.4      .1       0   841.2    .045       0
   895.1      .1       0  948.54     .12       0  999.28      .1       0
Bank Sta=841.2,895.1
XS Rating Curve= 0 ,0
Exp/Cntr(USF)=0,0
Exp/Cntr=0.3,0.1

Type RM Length L Ch R = 1 ,43096   ,61.6,61.7,61.6
XS GIS Cut Line= 3
2435334.42721578564340.4208525042436008.24445587564097.097960249
2436416.27822904564042.818238131
#Sta/Elev= 30
       0 2200.88    36.9  2195.6    77.3 2187.38  158.792167.745   179.4 2161.19
   196.4 2153.89   238.9 2129.14  259.842124.165   285.7 2119.45   298.4 2120.26
   315.4 2118.91   485.5 2119.56   630.1  2118.2   676.9 2121.66  764.312119.698
   783.8 2119.07   801.4 2113.36     808 2112.18   832.2 2113.24   832.2 2113.25
   856.4 2118.57  863.67 2122.98   872.6  2127.8   929.1 2148.88   949.7 2159.59
   965.4 2169.81   977.5 2172.26   989.6 2180.67  1023.1 2198.46    1128  2247.8
#Mann= 7 ,-1 , 0
       0     .05       0  158.79      .1       0  259.84     .05       0
  764.31     .06       0   801.4    .045       0   832.2     .06       0
  863.67      .1       0
Bank Sta=801.4,832.2
XS Rating Curve= 0 ,0
Exp/Cntr(USF)=0,0
Exp/Cntr=0.5,0.3

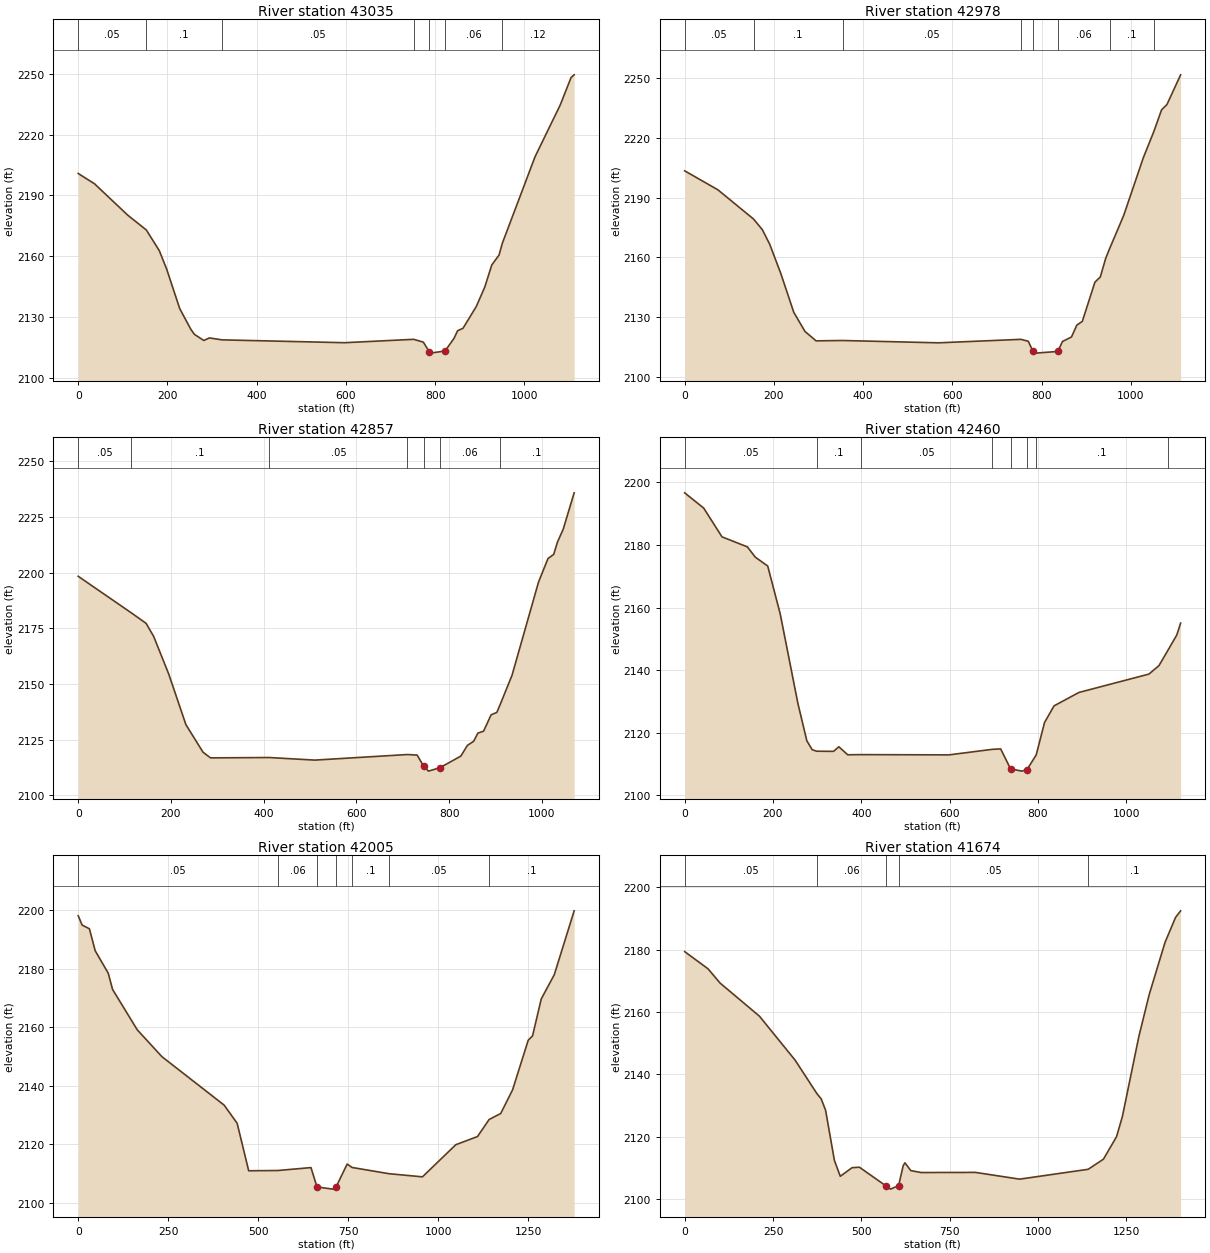
Type RM Length L Ch R = 1 ,43035   ,57.1,56.7,58.3
XS GIS Cut Line= 3
2435340.04235945564347.9077107282436013.85959954564158.864540591
 2436421.8933727564102.713103917
#Sta/Elev= 30
       0 2200.81    36.5 2195.74   111.2 2180.22  152.682172.959   181.8 2162.75
   198.5 2153.53   227.5 2134.19   252.5 2123.95   260.4 2121.48   281.5 2118.45
     294 2119.71  322.392118.753   597.2 2117.35  752.08 2119.02   773.7 2117.62
     787 2112.89   789.9 2112.21   822.4 2113.29   842.4  2119.5   850.4 2123.23
   862.6 2124.48   892.1 2135.12   911.2 2144.69   927.1 2155.72   943.3 2160.55
  950.77 2166.43    1024 2209.04  1080.6 2234.65  1104.8 2248.14  1111.7 2249.47
#Mann= 7 ,-1 , 0
       0     .05       0  152.68      .1       0  322.39     .05       0
  752.08     .06       0     787    .045       0   822.4     .06       0
  950.77     .12       0
#XS Ineff= 2 , 0
             760    2116     840            2116
Permanent Ineff=
       F       F
Bank Sta=787,822.4
XS Rating Curve= 0 ,0
Exp/Cntr(USF)=0,0
Exp/Cntr=0.5,0.3

Type RM Length L Ch R = 1 ,42978   ,122.8,120.9,119.4
XS GIS Cut Line= 3
2435347.52921767564404.0591474022436021.34645776564215.015977265
2436429.38023093564158.864540591
#Sta/Elev= 30
       0 2203.48    74.4 2193.94  154.292179.247   174.1 2173.88   190.7 2166.52
   215.6 2151.77   244.5 2132.35   269.6 2122.71   294.5 2117.96  354.192118.141
   568.7 2116.97  753.67 2118.72   770.2 2117.75   780.72112.742   786.4 2111.79
   836.3 2112.63   846.9 2117.64   867.1 2119.93   879.2 2125.92   891.3 2127.74
   919.6 2147.48   931.7  2150.1   943.8 2159.49  952.372164.254   984.2 2181.09
  1028.2 2210.13 1051.712223.264    1069 2234.15  1081.1 2236.85  1111.7 2251.76
#Mann= 8 ,-1 , 0
       0     .05       0  154.29      .1       0  354.19     .05       0
  753.67     .06       0   780.7    .045       0   836.3     .06       0
  952.37      .1       0 1051.71     .12       0
Bank Sta=780.7,836.3
XS Rating Curve= 0 ,0
Exp/Cntr(USF)=0,0
Exp/Cntr=0.5,0.3

Type RM Length L Ch R = 1 ,42857   ,394.8,397.5,398.7
XS GIS Cut Line= 2
2435399.93722523564477.0560150782436446.22566193564256.193697493
#Sta/Elev= 30
       0 2198.39  113.392182.118   146.3 2177.27   162.7 2171.38   195.4 2154.36
   232.2 2131.75     269 2119.39   285.3 2116.81  411.672116.972   510.2 2115.81
  709.962118.317   730.9 2118.06  744.94 2113.01   755.4 2110.86   779.9 2112.41
   824.9 2117.59   839.1 2122.41   852.6 2124.27   861.7 2127.94     874 2128.81
   890.3 2136.16   902.6 2137.24  908.82 2140.28   935.3 2153.88   992.5  2195.8
  1012.9 2206.35  1025.2 2208.22  1033.4  2213.8  1045.6 2219.47  1069.3 2235.88
#Mann= 7 ,-1 , 0
       0     .05       0  113.39      .1       0  411.67     .05       0
  709.96     .06       0  744.94    .045       0   779.9     .06       0
  908.82      .1       0
Bank Sta=744.94,779.9
XS Rating Curve= 0 ,0
Exp/Cntr(USF)=0,0
Exp/Cntr=0.3,0.1

Type RM Length L Ch R = 1 ,42460   ,449,454.1,458.7
XS GIS Cut Line= 2
2435464.37946402564792.9579745182436579.66716169564659.906108831
#Sta/Elev= 30
       0 2196.62    43.1 2191.74    84.5 2182.57   142.1 2179.35     160 2176.07
   188.1 2173.24   216.3 2158.01   256.5 2129.33   276.7 2117.43   288.8 2114.59
  299.112114.109   337.1 2114.06   349.2 2115.53   369.3 2112.97  398.522113.019
   598.7 2112.94  696.732114.711   715.7 2114.84  738.23 2108.43   764.1 2107.75
   775.4 2108.24  796.142112.926     815 2123.26   836.5 2128.59   892.9 2132.87
  1051.5 2138.74  1074.1 2141.43 1094.352146.308  1114.5 2151.21  1123.2 2155.02
#Mann= 8 ,-1 , 0
       0     .05       0  299.11      .1       0  398.52     .05       0
  696.73     .06       0  738.23    .045       0   775.4     .06       0
  796.14      .1       0 1094.35     .06       0
Bank Sta=738.23,775.4
XS Rating Curve= 0 ,0
Exp/Cntr(USF)=0,0
Exp/Cntr=0.3,0.1

Type RM Length L Ch R = 1 ,42005   ,328.2,331.7,338.7
XS GIS Cut Line= 2
2435472.20604435565074.714866562 2436841.8576029565223.419892918
#Sta/Elev= 30
       0 2198.06      11 2194.87    31.1 2193.62    47.2 2186.11    83.4 2178.45
    95.5 2172.89   163.9 2159.12   232.3 2149.95   405.3 2133.38   441.5 2127.18
   473.6 2110.94  554.79 2111.03   646.6 2112.03   663.3 2105.42     707 2104.67
  716.42 2105.45   747.2 2113.24  760.832112.066  863.85 2109.93   956.3 2108.87
  1048.9 2119.84  1109.3 2122.64 1141.372128.444  1173.7 2130.51  1206.7  2138.6
  1250.1 2155.54  1262.2 2157.04  1286.3 2169.64  1322.5 2177.93  1377.7 2199.75
#Mann= 7 ,-1 , 0
       0     .05       0  554.79     .06       0   663.3    .045       0
  716.42     .06       0  760.83      .1       0  863.85     .05       0
 1141.37      .1       0
Bank Sta=663.3,716.42
XS Rating Curve= 0 ,0
Exp/Cntr(USF)=0,0
Exp/Cntr=0.3,0.1

Type RM Length L Ch R = 1 ,41674   ,385.5,381.2,374.4
XS GIS Cut Line= 2
2435507.42565586565309.5122765982436857.51076357565693.014712991
#Sta/Elev= 30
       0 2179.34    66.2 2173.82   100.3 2169.25   211.7 2158.64   312.8 2144.52
  374.292133.824   386.4 2132.15   398.8  2128.5   423.8 2112.41   440.4 2107.34
   473.7  2110.1   494.5 2110.25   569.3  2104.3   582.8 2103.23   605.5 2104.38
   618.4 2110.74   623.4 2111.66     640 2109.16   669.1 2108.55   822.9 2108.59
   947.7 2106.43 1141.812109.579  1185.1 2112.83  1222.1 2120.02  1238.7 2126.49
  1285.5 2152.23  1314.6 2165.57  1359.3 2182.26  1389.1 2190.29  1403.5 2192.41
#Mann= 5 ,-1 , 0
       0     .05       0  374.29     .06       0   569.3    .045       0
   605.5     .05       0 1141.81      .1       0
Bank Sta=569.3,605.5
XS Rating Curve= 0 ,0
Exp/Cntr(USF)=0,0
Exp/Cntr=0.3,0.1

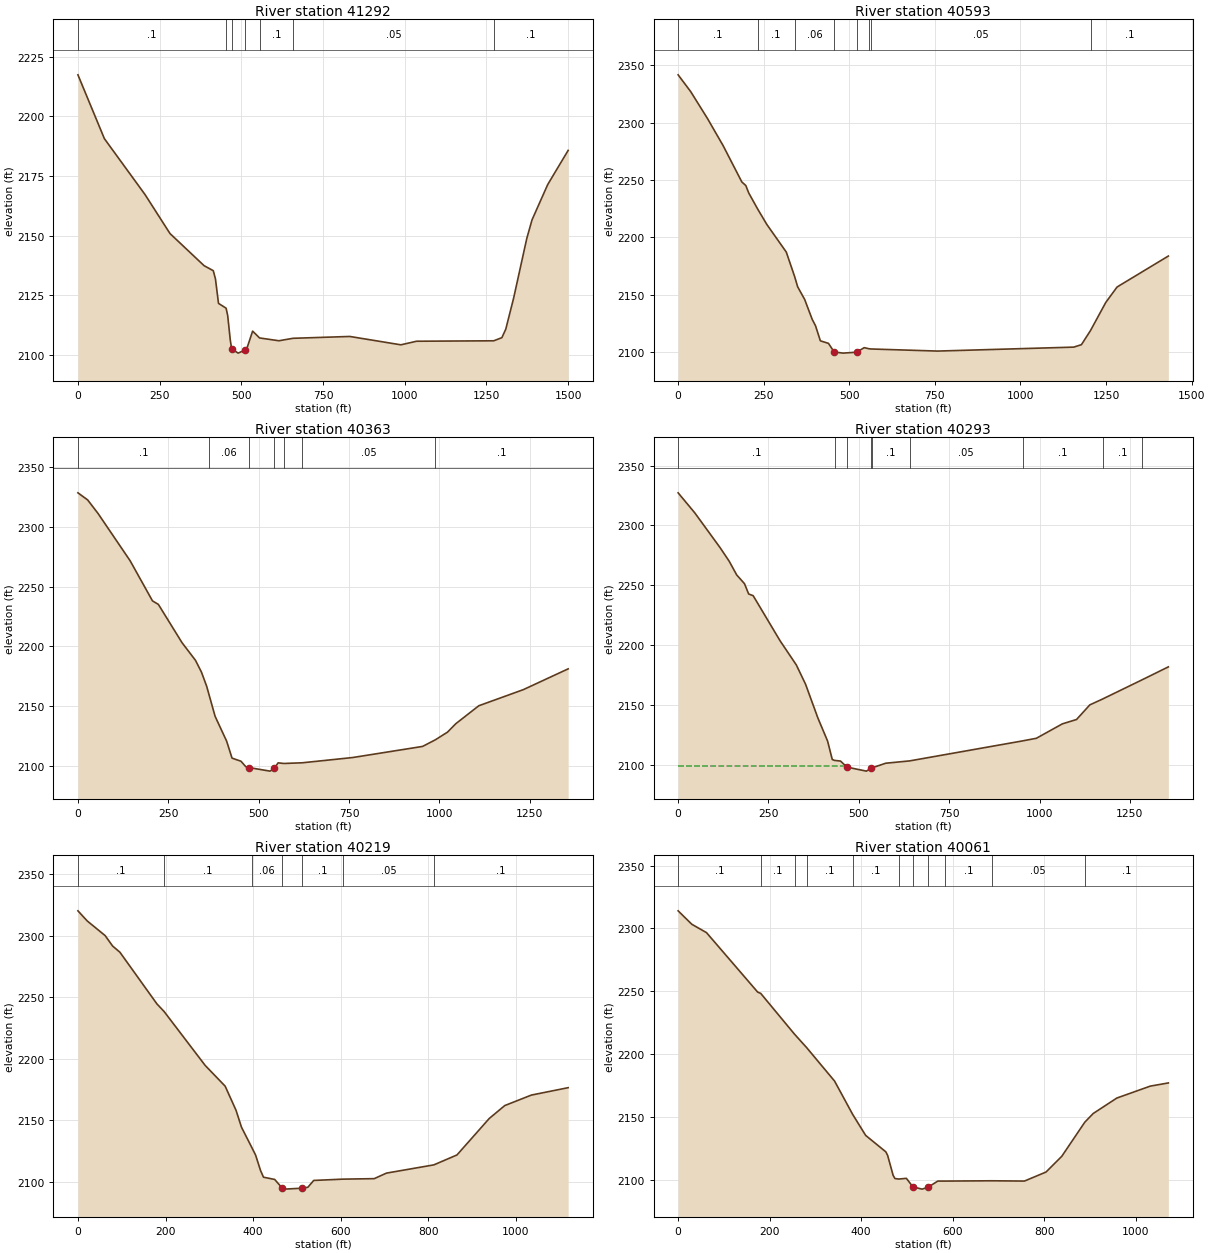
Type RM Length L Ch R = 1 ,41292   ,719.1,699.5,681.4
XS GIS Cut Line= 2
2435374.37379017565739.9741949982436869.25063407565865.199480351
#Sta/Elev= 30
       0 2217.36      81 2190.62   205.5 2167.18   281.7 2150.89   386.1 2137.42
   414.2 2135.33   420.8 2131.91   430.2 2121.63  453.422119.617   458.3 2116.51
   466.3  2106.2   470.4 2102.54   490.4  2100.8   510.5 2102.08   518.5  2103.4
   534.6 2110.02  555.782107.161   614.9 2105.98  658.142107.009   831.9 2107.78
   988.1 2104.28  1036.3 2105.78 1272.282105.964  1297.2 2107.27  1309.2 2110.83
  1333.3 2123.87  1373.4 2148.78  1389.5  2156.6  1437.6 2171.42  1500.1 2185.71
#Mann= 7 ,-1 , 0
       0      .1       0  453.42     .06       0   470.4    .045       0
   510.5     .06       0  555.78      .1       0  658.14     .05       0
 1272.28      .1       0
Bank Sta=470.4,510.5
XS Rating Curve= 0 ,0
Exp/Cntr(USF)=0,0
Exp/Cntr=0.3,0.1

Type RM Length L Ch R = 1 ,40593   ,222.2,229.6,230.8
XS GIS Cut Line= 2
2435652.21739205566659.5973843072436861.42405374565892.592511522
#Sta/Elev= 30
       0 2341.84    36.6 2327.27    85.8 2303.72   131.3 2280.17   186.1 2248.41
   197.7 2245.29   206.4 2238.73  232.322224.802   259.2  2211.3     316 2187.22
  340.362165.868   349.2 2156.94   369.6 2145.93   391.8 2128.45   401.3 2123.01
   415.5 2109.83   439.2  2107.6   455.6 2100.14   481.7 2099.09   522.3 2099.94
   543.4 2103.86  556.432102.968  563.012102.707   757.9 2100.88  1155.6 2104.33
    1178 2106.46 1204.652118.857  1249.1 2143.29  1282.2 2156.78  1431.9 2183.78
#Mann= 8 ,-1 , 0
       0      .1       0  232.32      .1       0  340.36     .06       0
   455.6    .045       0   522.3     .06       0  556.43      .1       0
  563.01     .05       0 1204.65      .1       0
Bank Sta=455.6,522.3
XS Rating Curve= 0 ,0
Exp/Cntr(USF)=0,0
Exp/Cntr=0.3,0.1

Type RM Length L Ch R = 1 ,40363   ,70.4,70.3,70.3
XS GIS Cut Line= 4
2435717.02687756566736.518894215 2436077.6252549566638.993481481
2436579.05989516566389.4315407072436925.75314375 566147.46717416
#Sta/Elev= 30
       0 2328.54      27 2322.58      56 2311.11   144.3 2271.73   206.3 2238.06
   222.6 2235.11     288 2203.07   325.3 2188.26   341.9 2178.34   356.3  2166.5
  362.482159.788   379.6 2141.37   411.5 2120.58   426.4 2106.39   451.1  2103.8
   464.5  2099.2   474.1 2098.44   531.5  2095.5  543.44 2097.88   553.9 2102.41
  570.012101.916  620.86 2102.48   760.5  2106.9   953.6 2116.18  989.132121.759
  1022.5 2128.13  1045.5  2135.2  1109.2 2150.25  1232.2 2163.71  1356.4 2181.13
#Mann= 7 ,-1 , 0
       0      .1       0  362.48     .06       0   474.1    .045       0
  543.44     .06       0  570.01      .1       0  620.86     .05       0
  989.13      .1       0
Bank Sta=474.1,543.44
XS Rating Curve= 0 ,0
Exp/Cntr(USF)=0,0
Exp/Cntr=0.5,0.3

Type RM Length L Ch R = 1 ,40293   ,74.6,74.6,74.7
XS GIS Cut Line= 4
2435758.62053436566794.2878619862436119.21891169566696.762449253
2436620.65355195566447.2005084782436967.34680054566205.236141932
#Sta/Elev= 30
       0 2327.19    46.1 2310.47   116.5 2281.25   141.2 2270.14   162.1 2258.62
   183.6 2251.34   195.2 2242.72   207.7 2241.27   282.2 2203.59   327.1 2183.44
   352.7  2167.3   386.8 2139.09   413.6 2119.87   426.5 2104.49  432.712103.736
   449.3 2103.18   467.2 2098.12   520.8 2094.77   534.2 2097.16   536.72097.521
   574.4 2101.37   640.72103.318  953.822120.058   991.1 2122.19  1063.3 2134.26
  1102.4 2137.89  1139.1 2150.08 1174.27 2154.96 1284.492171.135  1356.4 2181.84
#Mann= 9 ,-1 , 0
       0      .1       0  432.71     .06       0   467.2    .045       0
   534.2     .06       0   536.7      .1       0   640.7     .05       0
  953.82      .1       0 1174.27      .1       0 1284.49      .1       0
#XS Ineff= 2 , 0
             465    2099     565            2099
Permanent Ineff=
       F       F
Bank Sta=467.2,534.2
XS Rating Curve= 0 ,0
Exp/Cntr(USF)=0,0
Exp/Cntr=0.5,0.3

Type RM Length L Ch R = 1 ,40219   ,157.8,157.8,160.1
XS GIS Cut Line= 4
2435802.52494986566854.367588469 2436163.1233272566756.842175735
2436604.47824098566539.6308569132436847.18734758566614.240433756
#Sta/Elev= 30
       0 2320.36    21.3  2312.1    62.2 2300.18    79.2 2291.71    95.9 2286.65
   180.5 2244.54  196.752238.417   290.6  2194.5   336.2 2177.63   361.1 2157.92
   373.5  2144.2  397.372127.484   405.8 2121.44   417.1 2108.87   423.7 2103.52
   449.3 2101.68   465.6    2095   471.5 2093.81   511.7 2094.57     525 2095.32
   538.4 2100.88  605.072101.933   676.6 2102.34   704.5 2106.84  812.782113.563
   865.5 2121.62   939.2 2151.32   974.7 2161.84  1035.4 2170.37  1119.4 2176.39
#Mann= 7 ,-1 , 0
       0      .1       0  196.75      .1       0  397.37     .06       0
   465.6    .045       0   511.7      .1       0  605.07     .05       0
  812.78      .1       0
Bank Sta=465.6,511.7
XS Rating Curve= 0 ,0
Exp/Cntr(USF)=0,0
Exp/Cntr=0.5,0.3

Type RM Length L Ch R = 1 ,40061   ,113.2,120.5,134.3
XS GIS Cut Line= 3
2435821.13103799566860.8263177252436306.39036727566858.515559014
2436851.72942304566643.614998903
#Sta/Elev= 30
       0 2314.07      30 2303.35      62 2296.72   173.9 2249.35  180.562248.307
  254.392215.849   281.1 2205.05   341.9 2178.51  381.632151.873   409.9 2135.22
   453.9 2122.16   457.9 2119.31   469.9 2103.43   473.9 2100.86  482.172100.469
   498.9 2101.03   513.2 2094.17   533.3 2092.44   546.2 2093.97   567.6 2098.84
  583.792098.843  685.442099.079   756.8 2098.85   804.1 2106.06   838.5 2118.58
  888.74 2145.72   907.3  2152.7   958.8 2164.97  1031.9 2174.47  1071.4 2177.01
#Mann= 11 ,-1 , 0
       0      .1       0  180.56      .1       0  254.39      .1       0
   281.1      .1       0  381.63      .1       0  482.17     .06       0
   513.2    .045       0   546.2     .06       0  583.79      .1       0
  685.44     .05       0  888.74      .1       0
Bank Sta=513.2,546.2
XS Rating Curve= 0 ,0
Exp/Cntr(USF)=0,0
Exp/Cntr=0.3,0.1