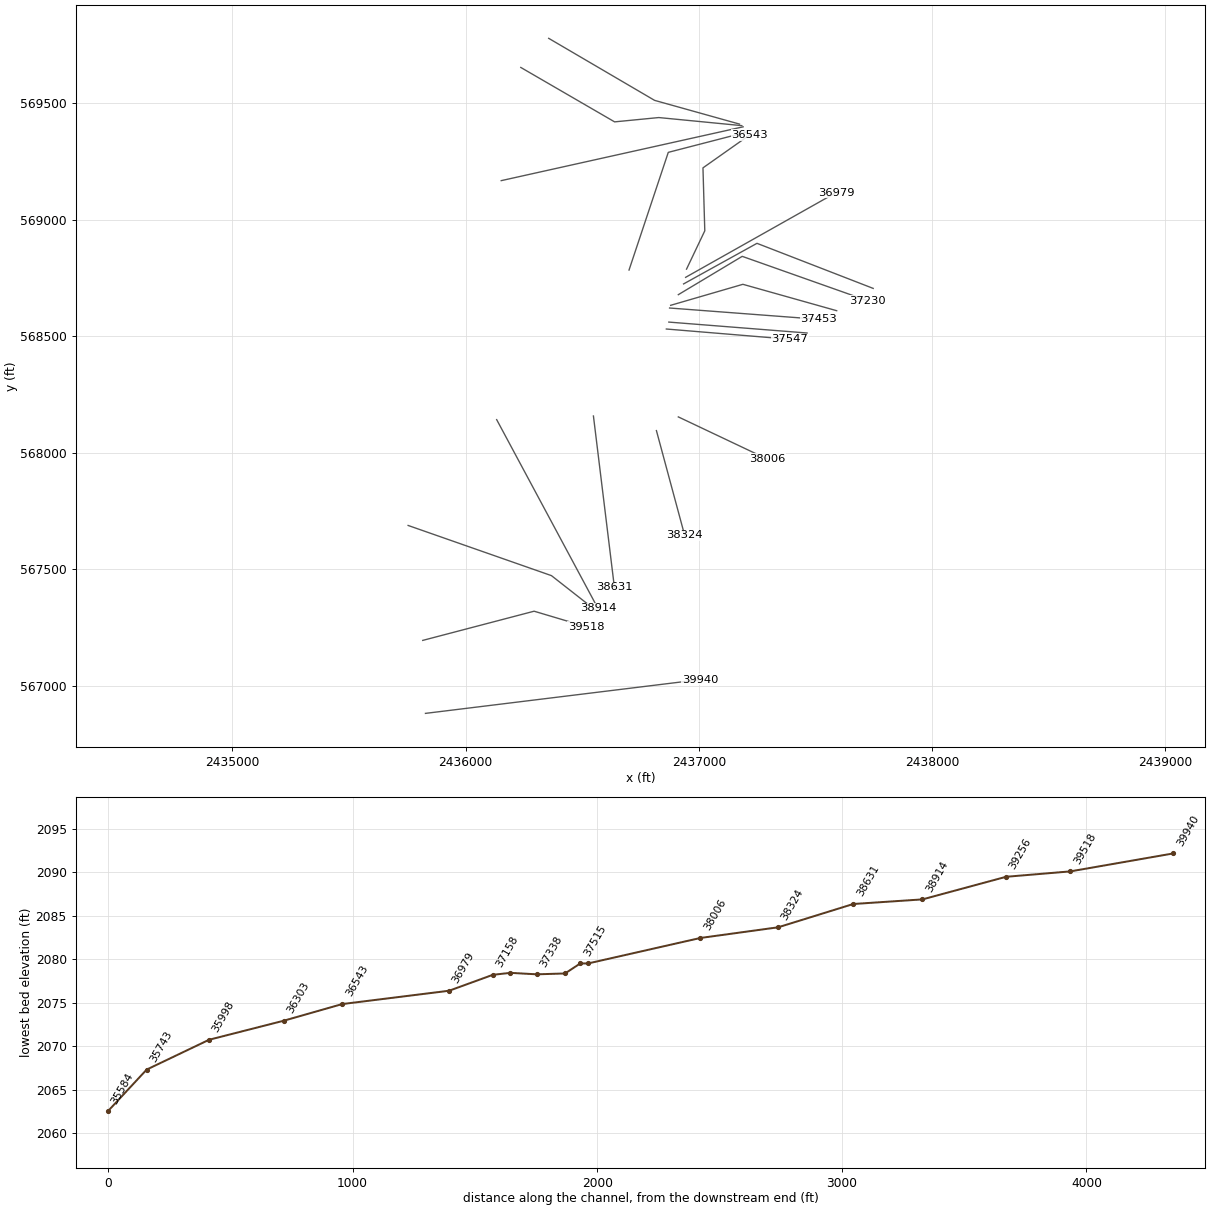
HEC-RAS study THORNCK.prj: THORNCK

--- THORNCK.g01 (geometry) --- (continued)

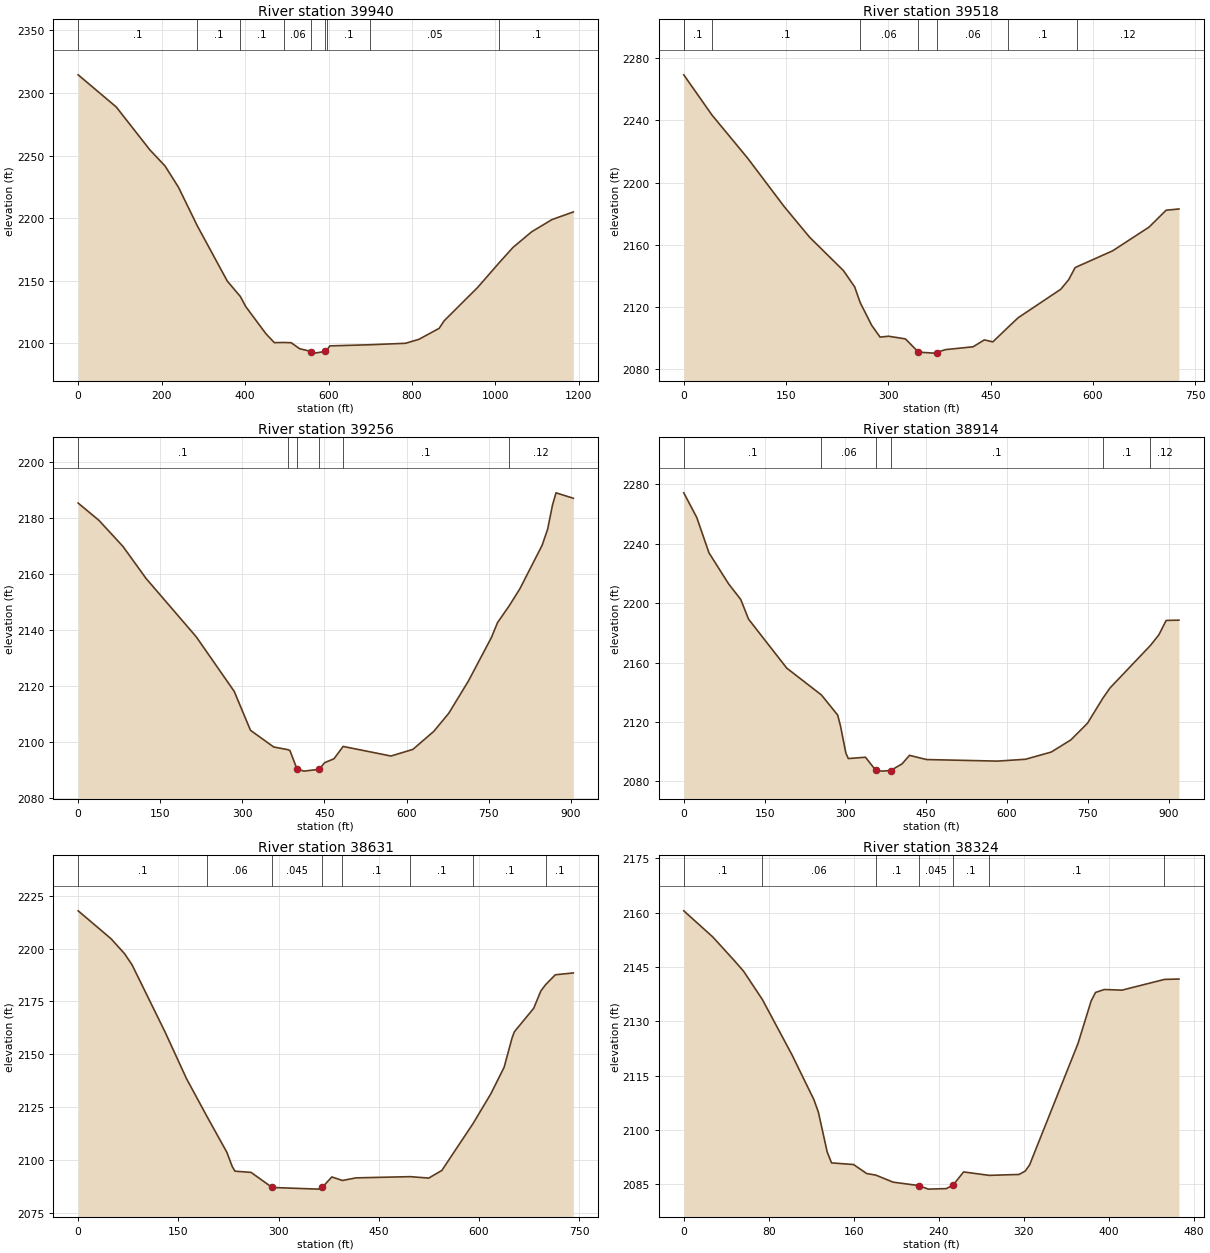
Type RM Length L Ch R = 1 ,39940   ,422,421.8,430.5
XS GIS Cut Line= 2
2435828.31544958566882.6549238422437006.21578993567027.446660031
#Sta/Elev= 30
       0 2314.47    91.3 2288.78     172 2254.47   208.3 2241.63   240.6 2224.55
  285.442193.918   357.4 2149.73  388.882137.327   401.7 2129.32   450.1 2107.62
   470.2 2100.53  492.31 2100.67   510.5 2100.48   530.7 2095.71   558.9 2093.43
     567 2092.16   592.5 2093.53  595.752094.472   603.2 2097.94  699.182098.852
   784.6 2100.02   816.8 2103.21   865.2 2111.96   877.2 2117.99   957.8 2144.76
 1009.482164.524  1042.2 2176.59  1086.8 2189.05  1135.5 2198.83  1186.8 2204.94
#Mann= 9 ,-1 , 0
       0      .1       0  285.44      .1       0  388.88      .1       0
  492.31     .06       0   558.9    .045       0   592.5     .06       0
  595.75      .1       0  699.18     .05       0 1009.48      .1       0
Bank Sta=558.9,592.5
XS Rating Curve= 0 ,0
Exp/Cntr(USF)=0,0
Exp/Cntr=0.3,0.1

Type RM Length L Ch R = 1 ,39518   ,278.6,262.3,251.9
XS GIS Cut Line= 3
2435816.57557908567195.7181372242436293.99697948567320.943422576
2436517.05451902567254.417489733
#Sta/Elev= 30
       0 2269.39     .532269.047   41.382243.487    93.6 2215.74   147.3  2184.5
   184.5  2164.8   234.2 2143.26   250.7 2132.75  258.66 2122.75   275.4 2108.19
   287.9 2100.42   300.3 2100.98   325.1 2099.26   344.2 2090.75   366.5 2090.09
   370.9 2090.48   383.5 2092.33   424.4 2094.18   440.9 2098.63   453.3 2097.32
  475.942106.871   490.5 2112.89   553.1 2131.28   564.7 2137.47     574 2145.16
  577.472145.894     629 2155.99   682.5 2171.29   707.5 2182.16   726.3 2182.97
#Mann= 8 ,-1 , 0
       0      .1       0     .53      .1       0   41.38      .1       0
  258.66     .06       0   344.2    .045       0   370.9     .06       0
  475.94      .1       0  577.47     .12       0
Bank Sta=344.2,370.9
XS Rating Curve= 0 ,0
Exp/Cntr(USF)=0,0
Exp/Cntr=0.3,0.1

Type RM Length L Ch R = 1 ,39256   ,358.6,341.9,329.8
XS GIS Cut Line= 3
 2435753.9629364  567688.79269832436368.34949266  567473.5617391
2436567.92729119567317.030132409
#Sta/Elev= 30
       0 2185.36      38 2179.17    81.9 2169.84   124.1 2158.38   215.6 2137.55
   285.1    2118   314.8 2104.08   357.2 2098.11  383.132097.145   386.9 2096.82
   399.6 2090.32   412.3 2089.47   440.1 2090.11   450.4  2092.5   467.4  2093.9
  484.012098.303   571.5 2094.87   611.5 2097.25   649.6 2103.68     677 2110.16
   712.8 2121.66   754.8 2137.21   766.2 2142.63  786.882148.439   806.8 2154.65
   847.6 2170.26   857.7 2176.04   866.6 2184.69     873 2189.03   904.6 2187.09
#Mann= 6 ,-1 , 0
       0      .1       0  383.13     .06       0   399.6    .045       0
   440.1     .06       0  484.01      .1       0  786.88     .12       0
Bank Sta=399.6,440.1
XS Rating Curve= 0 ,0
Exp/Cntr(USF)=0,0
Exp/Cntr=0.3,0.1

Type RM Length L Ch R = 1 ,38914   ,290.1,282.8,279.4
XS GIS Cut Line= 2
2436133.55208262568142.7343577032436567.92729119567332.683293078
#Sta/Elev= 30
       0 2274.37    24.1 2257.79    46.8 2233.95    83.1 2213.11   105.8 2202.49
   120.2 2189.31   191.1  2156.3  255.562138.173   285.7 2124.65     291  2117.2
     301  2098.9   305.5 2095.33   337.3 2096.24   356.6 2087.32   369.1 2086.87
     384 2087.28   405.4 2091.82     419  2097.5   450.7 2094.67   582.4 2093.62
   634.3 2094.86   682.2 2099.72   718.5 2107.89   749.5 2119.15   777.62135.785
   791.1 2142.85  866.412171.604   881.9 2178.68   895.5 2188.39   919.2 2188.59
#Mann= 6 ,-1 , 0
       0      .1       0  255.56     .06       0   356.6    .045       0
     384      .1       0   777.6      .1       0  866.41     .12       0
Bank Sta=356.6,384
XS Rating Curve= 0 ,0
Exp/Cntr(USF)=0,0
Exp/Cntr=0.3,0.1

Type RM Length L Ch R = 1 ,38631   ,301.6,307.1,304.1
XS GIS Cut Line= 2
2436548.36084035568158.387518373 2436638.3665142567422.688966925
#Sta/Elev= 30
       0 2217.83    49.3 2204.62    69.4  2197.6    80.7  2192.3   129.9 2160.69
   162.1 2138.58  192.922120.612   222.6 2103.73   230.6 2097.03   234.7 2094.82
   258.8 2094.25   290.4 2087.12   359.6 2086.34   365.3 2087.16   379.7 2092.09
  395.642090.429     416 2091.66     4972092.231   524.8 2091.56   544.4 2095.18
  591.182117.364   617.8 2131.42   637.6 2143.92   649.5 2157.77     653 2160.71
   681.9 2171.79   692.5 2179.92  699.722182.948   714.2 2187.61   741.2 2188.49
#Mann= 8 ,-1 , 0
       0      .1       0  192.92     .06       0   290.4    .045       0
   365.3      .1       0  395.64      .1       0     497      .1       0
  591.18      .1       0  699.72      .1       0
Bank Sta=290.4,365.3
XS Rating Curve= 0 ,0
Exp/Cntr(USF)=0,0
Exp/Cntr=0.3,0.1

Type RM Length L Ch R = 1 ,38324   ,297.3,318.3,335.9
XS GIS Cut Line= 2
 2436818.3778619568095.7748756962436939.68985708 567645.74650646
#Sta/Elev= 30
       0 2160.49    27.3 2153.28    48.1 2146.58    56.3 2143.82   74.042135.982
   101.8 2120.77   122.5 2108.36   126.7 2104.91     135 2093.92   139.1  2090.9
   159.8 2090.45   172.2 2087.96  180.732087.535   197.1 2085.58     221 2084.65
   230.2 2083.66   247.1  2083.8   253.6 2084.81   263.4 2088.41  287.41 2087.46
   315.6 2087.71   321.4 2088.64   325.5 2090.33   371.1 2123.87   383.5 2135.64
   387.6 2137.96   395.9 2138.77   412.5 2138.59   452.52141.558   466.1 2141.66
#Mann= 7 ,-1 , 0
       0      .1       0   74.04     .06       0  180.73      .1       0
     221    .045       0   253.6      .1       0  287.41      .1       0
   452.5      .1       0
Bank Sta=221,253.6
XS Rating Curve= 0 ,0
Exp/Cntr(USF)=0,0
Exp/Cntr=0.3,0.1

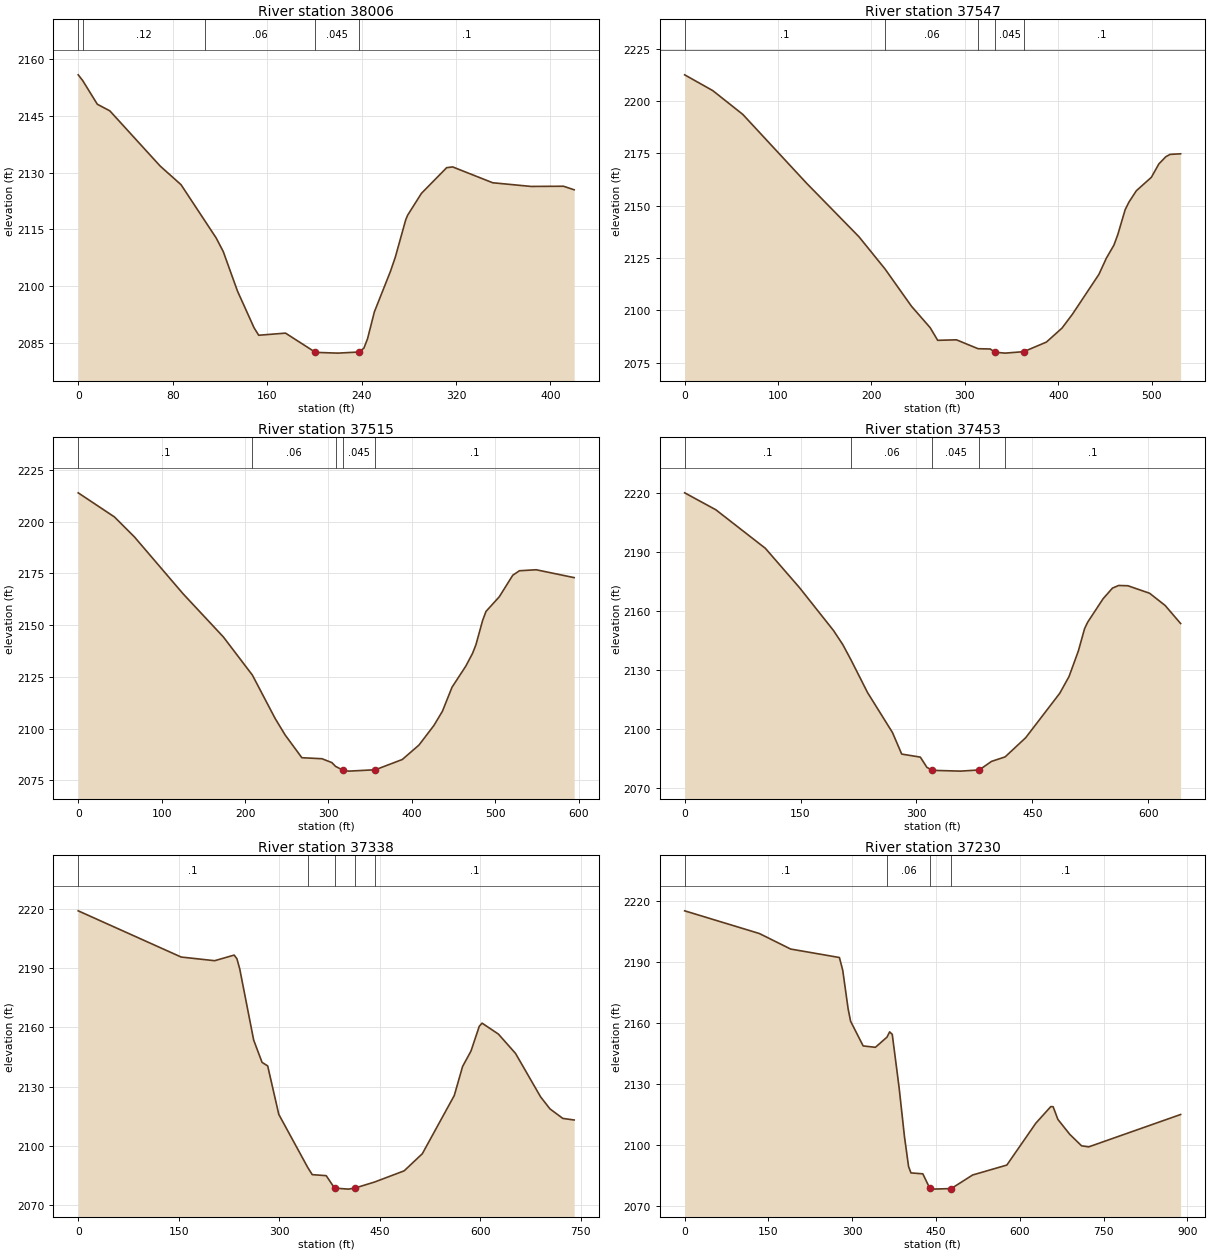
Type RM Length L Ch R = 1 ,38006   ,450.5,458.8,466.5
XS GIS Cut Line= 2
2436912.29682591568154.4742282052437291.88597214567974.462880511
#Sta/Elev= 30
       0 2155.74     3.72154.275    16.2 2147.99    26.8 2146.25    69.4 2131.72
    87.1  2126.8  107.112117.365   116.9 2112.75   122.9 2109.16   134.9 2098.79
     149 2089.08   152.9 2087.14   175.6  2087.7     201 2082.63   219.9 2082.43
   237.6 2082.72     242 2083.73   245.1 2086.24   250.9 2093.32   264.5 2103.98
   268.6  2107.7   277.4 2117.52     279 2118.74   290.7  2124.5   312.1 2131.28
   317.2 2131.48   351.1 2127.31   383.6 2126.34   411.1 2126.39   420.1 2125.46
#Mann= 5 ,-1 , 0
       0      .1       0     3.7     .12       0  107.11     .06       0
     201    .045       0   237.6      .1       0
Bank Sta=201,237.6
XS Rating Curve= 0 ,0
Exp/Cntr(USF)=0,0
Exp/Cntr=0.3,0.1

Type RM Length L Ch R = 1 ,37547   ,32.4,31.9,32
XS GIS Cut Line= 2
2436860.97245788568531.5048656862437390.13620267568487.600450179
#Sta/Elev= 30
       0 2212.52    30.1 2204.97    62.2 2193.62   130.4 2160.77   186.6 2135.13
  214.542119.715   242.8 2101.93   262.9 2091.64   270.9 2085.62     291 2085.86
  314.162081.609   327.1 2081.48   332.5 2079.92   343.1  2079.5   363.1 2080.21
   387.3 2084.78     404 2091.46   415.2 2098.12   443.5 2117.13   451.5 2124.89
   459.6 2131.13   463.8 2136.23   471.6 2148.04   475.6 2151.63   483.6 2157.12
   499.7 2163.55   507.7 2169.93   515.2 2173.39   519.7 2174.49     531 2174.77
#Mann= 5 ,-1 , 0
       0      .1       0  214.54     .06       0  314.16      .1       0
   332.5    .045       0   363.1      .1       0
Bank Sta=332.5,363.1
XS Rating Curve= 0 ,0
Exp/Cntr(USF)=0,0
Exp/Cntr=0.5,0.3

Type RM Length L Ch R = 1 ,37515   ,61.5,62.2,66.3
XS GIS Cut Line= 2
2436871.66545809568561.2183974542437464.32480121568514.408911859
#Sta/Elev= 30
       0 2213.96    43.4 2202.32    67.5 2192.61   125.6 2165.23     174 2144.33
  208.792125.904     236 2104.99   248.1 2096.94   268.1 2085.98   292.2 2085.49
   304.1 2083.62  308.442081.808   317.5 2079.94   324.3  2079.5   356.2 2080.16
   388.5 2085.12   408.5  2092.1   426.4 2101.57   436.6 2108.43   448.1 2120.04
   464.7 2130.28   472.7 2136.41   476.7 2140.49   484.8 2152.31   488.8 2156.65
   504.8 2163.76   520.9 2174.14   528.9 2176.31     549 2176.79   594.5 2172.99
#Mann= 5 ,-1 , 0
       0      .1       0  208.79     .06       0  308.44      .1       0
   317.5    .045       0   356.2      .1       0
#XS Ineff= 2 , 0
             280    2084     390            2084
Permanent Ineff=
       F       F
Bank Sta=317.5,356.2
XS Rating Curve= 0 ,0
Exp/Cntr(USF)=0,0
Exp/Cntr=0.5,0.3

Type RM Length L Ch R = 1 ,37453   ,122.6,115.4,107.4
XS GIS Cut Line= 2
2436874.83701015 568621.624455412437514.91717306568573.098522481
#Sta/Elev= 30
       0 2219.91    40.3  2211.3   104.4  2191.7   148.6 2171.69   192.7 2149.84
   204.7 2142.69   215.42134.826   236.8 2118.24   268.9 2098.02   280.9 2087.02
     305 2085.48   313.5 2080.28   320.4 2078.75   357.1 2078.35   381.2 2078.95
   397.2 2083.31  414.762085.596   441.4 2095.36   485.5 2117.97   497.5 2126.49
   509.5 2139.41   517.6 2150.81   521.6 2154.11   541.6 2166.06   553.7 2171.45
   561.7 2172.79   573.7 2172.64   601.8 2168.82   621.9 2162.61   641.9 2153.44
#Mann= 5 ,-1 , 0
       0      .1       0   215.4     .06       0   320.4    .045       0
   381.2     .06       0  414.76      .1       0
Bank Sta=320.4,381.2
XS Rating Curve= 0 ,0
Exp/Cntr(USF)=0,0
Exp/Cntr=0.5,0.3

Type RM Length L Ch R = 1 ,37338   ,109.8,108.2,108.6
XS GIS Cut Line= 3
2436879.45852757568633.1782489642437189.10019483568723.297838688
2437591.17221052568610.070661855
#Sta/Elev= 30
       0 2218.91   153.6 2195.56   203.6  2193.7   232.8 2196.54   236.9 2194.67
   241.1 2189.53   261.9 2153.56   274.4 2142.32   282.8 2140.52   299.4 2116.01
  342.622089.172   349.3 2085.57   370.1 2085.06   382.6 2078.78   403.3 2078.25
   413.1 2078.79  442.592081.865   486.5  2087.5   513.6 2096.15   561.3 2125.58
   573.7 2140.25   586.2 2148.02   598.6 2160.56   602.8 2162.14   627.1 2156.63
   652.7 2146.85   690.1 2124.89   704.1 2118.81   723.3 2113.99   740.2 2113.19
#Mann= 5 ,-1 , 0
       0      .1       0  342.62     .06       0   382.6    .045       0
   413.1     .06       0  442.59      .1       0
Bank Sta=382.6,413.1
XS Rating Curve= 0 ,0
Exp/Cntr(USF)=0,0
Exp/Cntr=0.5,0.3

Type RM Length L Ch R = 1 ,37230   ,73,71.9,71.1
XS GIS Cut Line= 3
2436912.29682591 568678.855110622437186.22713762568843.213297645
2437721.97573664568653.586761212
#Sta/Elev= 30
       0  2215.4   133.7 2204.23   189.7 2196.59     277 2192.42     283 2186.08
   292.6 2167.16     297 2161.07   319.5 2148.91   341.4 2148.22  362.182153.234
   366.9 2155.82   371.6 2154.61   383.9 2128.31   393.5 2104.18   400.8 2089.53
   405.1  2086.4   426.3 2085.95     439 2078.74   443.3 2078.42   477.2 2078.69
   515.4 2085.37   576.7 2090.26   628.6 2110.87   655.4 2119.04   659.6 2118.98
   668.1 2112.74   689.3 2105.41   710.5 2099.73   723.3 2099.22   887.8 2115.15
#Mann= 4 ,-1 , 0
       0      .1       0  362.18     .06       0     439    .045       0
   477.2      .1       0
#XS Ineff= 2 , 0
             415    2082     505            2082
Permanent Ineff=
       F       F
Bank Sta=439,477.2
XS Rating Curve= 0 ,0
Exp/Cntr(USF)=0,0
Exp/Cntr=0.5,0.3

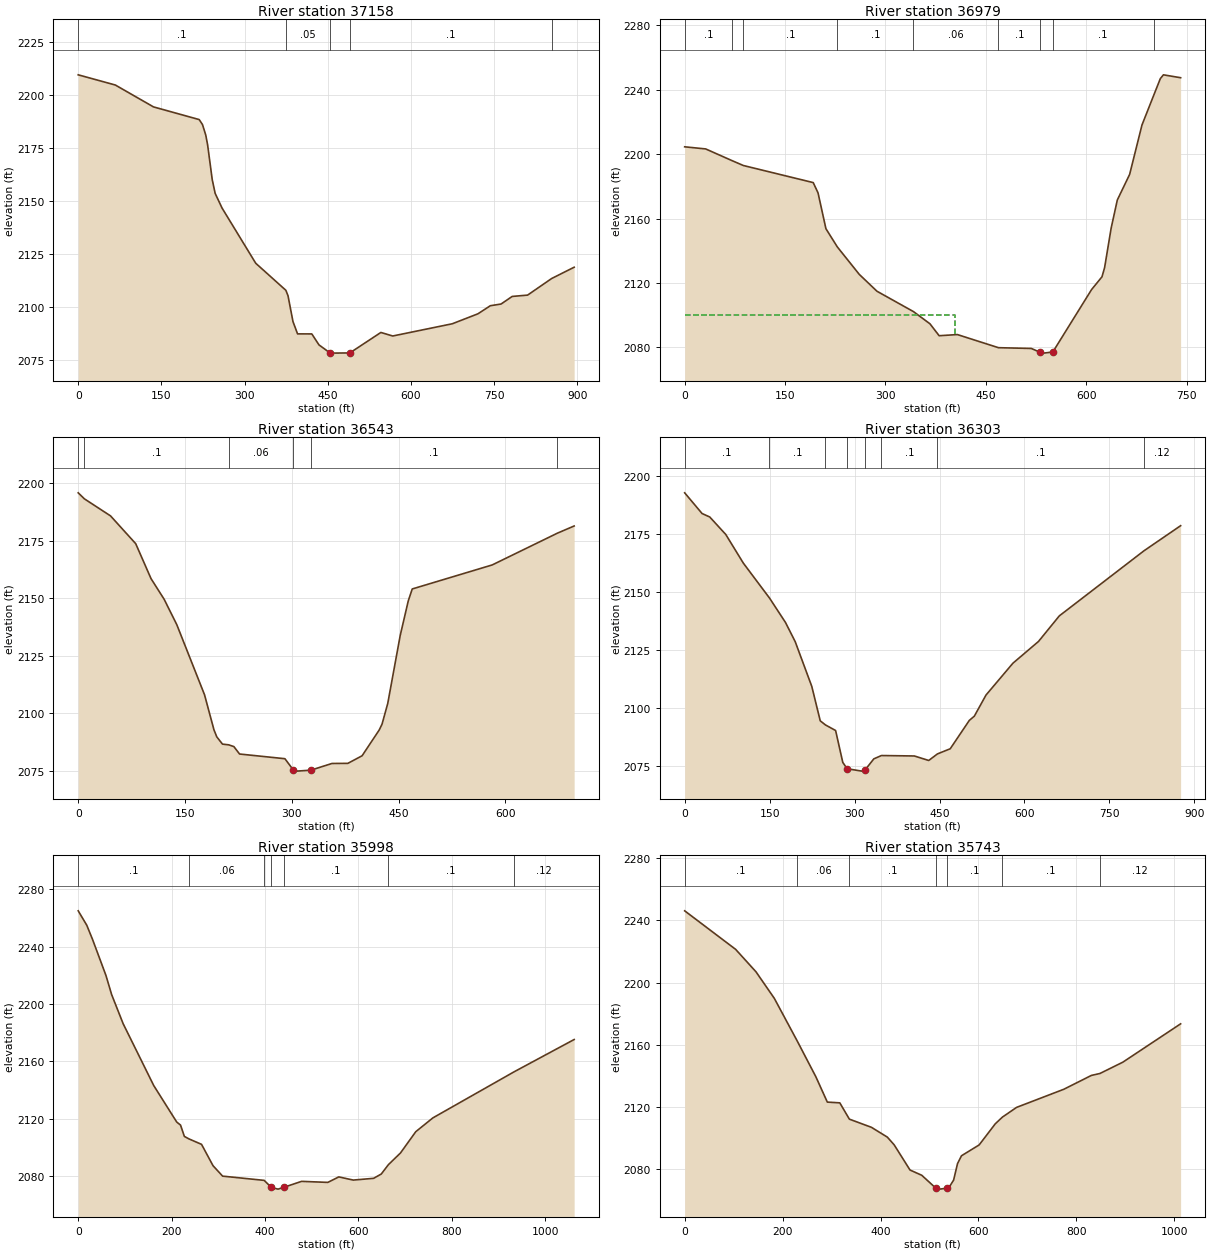
Type RM Length L Ch R = 1 ,37158   ,170.7,178.7,194
XS GIS Cut Line= 3
2436934.94002228 568724.97302515 2437249.4928532568899.083307712
2437747.77531932568705.734319894
#Sta/Elev= 30
       0 2209.32    66.9 2204.52   135.7 2194.21   218.1 2188.23     224  2185.9
   229.9 2180.96   233.2 2176.46   241.6 2159.94   246.9 2153.44   259.3 2146.55
     320 2120.54   374.3  2107.8   378.2 2105.24   387.1  2093.1   395.4 2087.26
   421.1 2087.24     434 2082.07   454.42078.198   454.7 2078.19   489.72078.289
   545.6 2087.93     567 2086.26   674.3 2092.02   720.5 2096.71   742.9 2100.52
   762.3 2101.33   782.3  2104.9   810.1 2105.53   853.4 2113.34     894 2118.67
#Mann= 5 ,-1 , 0
       0      .1       0   374.3     .05       0   454.4    .045       0
   489.7      .1       0   853.4     .05       0
Bank Sta=454.4,489.7
XS Rating Curve= 0 ,0
Exp/Cntr(USF)=0,0
Exp/Cntr=0.5,0.3

Type RM Length L Ch R = 1 ,36979   ,423.7,436.5,454.8
XS GIS Cut Line= 2
2436943.60314725568753.2076237982437589.29602485569117.143609354
#Sta/Elev= 30
       0 2204.59    31.4 2203.27   70.572196.033   87.662192.974   192.1 2182.35
   199.3 2175.98   211.1  2153.7  228.152142.371   260.9 2125.32   287.4 2114.82
  341.882102.183   366.6 2094.58   380.3 2087.18   407.6 2087.89     4692079.736
   518.1 2079.26   531.1 2076.89   536.4 2076.36   550.2 2077.06   608.1 2115.84
   623.7 2123.81   627.6 2129.51   637.4 2154.08   646.6 2171.54     665 2187.43
   683.4 2218.09  700.882236.494   710.9 2246.98   715.5 2249.33   741.2 2247.53
#Mann= 9 ,-1 , 0
       0      .1       0   70.57      .1       0   87.66      .1       0
  228.15      .1       0  341.88     .06       0     469      .1       0
   531.1    .045       0   550.2      .1       0  700.88     .12       0
#XS Ineff= 2 , 0
       0   403.3    2100               0
Permanent Ineff=
       F       F
Bank Sta=531.1,550.2
XS Rating Curve= 0 ,0
Exp/Cntr(USF)=0,0
Exp/Cntr=0.3,0.1

Type RM Length L Ch R = 1 ,36543   ,244.3,239.5,230
XS GIS Cut Line= 4
2436947.51643742568788.4272353042437025.78224076568952.785422329
2437017.95566043569222.8024438712437217.53345896569363.680889893
#Sta/Elev= 30
       0 2195.85    8.642193.244    45.4 2185.82    80.8 2173.72   102.3 2158.52
   120.7 2149.56   138.5 2138.49   177.4 2108.04   190.6 2092.84   194.6 2089.74
   202.6 2086.58  211.442086.258   218.6  2085.5   226.6 2082.27   290.3 2080.23
     302 2075.37   306.7 2074.83   326.7 2075.24   356.4 2078.16   378.7 2078.21
   398.7 2081.51   422.7  2092.7   426.7 2095.26   434.7 2104.24   452.2 2133.79
   463.5 2148.82   469.1 2154.04   581.4 2164.49  672.822178.283   696.5 2181.43
#Mann= 6 ,-1 , 0
       0      .1       0    8.64      .1       0  211.44     .06       0
     302    .045       0   326.7      .1       0  672.82     .12       0
Bank Sta=302,326.7
XS Rating Curve= 0 ,0
Exp/Cntr(USF)=0,0
Exp/Cntr=0.3,0.1

Type RM Length L Ch R = 1 ,36303   ,321.7,305.1,282.2
XS GIS Cut Line= 3
2436700.97915688568784.5139451362436869.25063407569289.328376714
2437201.88029829569375.420760394
#Sta/Elev= 30
       0 2192.86    30.7 2183.94    44.3 2182.44    72.6  2174.9   103.5 2162.59
  149.612147.572     178 2136.99   195.2 2128.69   224.4 2109.46   239.4 2094.58
  248.522092.833   266.5 2090.42   279.2 2076.66   286.9 2073.94   312.9 2072.91
   318.5 2073.42     334  2078.2  347.44 2079.63   405.6 2079.44   430.9  2077.5
  446.352080.332   468.9 2082.55   502.6 2094.77   511.4 2096.58   532.1 2105.71
   579.5  2119.4   624.8 2128.81   661.5 2139.82  810.992167.875   875.7 2178.69
#Mann= 8 ,-1 , 0
       0      .1       0  149.61      .1       0  248.52     .06       0
   286.9    .045       0   318.5     .06       0  347.44      .1       0
  446.35      .1       0  810.99     .12       0
Bank Sta=286.9,318.5
XS Rating Curve= 0 ,0
Exp/Cntr(USF)=0,0
Exp/Cntr=0.3,0.1

Type RM Length L Ch R = 1 ,35998   ,256.7,255,245.5
XS GIS Cut Line= 2
2436153.11853346569168.0163815292437190.14042779569398.900501398
#Sta/Elev= 30
       0 2264.93    18.4 2254.84    30.7 2244.98    59.4 2219.87    71.6 2206.49
    96.2  2186.2   161.8    2143     211 2117.55   219.2  2115.4   227.4 2107.51
  236.832105.826   264.2 2101.97   288.8 2087.08   309.3 2079.79  398.372076.829
  413.85 2071.89   428.1 2070.72  440.34 2071.98   478.6 2076.14   534.7 2075.42
   558.2 2079.25   589.2 2077.04   632.8 2078.25   649.2 2081.26  664.592087.816
   690.4 2095.96   723.1 2110.79   759.8 2120.44  933.39 2152.52  1062.4 2175.12
#Mann= 7 ,-1 , 0
       0      .1       0  236.83     .06       0  398.37      .1       0
  413.85    .045       0  440.34      .1       0  664.59      .1       0
  933.39     .12       0
Bank Sta=413.85,440.34
XS Rating Curve= 0 ,0
Exp/Cntr(USF)=0,0
Exp/Cntr=0.3,0.1

Type RM Length L Ch R = 1 ,35743   ,175.8,158.5,141.2
XS GIS Cut Line= 4
2436237.03256372569653.5402126052436639.10457942569420.153582807
2436828.58679371569438.6396524942437184.44363518569403.978271831
#Sta/Elev= 30
       0 2246.07   104.1 2221.31   145.7 2206.87   183.1 2189.83     230 2162.36
   267.9 2139.48   291.3  2123.2   316.8 2122.71  336.33 2112.25   381.5 2106.98
   413.9 2100.69   427.8 2095.75   460.2 2079.57   484.2 2076.18     513 2067.89
   521.1 2067.29   535.4 2067.91   541.2 2069.09   549.2 2073.08   557.2 2083.69
   565.3 2088.72   601.4 2095.69   634.3 2109.25  648.852113.547   677.8  2119.8
   774.2 2131.43   830.5 2140.32  848.092141.581   894.8 2148.84  1012.8 2173.47
#Mann= 7 ,-1 , 0
       0      .1       0     230     .06       0  336.33      .1       0
     513    .045       0   535.4      .1       0  648.85      .1       0
  848.09     .12       0
Bank Sta=513,535.4
XS Rating Curve= 0 ,0
Exp/Cntr(USF)=0,0
Exp/Cntr=0.3,0.1

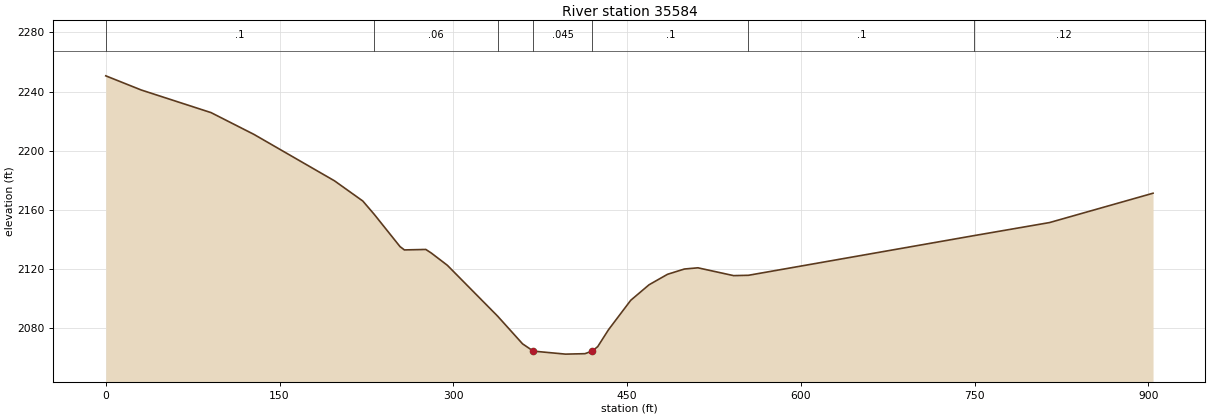
Type RM Length L Ch R = 1 ,35584   ,277,242.7,221.4
XS GIS Cut Line= 3
2436356.60962216569778.4896476232436810.55128156569512.385916249
2437174.48726712  569410.6403719
#Sta/Elev= 30
       0 2250.68    30.6  2241.1    90.9  2225.8     128 2211.04   197.5 2179.66
   221.9 2166.02  231.762157.018     254 2135.22   257.8 2132.96   276.3 2133.28
     281 2130.86   294.9 2122.56  338.262088.194   359.8 2069.46   369.1 2064.53
   396.9  2062.5   413.7  2062.8   420.1 2064.66   424.7 2067.59     434    2079
   453.2 2098.91     469 2109.39   484.9 2116.46   499.5 2120.05   511.2 2120.86
     542 2115.58  554.832115.809  749.61 2142.64   814.7 2151.45   904.1  2171.3
#Mann= 7 ,-1 , 0
       0      .1       0  231.76     .06       0  338.26      .1       0
   369.1    .045       0   420.1      .1       0  554.83      .1       0
  749.61     .12       0
Bank Sta=369.1,420.1
XS Rating Curve= 0 ,0
Exp/Cntr(USF)=0,0
Exp/Cntr=0.3,0.1