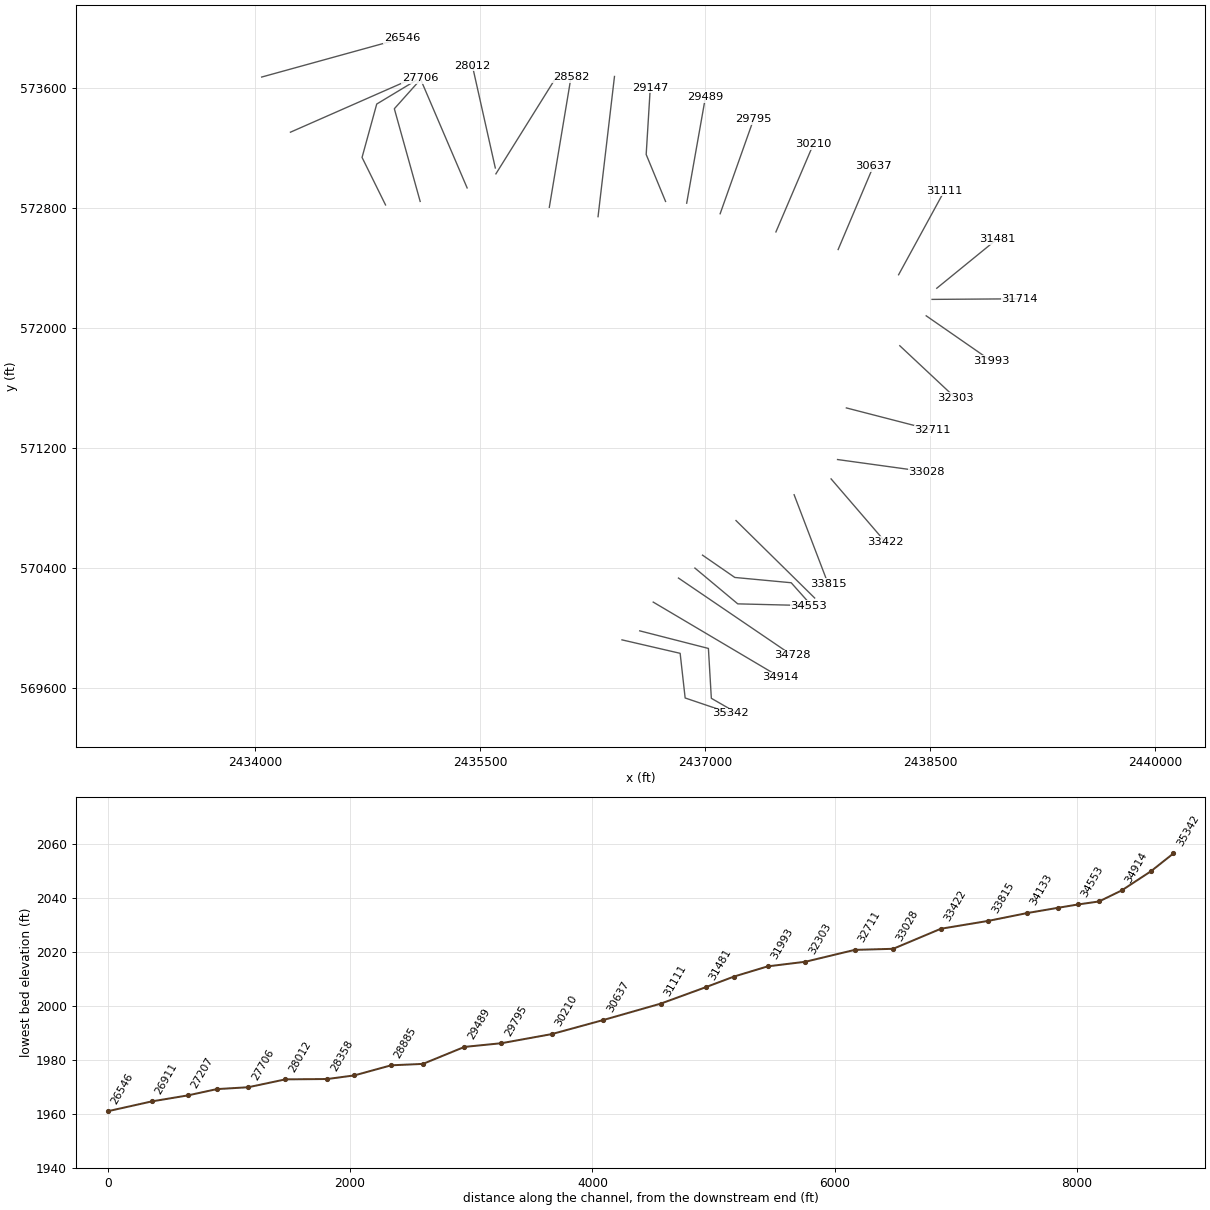
HEC-RAS study THORNCK.prj: THORNCK

--- THORNCK.g01 (geometry) --- (continued)

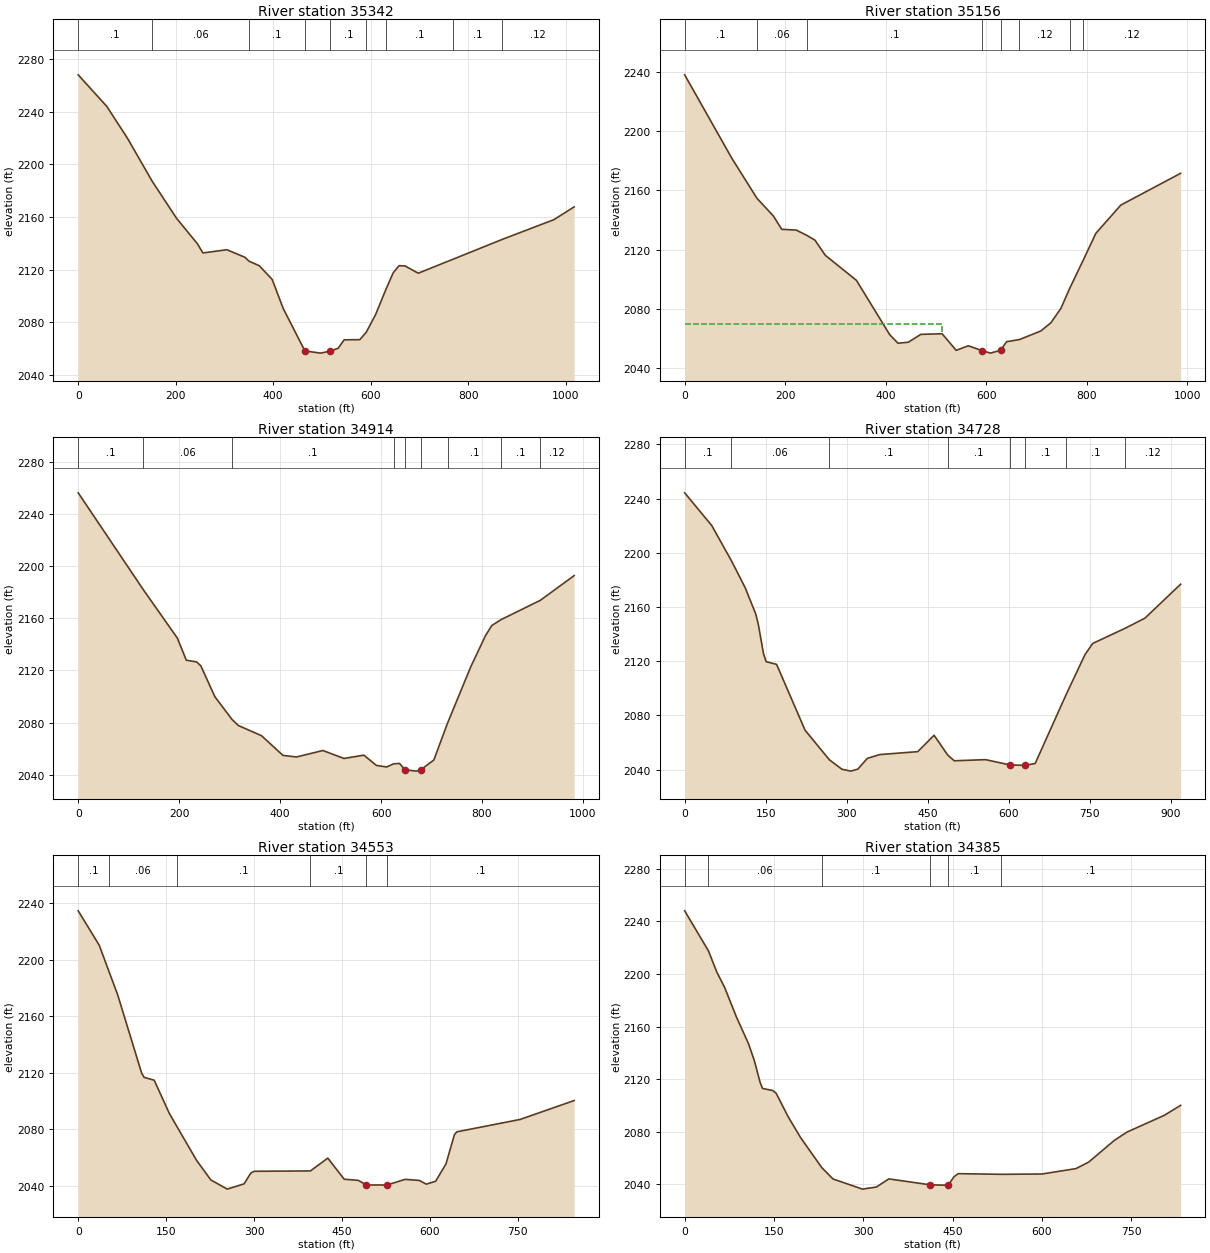
Type RM Length L Ch R = 1 ,35342   ,189.8,185.5,184.3
XS GIS Cut Line= 4
2436445.77110061569921.844974034 2436833.4650621569831.982135278
2436866.84268792569534.1510125432437169.80883001569431.450625393
#Sta/Elev= 30
       0 2267.89    58.8 2243.86   101.5 2219.48  151.392187.367   201.5 2159.14
   244.9 2139.51   255.8 2132.68   305.1 2135.13   342.1 2129.39  350.472126.416
   371.5    2123     398 2112.57   420.8 2090.39   465.1 2058.33   497.3 2056.64
   517.6  2058.2   533.5 2060.37   545.6 2066.74   577.8 2066.86     5912072.482
     610 2085.76  631.342104.954   646.2 2117.54   658.3 2123.02   670.4 2122.84
   697.8 2117.31  769.272127.935  869.982142.953     976 2157.94  1017.6 2167.66
#Mann= 9 ,-1 , 0
       0      .1       0  151.39     .06       0  350.47      .1       0
   465.1    .045       0   517.6      .1       0     591     .12       0
  631.34      .1       0  769.27      .1       0  869.98     .12       0
Bank Sta=465.1,517.6
XS Rating Curve= 0 ,0
Exp/Cntr(USF)=0,0
Exp/Cntr=0.3,0.1

Type RM Length L Ch R = 1 ,35156   ,216.4,241.8,259.1
XS GIS Cut Line= 4
2436564.01400102569981.9807363222437021.86895059569864.582031303
2437041.43540143569531.9523670852437197.96700812569441.946693238
#Sta/Elev= 30
       0 2238.16    93.9 2181.69  143.862154.651   176.5  2142.7     193 2133.72
   221.9 2133.21  243.582129.499   259.1 2126.42   279.7 2116.15   341.6 2099.23
   407.7 2062.54   424.3 2056.71   444.9  2057.4   469.7  2062.7     512  2063.1
   540.1  2051.9   564.1 2054.97   592.2 2051.66   608.2 2050.02   628.3 2051.95
   640.3 2057.75  665.82 2059.19   708.4 2065.01   728.4 2070.55   748.4 2080.32
   765.62093.668  793.232113.216   817.7 2130.96   867.4 2150.09   986.4 2171.58
#Mann= 8 ,-1 , 0
       0      .1       0  143.86     .06       0  243.58      .1       0
   592.2    .045       0   628.3      .1       0  665.82     .12       0
   765.6      .1       0  793.23     .12       0
#XS Ineff= 2 , 0
       0     512    2070               0
Permanent Ineff=
       F       F
Bank Sta=592.2,628.3
XS Rating Curve= 0 ,0
Exp/Cntr(USF)=0,0
Exp/Cntr=0.3,0.1

Type RM Length L Ch R = 1 ,34914   ,187.8,186.5,185.2
XS GIS Cut Line= 2
2436654.01967487570173.731954518  2437499.290351569672.830813107
#Sta/Elev= 30
       0 2256.02  128.322182.217   196.4 2144.76   214.2 2127.83   234.6 2126.53
   242.9 2123.51   270.8 2099.84  304.852082.416   317.3 2077.81   363.1 2070.04
   405.6 2054.95   432.5 2053.72   484.7 2058.68   526.5 2052.59   565.9 2055.13
   590.8 2047.24   611.2 2046.09  624.96 2048.47   636.5 2048.77   647.4 2043.95
   669.6 2042.89   678.3 2043.76   704.6 2051.45  731.662079.604   777.6 2122.72
   806.8 2146.61   819.4 2154.42  838.362159.036  915.462173.687   982.5 2192.63
#Mann= 9 ,-1 , 0
       0      .1       0  128.32     .06       0  304.85      .1       0
  624.96      .1       0   647.4    .045       0   678.3      .1       0
  731.66      .1       0  838.36      .1       0  915.46     .12       0
Bank Sta=647.4,678.3
XS Rating Curve= 0 ,0
Exp/Cntr(USF)=0,0
Exp/Cntr=0.3,0.1

Type RM Length L Ch R = 1 ,34728   ,163.4,174.9,185
XS GIS Cut Line= 2
2436822.29115206570334.1768513762437581.46944451569817.622549296
#Sta/Elev= 30
       0 2244.26    50.1 2220.12   86.292194.307   112.1 2174.16   131.5  2154.9
   136.3 2147.24     146 2125.49   150.8 2119.63   170.2 2117.63   222.9 2069.02
  267.792047.217   291.1 2040.22   307.4 2038.81   320.7  2040.3     338 2048.19
     361 2051.02   431.4 2053.19   461.8 2065.28  486.992050.682   499.1 2046.45
   557.2 2047.29   602.9 2043.33   629.7  2043.1   648.9 2044.42   706.22095.283
   741.1 2124.77   755.5 2133.07  815.81 2144.33   852.3 2151.79   918.2  2176.8
#Mann= 8 ,-1 , 0
       0      .1       0   86.29     .06       0  267.79      .1       0
  486.99      .1       0   602.9    .045       0   629.7      .1       0
   706.2      .1       0  815.81     .12       0
Bank Sta=602.9,629.7
XS Rating Curve= 0 ,0
Exp/Cntr(USF)=0,0
Exp/Cntr=0.3,0.1

Type RM Length L Ch R = 1 ,34553   ,167.6,167.7,164.8
XS GIS Cut Line= 3
2436931.86327675 570400.702784222437217.53345896570161.992084016
 2437691.0415692570150.252213514
#Sta/Elev= 30
       0 2234.79    35.9 2210.38   53.282190.926    67.2 2175.47   108.3 2119.71
   112.6 2116.81   129.6 2114.83   155.2  2091.5  168.752081.729   202.1 2057.91
   226.2  2044.2   254.2 2037.68     283 2041.44   294.3 2049.01     300 2050.31
  396.082050.569   425.7 2059.64   453.7 2044.68   477.7  2043.9   491.5 2040.62
   526.7 2040.63   557.7  2044.6   581.7 2043.85   593.7  2041.2   609.7 2043.26
   627.3 2055.58   641.7 2076.27   645.7 2078.25   753.8 2087.04   845.9 2100.42
#Mann= 6 ,-1 , 0
       0      .1       0   53.28     .06       0  168.75      .1       0
  396.08      .1       0   491.5    .045       0   526.7      .1       0
Bank Sta=491.5,526.7
XS Rating Curve= 0 ,0
Exp/Cntr(USF)=0,0
Exp/Cntr=0.3,0.1

Type RM Length L Ch R = 1 ,34385   ,264.8,252.2,241.3
XS GIS Cut Line= 4
2436982.73604892  570486.79516792437197.96700812570338.090141543
2437573.64286418570302.870530038 2437702.7814397570158.078793849
#Sta/Elev= 30
       0 2247.97   39.962217.519    53.8 2201.58    67.4 2189.42    87.2 2166.97
   107.2 2146.96     117 2134.09   126.7 2117.55   130.7 2112.96   147.9 2111.36
   153.7 2109.23   173.8 2091.43   194.7 2075.57  230.342052.734   249.1 2044.14
   298.7 2036.42   322.1 2038.04   342.9 2044.21   412.4 2039.68   442.4 2039.38
   452.3 2045.81   459.4 2048.18  531.942047.675     600 2047.91   657.2 2052.02
   678.7 2057.03   721.5 2073.47   742.9  2079.8   805.3 2092.48   832.9  2100.1
#Mann= 6 ,-1 , 0
       0      .1       0   39.96     .06       0  230.34      .1       0
   412.4    .045       0   442.4      .1       0  531.94      .1       0
Bank Sta=412.4,442.4
XS Rating Curve= 0 ,0
Exp/Cntr(USF)=0,0
Exp/Cntr=0.3,0.1

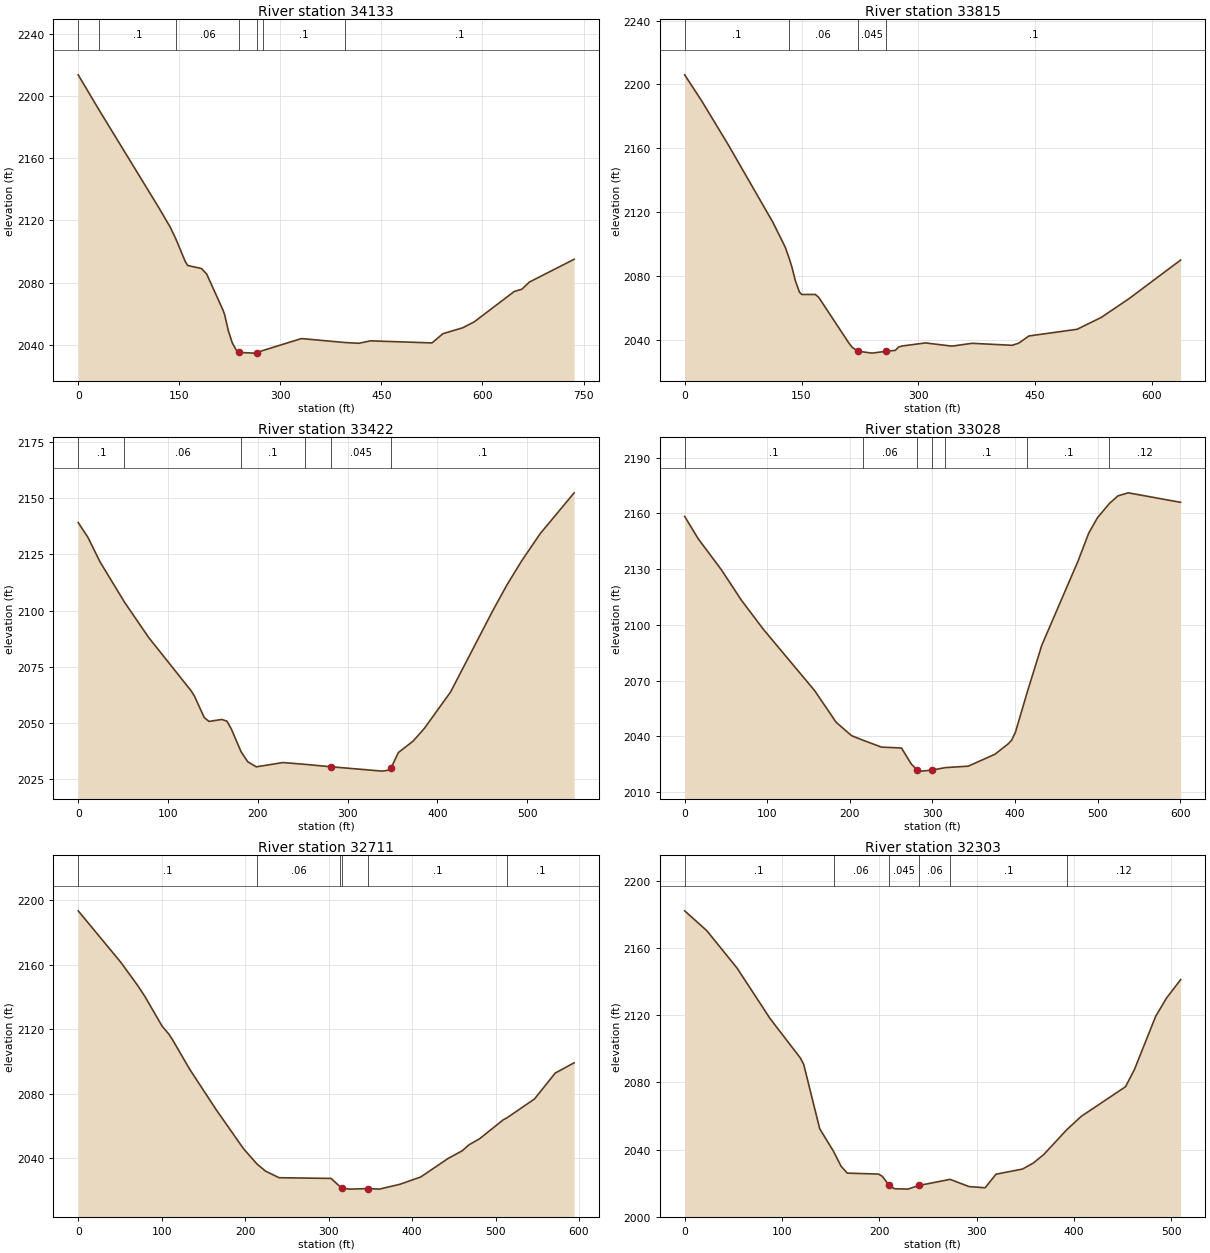
Type RM Length L Ch R = 1 ,34133   ,327.8,318.4,312.2
XS GIS Cut Line= 2
2437205.79358846570717.6792877692437730.17447087570201.124985689
#Sta/Elev= 30
       0 2213.88   30.412191.619     120 2127.99   136.4 2115.82  145.062107.969
   158.8 2093.62   162.4 2091.01   183.1 2089.01   190.7 2085.46     215 2062.15
   217.3  2059.3     223 2048.68   228.7 2041.09   234.4 2036.56   238.7 2034.93
   261.4 2034.49   265.5 2034.82  273.972036.157   331.3 2043.87  395.752041.326
   416.8 2040.85   433.9 2042.41   525.1 2041.07   541.4 2047.04   570.7 2050.83
   587.7 2054.62   647.2 2074.23   658.5  2075.7   669.7 2080.31   736.1 2094.99
#Mann= 7 ,-1 , 0
       0      .1       0   30.41      .1       0  145.06     .06       0
   238.7    .045       0   265.5     .06       0  273.97      .1       0
  395.75      .1       0
Bank Sta=238.7,265.5
XS Rating Curve= 0 ,0
Exp/Cntr(USF)=0,0
Exp/Cntr=0.3,0.1

Type RM Length L Ch R = 1 ,33815   ,367.6,392.4,397.9
XS GIS Cut Line= 2
2437593.20931502570889.8640551292437820.18014472570295.043949703
#Sta/Elev= 30
       0    2206    22.2  2189.4    56.4  2161.8   113.4 2113.45   129.2 2097.91
  134.02 2091.23   137.8 2085.33     142  2077.1   147.5 2069.64   150.6 2068.34
   167.7 2068.38     172 2066.61   210.5 2038.16   214.8 2035.39   221.9 2032.85
   240.5  2031.6     259  2032.8   270.5 2033.34   274.5  2035.4     279 2036.05
     309    2038   343.2 2035.98   368.9 2037.76   420.3  2036.5   428.8 2037.82
   441.9 2042.35   503.8 2046.55   534.8 2053.97   570.1 2065.61   636.7 2089.92
#Mann= 4 ,-1 , 0
       0      .1       0  134.02     .06       0   221.9    .045       0
     259      .1       0
Bank Sta=221.9,259
XS Rating Curve= 0 ,0
Exp/Cntr(USF)=0,0
Exp/Cntr=0.3,0.1

Type RM Length L Ch R = 1 ,33422   ,361.1,393.9,406.1
XS GIS Cut Line= 2
2437839.74659555570995.5228896452438199.76929094570576.800841747
#Sta/Elev= 30
       0 2139.11    10.9 2132.48    24.2 2121.72    51.5 2103.78    78.4 2088.09
   125.9 2064.28   129.7 2061.81   140.3  2052.5   145.6 2050.76   159.9 2051.64
   165.6 2050.88   170.4 2047.48  181.342037.293   188.8 2032.83   198.3 2030.59
     228 2032.49  252.642031.687   281.9  2030.6   338.6 2028.68     346 2029.14
   348.3 2030.12   356.5 2036.94   372.9 2042.01   385.2 2047.56   414.6 2063.84
     462 2100.27   477.5  2111.5   493.7 2122.05   514.4 2134.19   552.2 2152.32
#Mann= 6 ,-1 , 0
       0      .1       0    51.5     .06       0  181.34      .1       0
  252.64      .1       0   281.9    .045       0   348.3      .1       0
Bank Sta=281.9,348.3
XS Rating Curve= 0 ,0
Exp/Cntr(USF)=0,0
Exp/Cntr=0.3,0.1

Type RM Length L Ch R = 1 ,33028   ,318.5,317.1,315.8
XS GIS Cut Line= 2
2437882.79278739571124.6614651652438477.61289282571042.482371652
#Sta/Elev= 30
       0 2158.32    16.2 2146.42    44.5 2129.56    68.7 2113.22    95.4  2097.5
   157.5 2064.48   183.3 2047.56     202 2040.34  216.272037.799   238.3 2034.16
   262.5 2033.68   274.6 2024.91   281.7 2021.81   286.7 2021.23   299.32021.787
  315.612023.117   343.3 2023.89   375.7 2030.31   391.7 2035.91   395.8 2037.84
   400.5 2042.18  414.96    2064   432.4 2088.98   476.5 2134.49   489.2 2149.27
   499.8  2157.6   514.32165.304   524.7 2169.39   537.1 2171.01   600.5  2165.9
#Mann= 7 ,-1 , 0
       0      .1       0  216.27     .06       0   281.7    .045       0
   299.3     .06       0  315.61      .1       0  414.96      .1       0
   514.3     .12       0
Bank Sta=281.7,299.3
XS Rating Curve= 0 ,0
Exp/Cntr(USF)=0,0
Exp/Cntr=0.3,0.1

Type RM Length L Ch R = 1 ,32711   ,417.3,407.9,396.8
XS GIS Cut Line= 2
 2437941.4921399571469.0309998852438516.74579449571320.325973529
#Sta/Elev= 30
       0  2193.4      51 2161.51    71.6 2146.87    79.9 2140.29   100.6 2121.84
   108.8 2116.83     113 2113.48   133.6 2095.14   165.2 2070.18     198 2045.91
   214.32036.356   224.5 2031.98   240.7  2027.9     303 2027.47  314.042022.211
   316.2 2021.39     326 2020.83   347.4 2021.18   360.8 2020.83   385.6 2023.86
   410.4 2028.36   443.4 2039.92     460 2044.57   468.2 2048.32   480.6 2051.94
   509.5 2063.91  513.522064.952   546.7 2076.74   571.5 2092.78   594.2 2099.18
#Mann= 6 ,-1 , 0
       0      .1       0   214.3     .06       0  314.04      .1       0
   316.2    .045       0   347.4      .1       0  513.52      .1       0
Bank Sta=316.2,347.4
XS Rating Curve= 0 ,0
Exp/Cntr(USF)=0,0
Exp/Cntr=0.3,0.1

Type RM Length L Ch R = 1 ,32303   ,301.1,310.2,311.1
XS GIS Cut Line= 2
2438297.60154513571883.8397576162438669.36411102571535.556932729
#Sta/Elev= 30
       0 2182.08    22.7 2170.28    53.8 2148.01    87.7 2117.97   118.9 2094.42
   122.3  2090.6   138.7 2052.37  152.932038.859   160.6 2030.09     167 2025.94
     199 2025.39     203 2024.06   209.9 2018.77   215.4 2016.67   229.2 2016.42
   240.5 2018.59  272.622022.229   292.1 2017.94   308.6 2017.23   319.8 2025.31
     347 2028.37   357.9 2031.86   368.9 2037.05   392.32051.692   407.2 2059.68
   452.8 2077.38     462 2087.65   483.8  2119.3   494.9 2130.13   509.4 2141.12
#Mann= 6 ,-1 , 0
       0      .1       0  152.93     .06       0   209.9    .045       0
   240.5     .06       0  272.62      .1       0   392.3     .12       0
Bank Sta=209.9,240.5
XS Rating Curve= 0 ,0
Exp/Cntr(USF)=0,0
Exp/Cntr=0.3,0.1

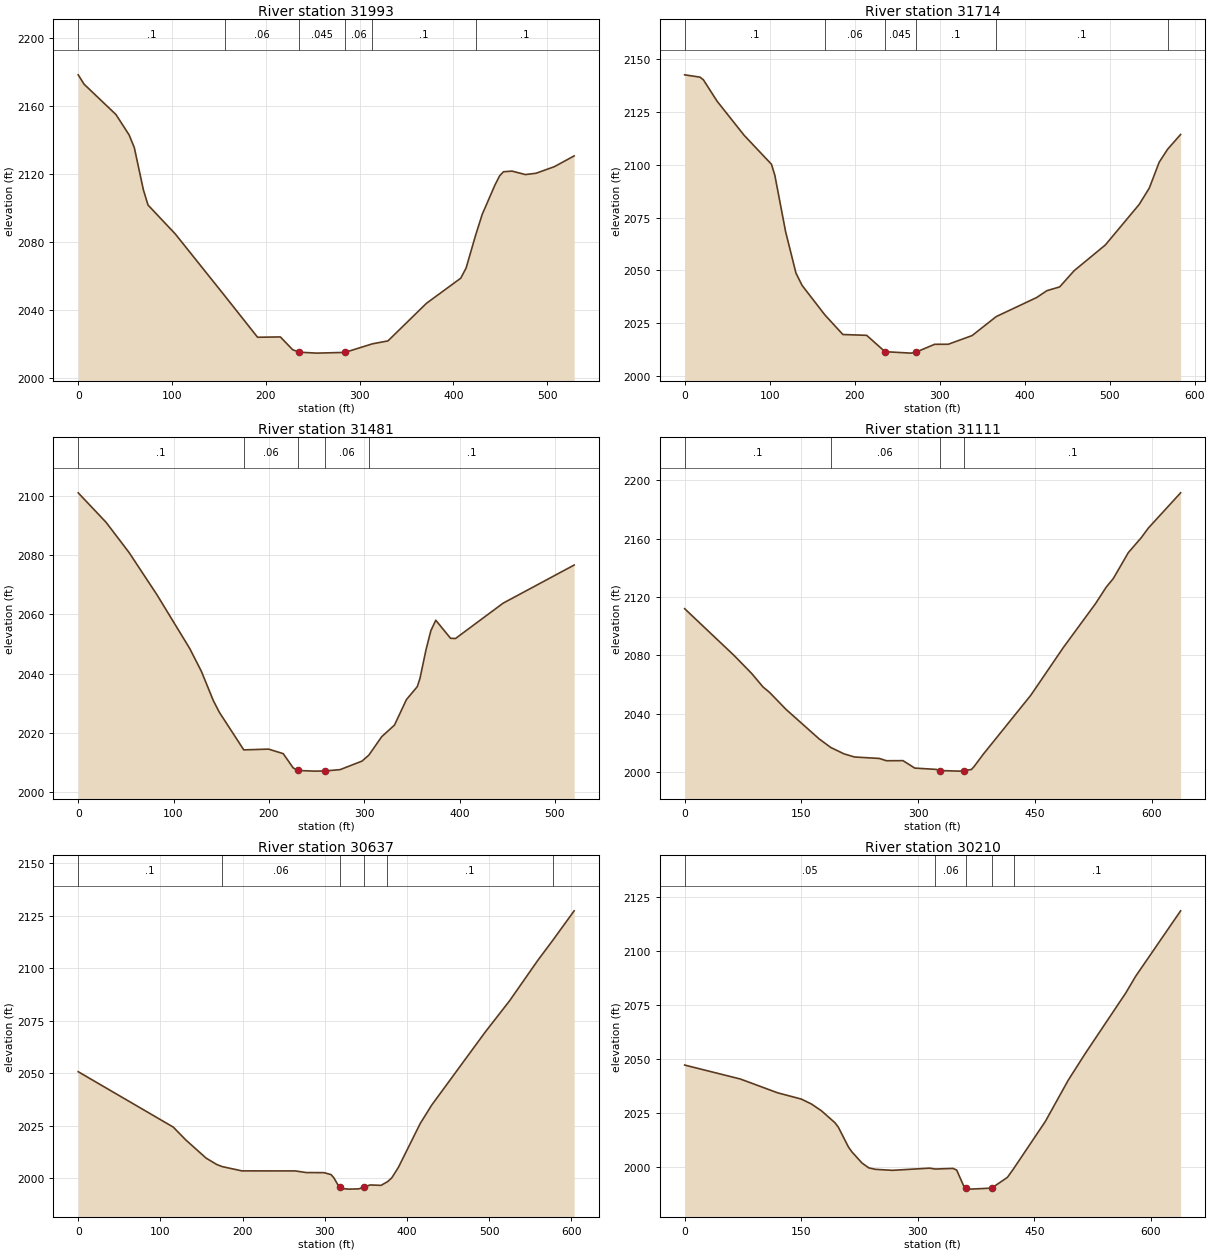
Type RM Length L Ch R = 1 ,31993   ,257,279.1,289.5
XS GIS Cut Line= 2
2438473.69960265572083.4175561472438908.07481122571782.094213267
#Sta/Elev= 30
       0 2178.29     6.2 2172.82    40.3 2154.91    54.3 2142.94    59.8 2135.52
    69.5 2110.67    74.4 2101.78   103.6 2084.69  156.622048.134   191.2 2024.05
   215.5 2024.24   228.7 2016.69   235.8 2015.26   254.5 2014.72   284.42015.153
  313.612020.189   330.2  2021.9   371.3 2044.02   407.8 2058.76   413.5 2064.74
  423.682084.068   430.7  2096.3   444.3 2113.57   449.2 2118.88   453.3 2121.31
   462.4 2121.71   476.7 2119.67   488.1 2120.44   507.6 2124.31   528.7 2130.64
#Mann= 6 ,-1 , 0
       0      .1       0  156.62     .06       0   235.8    .045       0
   284.4     .06       0  313.61      .1       0  423.68      .1       0
Bank Sta=235.8,284.4
XS Rating Curve= 0 ,0
Exp/Cntr(USF)=0,0
Exp/Cntr=0.3,0.1

Type RM Length L Ch R = 1 ,31714   ,220,233,246.7
XS GIS Cut Line= 2
2438512.83250433 572192.989680832439095.91273925572196.902970998
#Sta/Elev= 30
       0 2142.48      18 2141.39      22 2140.13    38.2 2129.96      70 2113.85
     102 2100.23     106 2095.03   118.7 2068.27   130.8  2048.8     138 2042.96
  164.872028.976     186 2019.72     214 2019.33   235.5 2011.61   265.9 2010.92
   271.8 2011.35   293.9  2015.1   309.9 2015.11   337.9 2019.21  366.322028.197
   413.9 2037.22   425.9 2040.45   440.9 2042.23   457.9 2049.88   494.6 2062.05
   534.4 2081.22   546.3 2088.97   557.9 2101.16  567.77 2107.28   583.1 2114.29
#Mann= 6 ,-1 , 0
       0      .1       0  164.87     .06       0   235.5    .045       0
   271.8      .1       0  366.32      .1       0  567.77     .12       0
Bank Sta=235.5,271.8
XS Rating Curve= 0 ,0
Exp/Cntr(USF)=0,0
Exp/Cntr=0.3,0.1

Type RM Length L Ch R = 1 ,31481   ,363.3,370.4,378.1
XS GIS Cut Line= 2
2438544.13882566572267.3421940082438947.20771289572596.058568059
#Sta/Elev= 30
       0 2101.14    29.2 2091.17    53.3 2080.96    82.7 2066.59     117 2048.44
   129.2 2040.72   141.8 2030.76     148 2026.89  173.642014.158   199.6 2014.42
     215 2012.89   225.4 2008.08   230.4 2007.19   247.5 2006.97   258.8 2007.02
   274.7 2007.48   297.6 2010.36  304.822012.392   318.3 2018.63   331.7 2022.56
   344.2 2031.17   355.6 2035.56   358.4 2038.33   364.7 2047.98   369.8 2054.47
     375 2058.03   390.5 2051.91   395.7 2051.85   445.6  2063.8   520.1  2076.7
#Mann= 5 ,-1 , 0
       0      .1       0  173.64     .06       0   230.4    .045       0
   258.8     .06       0  304.82      .1       0
Bank Sta=230.4,258.8
XS Rating Curve= 0 ,0
Exp/Cntr(USF)=0,0
Exp/Cntr=0.3,0.1

Type RM Length L Ch R = 1 ,31111   ,471.9,473.5,476.3
XS GIS Cut Line= 2
2438289.77496479572357.3478678562438595.01159784572916.948361775
#Sta/Elev= 30
       0 2111.99    63.4 2080.07    86.2 2067.65   100.7 2058.45   108.9 2054.85
   130.2 2043.16   172.7 2022.99  187.812017.061   204.6 2012.74   218.3 2010.56
   250.2 2009.56   259.3    2008   280.6 2008.06   295.7 2002.97   323.1 2002.08
   327.7 2001.28     353 2000.89   359.5 2001.22   368.6 2002.03   371.9 2003.98
   383.7 2012.41   444.9 2052.83   486.6  2085.4   528.1 2115.52   541.7 2126.69
   550.9 2132.65   570.2 2150.37   586.9 2160.63     596 2167.22   637.4 2191.27
#Mann= 4 ,-1 , 0
       0      .1       0  187.81     .06       0   327.7    .045       0
   359.5      .1       0
Bank Sta=327.7,359.5
XS Rating Curve= 0 ,0
Exp/Cntr(USF)=0,0
Exp/Cntr=0.3,0.1

Type RM Length L Ch R = 1 ,30637   ,426.8,426.8,426.5
XS GIS Cut Line= 2
2437886.70607756572525.619345048 2438121.5034876573081.306548801
#Sta/Elev= 30
       0 2050.76   115.6 2024.37   130.9 2018.24   155.6 2009.58   168.6 2006.53
  175.112005.549     199 2003.51   264.2 2003.48   277.2 2002.71   298.8 2002.66
   307.6 2001.73     311 2000.19   316.3  1996.6  318.34 1995.76   320.6 1995.08
   329.3 1994.81   341.5 1994.95   347.6 1995.89   355.3  1996.8   368.4  1996.6
   376.21998.328   381.4 2000.15   389.5 2005.18   416.1 2026.11     430 2034.84
   494.7 2069.43   524.7 2084.52   559.4 2103.98   577.32113.352   603.3 2127.41
#Mann= 6 ,-1 , 0
       0      .1       0  175.11     .06       0  318.34    .045       0
   347.6     .06       0   376.2      .1       0   577.3      .1       0
Bank Sta=318.34,347.6
XS Rating Curve= 0 ,0
Exp/Cntr(USF)=0,0
Exp/Cntr=0.3,0.1

Type RM Length L Ch R = 1 ,30210   ,413.6,415.1,416.8
XS GIS Cut Line= 2
2437471.89731983572643.0180500672437722.34789054573230.011575157
#Sta/Elev= 30
       0 2046.99    71.7 2040.53   119.6 2034.15     150 2031.26     163    2029
     176 2025.83   193.4  2020.3   197.8 2018.21   210.8 2009.04   215.2 2006.81
   228.2 2001.65   236.9 1999.41   245.6 1998.73   267.4 1998.27   315.2 1999.28
  322.531998.866   345.2 1999.16     350  1998.4   358.7 1991.34     362 1990.08
   367.4 1989.57     395 1990.04   415.3 1995.01  423.171998.969     464 2020.83
   493.5 2039.94   515.2 2052.19   567.7 2080.41   580.4 2088.12   638.2 2118.38
#Mann= 5 ,-1 , 0
       0     .05       0  322.53     .06       0     362    .045       0
     395     .06       0  423.17      .1       0
Bank Sta=362,395
XS Rating Curve= 0 ,0
Exp/Cntr(USF)=0,0
Exp/Cntr=0.3,0.1

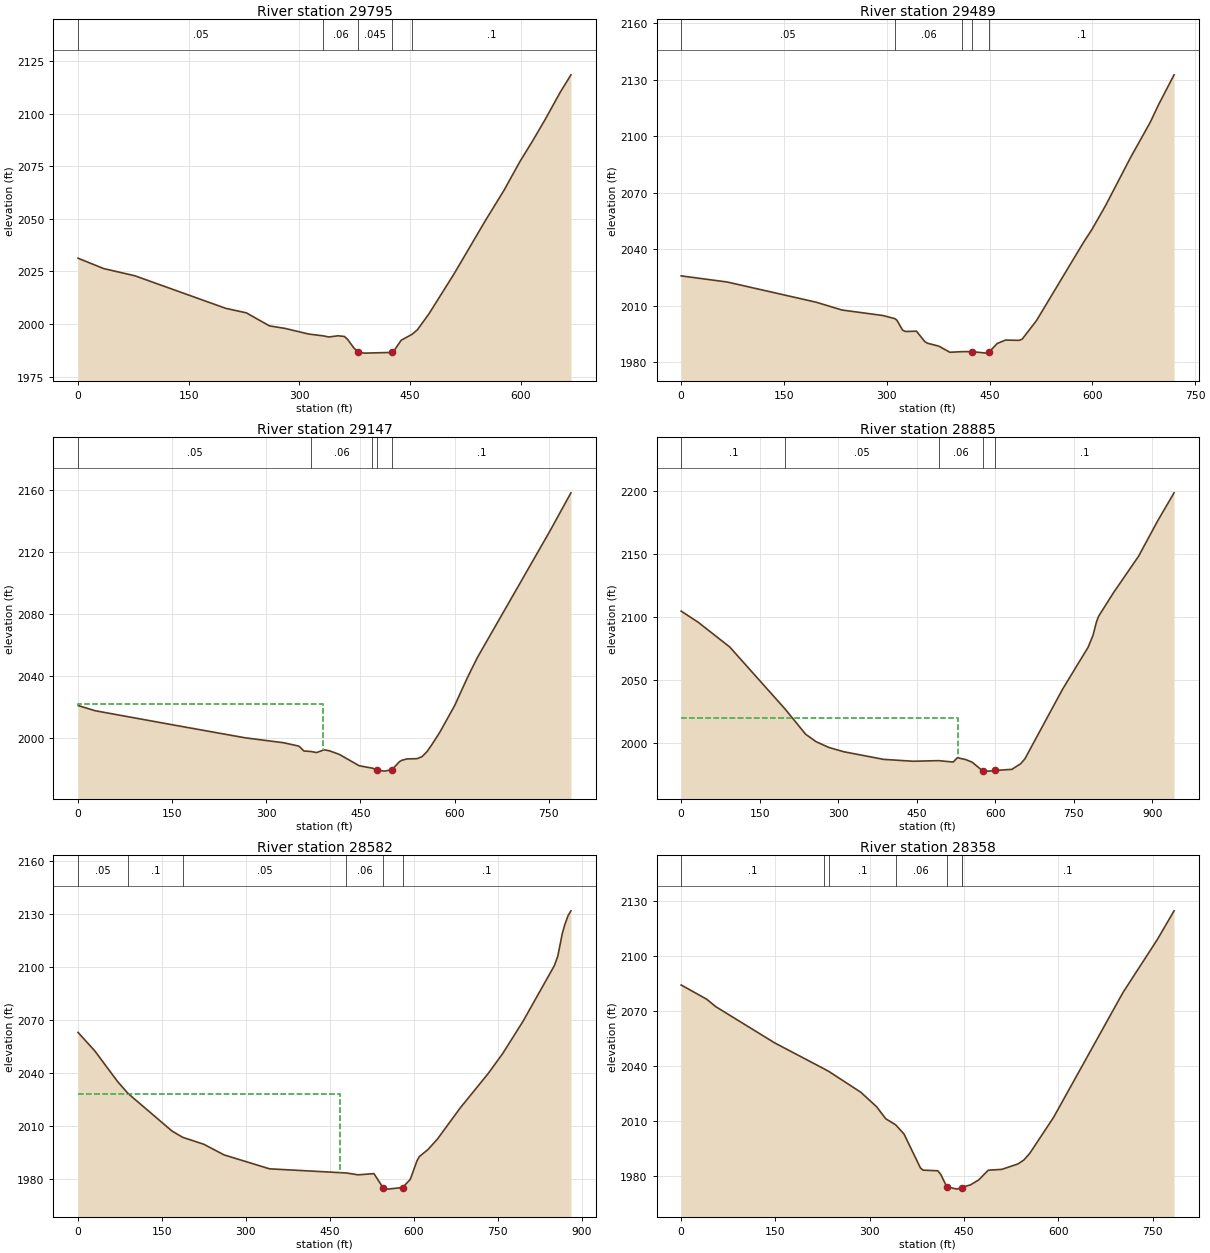
Type RM Length L Ch R = 1 ,29795   ,305.1,306,309.1
XS GIS Cut Line= 2
2437100.13475394572764.3300452522437323.19229347573394.369762183
#Sta/Elev= 30
       0 2031.32    34.6  2026.4      77 2022.97   200.2 2007.49   228.3 2005.33
   259.5 1999.15   280.7 1997.94   312.9 1995.25  332.751994.382   340.1 1993.87
   352.8 1994.44   361.3 1994.09   365.5 1992.74     374 1988.65     380 1986.67
   388.1 1986.19   425.7 1986.52   429.2  1987.7   438.2 1992.32  452.641995.092
   460.2 1997.28   475.9 2004.91   509.8 2023.82   552.2  2049.1   577.7 2063.64
   598.9 2077.09   615.9 2086.78   633.5 2097.31     654  2110.3   668.4  2118.5
#Mann= 5 ,-1 , 0
       0     .05       0  332.75     .06       0     380    .045       0
   425.7     .06       0  452.64      .1       0
Bank Sta=380,425.7
XS Rating Curve= 0 ,0
Exp/Cntr(USF)=0,0
Exp/Cntr=0.3,0.1

Type RM Length L Ch R = 1 ,29489   ,340.3,342,344.1
XS GIS Cut Line= 2
2436877.07721441572834.7692682632437002.30249976573543.074788539
#Sta/Elev= 30
       0 2025.86    67.2  2022.6   197.2 2011.85   234.8 2007.71   294.6 2004.78
     3122003.114   314.9 2002.27   323.1 1997.05   327.1 1996.31   343.4 1996.47
   355.5 1990.95   359.6 1990.05   375.9 1988.54   392.1 1985.27  409.55 1985.59
   424.6 1985.62   444.9 1984.81   449.3 1985.35   461.2 1989.92   473.3 1991.76
   493.4 1991.59   497.7 1992.27   518.4 2002.03   586.8 2043.45   599.3 2050.44
   619.6 2063.39   655.8 2088.76   684.6 2107.53   696.7 2116.84   719.3  2132.7
#Mann= 5 ,-1 , 0
       0     .05       0     312     .06       0  409.55      .1       0
   424.6    .045       0   449.3      .1       0
Bank Sta=424.6,449.3
XS Rating Curve= 0 ,0
Exp/Cntr(USF)=0,0
Exp/Cntr=0.3,0.1

Type RM Length L Ch R = 1 ,29147   ,263.4,262.4,261.5
XS GIS Cut Line= 3
2436736.19876838572846.5091387652436607.06019286573159.572352146
2436634.45322404573605.687431215
#Sta/Elev= 30
       0 2020.89    27.3 2017.51   152.9 2008.26   266.5 2000.02   328.3  1996.8
     352 1994.65     360 1991.51  371.22 1991.19   380.1 1990.49   392.1 1992.26
   400.3 1991.68   416.1 1989.38   448.2 1981.97  469.171980.423   476.7 1979.25
   488.2 1978.51   500.3 1979.41   512.3 1984.66   516.3 1985.53   524.3 1986.39
   540.3 1986.56   548.4  1987.9   556.4 1991.21   564.4 1995.93   576.4 2003.49
   600.4 2020.97   620.5 2038.83   636.5 2051.91   751.4 2133.08   785.6 2158.25
#Mann= 5 ,-1 , 0
       0     .05       0  371.22     .06       0  469.17      .1       0
   476.7    .045       0   500.3      .1       0
#XS Ineff= 2 , 0
          390.25 2021.66
Permanent Ineff=
       F       F
Bank Sta=476.7,500.3
XS Rating Curve= 0 ,0
Exp/Cntr(USF)=0,0
Exp/Cntr=0.3,0.1

Type RM Length L Ch R = 1 ,28885   ,304,302.8,301.8
XS GIS Cut Line= 2
2436286.17039915572744.7635944162436395.74252383573680.039944394
#Sta/Elev= 30
       0 2104.81    32.4 2096.03    92.8 2076.39  199.132026.943   237.8 2007.23
   257.9 2001.28   282.5 1996.72     311 1993.32   386.8 1987.31   443.1 1985.82
  491.92  1986.3   519.7  1985.2   527.7 1988.64   543.8 1987.11   555.9  1985.1
     576 1978.22   588.1 1977.99     5991978.513   631.8 1979.39   648.5 1983.81
   656.6 1987.66     729 2043.15   777.4 2076.11   786.8 2085.58   793.5 2096.33
   797.5 2100.72   825.7 2119.24     874  2148.4   910.3 2176.29   941.7 2198.58
#Mann= 5 ,-1 , 0
       0      .1       0  199.13     .05       0  491.92     .06       0
     576    .045       0     599      .1       0
#XS Ineff= 2 , 0
          528.01 2020.26
Permanent Ineff=
       F       F
Bank Sta=576,599
XS Rating Curve= 0 ,0
Exp/Cntr(USF)=0,0
Exp/Cntr=0.3,0.1

Type RM Length L Ch R = 1 ,28582   ,230.3,223.9,217.3
XS GIS Cut Line= 2
2435961.36731526572807.3762370922436106.15905145573676.126654226
#Sta/Elev= 30
       0 2062.97      30 2052.48    70.5 2035.21   89.46 2028.36   167.8 2007.15
  186.992003.568   224.6 1999.66   261.1 1993.61   342.2 1985.74  479.591983.392
   500.3 1982.34   528.7 1983.03   544.9 1975.09     553 1974.25   579.8 1975.15
   593.6 1979.75   605.7 1990.38   609.8 1992.68     625  1996.6   642.1 2002.57
   682.8 2020.21   732.7 2039.65   758.9 2051.08   795.3 2069.39   850.9 2100.69
   857.1 2106.03   865.2 2118.87   869.3 2123.57   875.6  2129.1   880.7  2131.8
#Mann= 6 ,-1 , 0
       0     .05       0   89.46      .1       0  186.99     .05       0
  479.59     .06       0   544.9    .045       0   579.8      .1       0
#XS Ineff= 2 , 0
          467.35 2027.99
Permanent Ineff=
       F       F
Bank Sta=544.9,579.8
XS Rating Curve= 0 ,0
Exp/Cntr(USF)=0,0
Exp/Cntr=0.3,0.1

Type RM Length L Ch R = 1 ,28358   ,331.9,345.8,360.5
XS GIS Cut Line= 2
2435605.25791004573030.4337766262436020.06666777573695.693105063
#Sta/Elev= 30
       0 2084.22    40.9 2076.38    54.8 2072.44     149 2052.59  227.312038.488
  235.16 2037.01   285.7 2025.74   310.9 2017.81   325.4 2011.27  341.212007.949
   354.4 2002.98   380.6 1984.45   384.7 1983.26   408.3  1982.9     413 1980.87
   422.4 1974.23   438.6  1972.9     446 1973.73  447.25 1973.98   460.1 1975.19
   473.5 1977.98   488.4 1983.21     510 1983.68   535.5  1986.6     545 1988.75
   554.4 1992.38   592.5 2012.12   702.8 2080.13   757.1 2108.84     784 2124.65
#Mann= 7 ,-1 , 0
       0      .1       0  227.31     .05       0  235.16      .1       0
  341.21     .06       0   422.4    .045       0     446     .06       0
  447.25      .1       0
Bank Sta=422.4,446
XS Rating Curve= 0 ,0
Exp/Cntr(USF)=0,0
Exp/Cntr=0.3,0.1

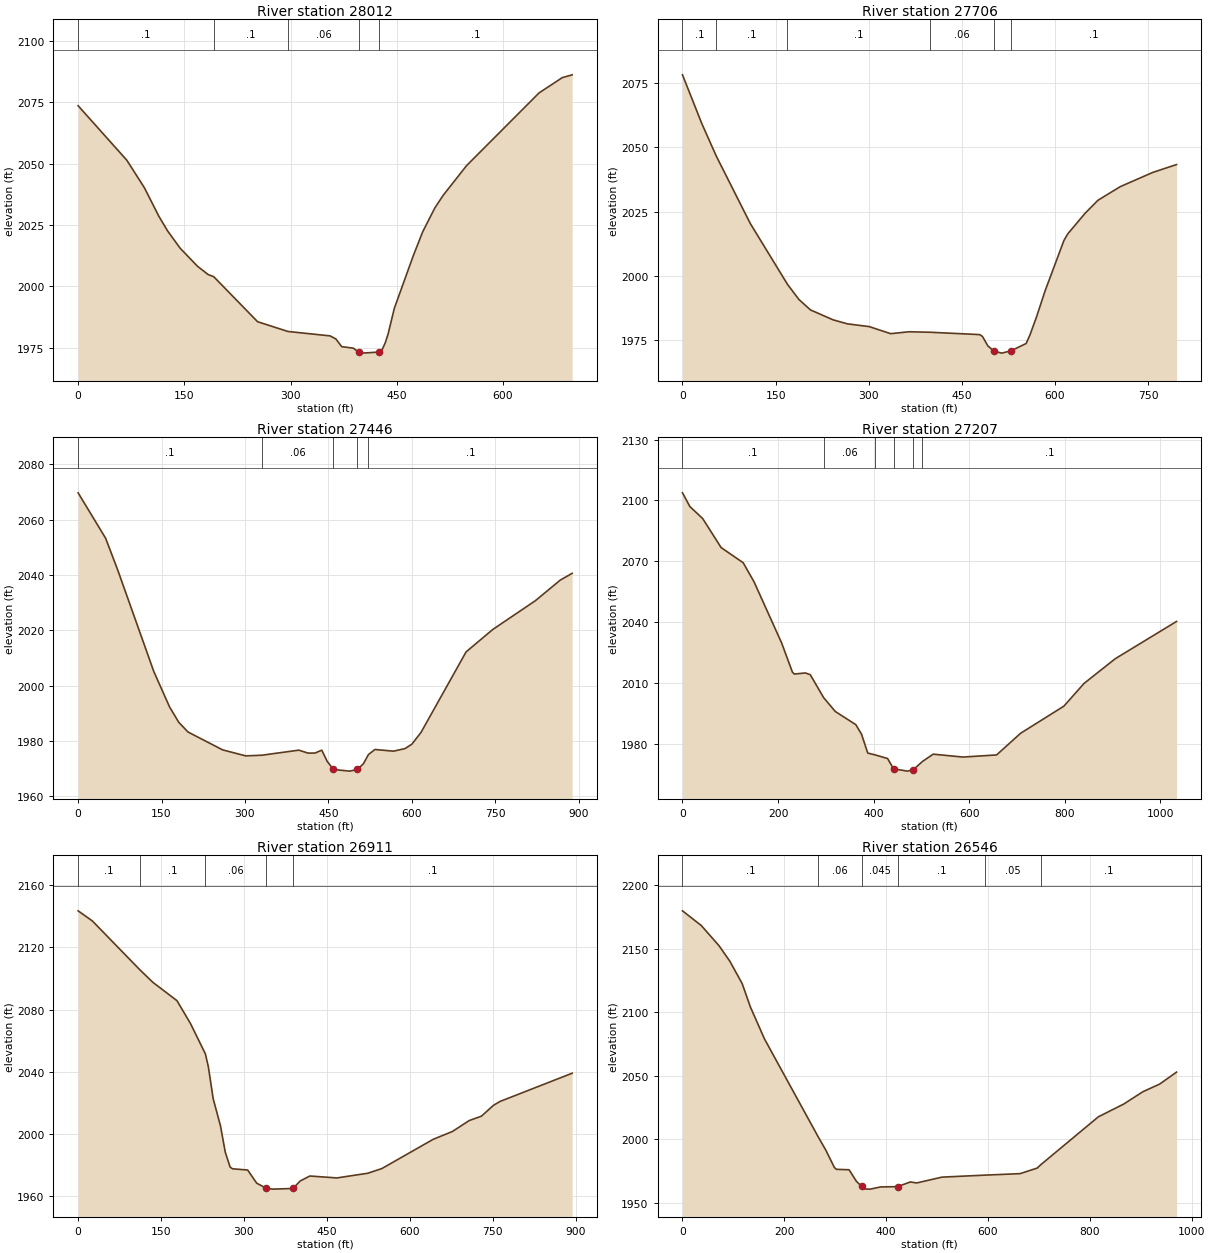
Type RM Length L Ch R = 1 ,28012   ,303.4,306.2,310.2
XS GIS Cut Line= 2
2435601.34461987573069.5666782992435448.72630335573750.479167404
#Sta/Elev= 30
       0 2073.64      69 2051.34    93.6  2040.2   114.1 2028.54   126.4 2022.59
   144.1 2015.55   168.7 2008.17   183.8 2004.77   191.5 2003.95   253.5 1985.58
  296.291981.604   355.9  1979.8   364.1 1978.54   372.3 1975.41   388.7  1974.8
   396.4 1973.15     401 1972.77   425.6 1973.21   429.7 1974.36   433.8 1976.95
   437.9 1980.64   446.6 1991.01   473.4 2012.47   486.8  2022.3   503.9 2031.99
   515.8 2037.17   548.6 2049.19     651 2078.84   683.8 2085.08   697.8 2086.23
#Mann= 5 ,-1 , 0
       0      .1       0   191.5      .1       0  296.29     .06       0
   396.4    .045       0   425.6      .1       0
Bank Sta=396.4,425.6
XS Rating Curve= 0 ,0
Exp/Cntr(USF)=0,0
Exp/Cntr=0.3,0.1

Type RM Length L Ch R = 1 ,27706   ,263.3,260,256.3
XS GIS Cut Line= 2
2435413.50669185572936.5148126122435100.44347846573668.300073892
#Sta/Elev= 30
       0 2078.25    30.9 2059.39   54.172046.736   109.2 2020.35  169.161996.646
   187.5 1990.76   206.2 1986.68   242.8  1982.8   265.8 1981.25   300.7 1980.19
   335.4 1977.43   364.7 1978.17  399.151977.981     479 1977.06   483.3 1976.34
     492 1972.66   501.8  1970.6   514.4 1969.85   529.2 1970.75   553.6 1973.59
   559.7 1976.88   570.3 1983.91     584    1994   614.5 2013.72   620.6 2016.27
   648.6 2024.32   669.4  2029.4   705.2 2034.69   757.7 2040.24   795.9  2043.3
#Mann= 6 ,-1 , 0
       0      .1       0   54.17      .1       0  169.16      .1       0
  399.15     .06       0   501.8    .045       0   529.2      .1       0
Bank Sta=501.8,529.2
XS Rating Curve= 0 ,0
Exp/Cntr(USF)=0,0
Exp/Cntr=0.3,0.1

Type RM Length L Ch R = 1 ,27446   ,253.9,239.2,226.8
XS GIS Cut Line= 3
2435100.44347846572846.509138765 2434928.2587111573464.808985194
2435092.61689813573648.733623055
#Sta/Elev= 30
       0 2069.72    49.5  2053.3    71.2 2041.86   136.1 2005.16   164.4 1992.39
     181 1986.79   197.7 1983.28   259.9 1976.83   301.4 1974.66  330.561974.901
   396.9 1976.73   413.5 1975.66     426 1975.68   438.2 1976.72   447.9  1972.7
   459.2 1969.74   488.3 1969.15   502.3 1969.74   513.2 1971.85  522.13 1975.14
   533.9 1976.97   567.2 1976.36   587.9 1977.29   600.4 1978.92   616.8 1983.18
   697.8 2012.25   745.9 2020.36   822.4 2030.74   867.2 2038.19   888.5 2040.63
#Mann= 5 ,-1 , 0
       0      .1       0  330.56     .06       0   459.2    .045       0
   502.3     .06       0  522.13      .1       0
Bank Sta=459.2,502.3
XS Rating Curve= 0 ,0
Exp/Cntr(USF)=0,0
Exp/Cntr=0.3,0.1

Type RM Length L Ch R = 1 ,27207   ,315.5,295.5,269.1
XS GIS Cut Line= 4
 2434869.5593586572823.029397761 2434713.0277519 573140.00590131
2434810.86000609573496.1153065322435076.96373746 573656.56020339
#Sta/Elev= 30
       0 2103.76    15.5    2097    42.3 2091.09    80.8 2076.82     127 2069.36
   149.9 2059.88   207.3 2029.96   230.1 2015.47   234.1 2014.59     257 2015.13
   267.3 2014.28  295.322002.965   319.7 1996.17   362.7 1989.67   374.6 1984.98
   387.6 1975.71  403.761974.759   429.1 1973.02   441.6 1967.96   470.6 1966.82
     483 1967.53  501.93 1971.55   524.5 1975.17   586.7 1973.74   657.2 1974.79
   707.4 1985.45     798  1998.8     840 2009.95   905.4 2022.13  1033.6 2040.47
#Mann= 6 ,-1 , 0
       0      .1       0  295.32     .06       0  403.76     .06       0
   441.6    .045       0     483     .06       0  501.93      .1       0
Bank Sta=441.6,483
XS Rating Curve= 0 ,0
Exp/Cntr(USF)=0,0
Exp/Cntr=0.3,0.1

Type RM Length L Ch R = 1 ,26911   ,368.8,365.6,355.7
XS GIS Cut Line= 2
 2434235.6063515573308.2773785032435053.48399646573668.300073892
#Sta/Elev= 30
       0 2143.55    25.9    2137  111.882105.571   135.1 2097.61   178.8 2085.79
   203.5 2070.91  230.262051.516   235.6 2043.22   244.3 2022.73   257.5 2005.31
   266.2 1988.33   274.9 1978.83   279.3 1977.69   306.7 1976.89     323 1968.44
   340.5 1965.15   352.2 1964.61   388.6 1965.03   401.7 1969.84   419.1 1973.04
   468.1 1971.81     524 1974.83   549.4 1977.83     642 1996.59     677 2001.67
   707.6 2008.74   729.4 2011.49   751.3  2018.5   763.1 2020.98   893.6 2039.13
#Mann= 5 ,-1 , 0
       0      .1       0  111.88      .1       0  230.26     .06       0
   340.5    .045       0   388.6      .1       0
Bank Sta=340.5,388.6
XS Rating Curve= 0 ,0
Exp/Cntr(USF)=0,0
Exp/Cntr=0.3,0.1

Type RM Length L Ch R = 1 ,26546   ,266.4,263.5,258.3
XS GIS Cut Line= 2
 2434043.8551333573676.1266542262434979.13148328573934.403805266
#Sta/Elev= 30
       0 2179.67    36.8 2168.16    71.7 2152.28    92.9 2140.14   117.2  2122.5
   133.4 2104.07   161.2 2078.86  267.04 2001.67   281.6 1991.52   298.2 1978.04
   302.3 1976.51   327.2 1976.16   341.5 1967.14   352.1 1963.01   360.4 1960.99
   368.7 1960.94   389.4 1962.68   422.3 1962.88   447.5 1966.57     460  1965.8
   509.8 1970.37  594.861971.955   663.1 1973.11   696.5 1977.45  704.131980.266
   816.8 2017.78   866.6  2027.8   904.2 2037.49   937.1 2043.49   970.3  2052.9
#Mann= 6 ,-1 , 0
       0      .1       0  267.04     .06       0   352.1    .045       0
   422.3      .1       0  594.86     .05       0  704.13      .1       0
Bank Sta=352.1,422.3
XS Rating Curve= 0 ,0
Exp/Cntr(USF)=0,0
Exp/Cntr=0.3,0.1