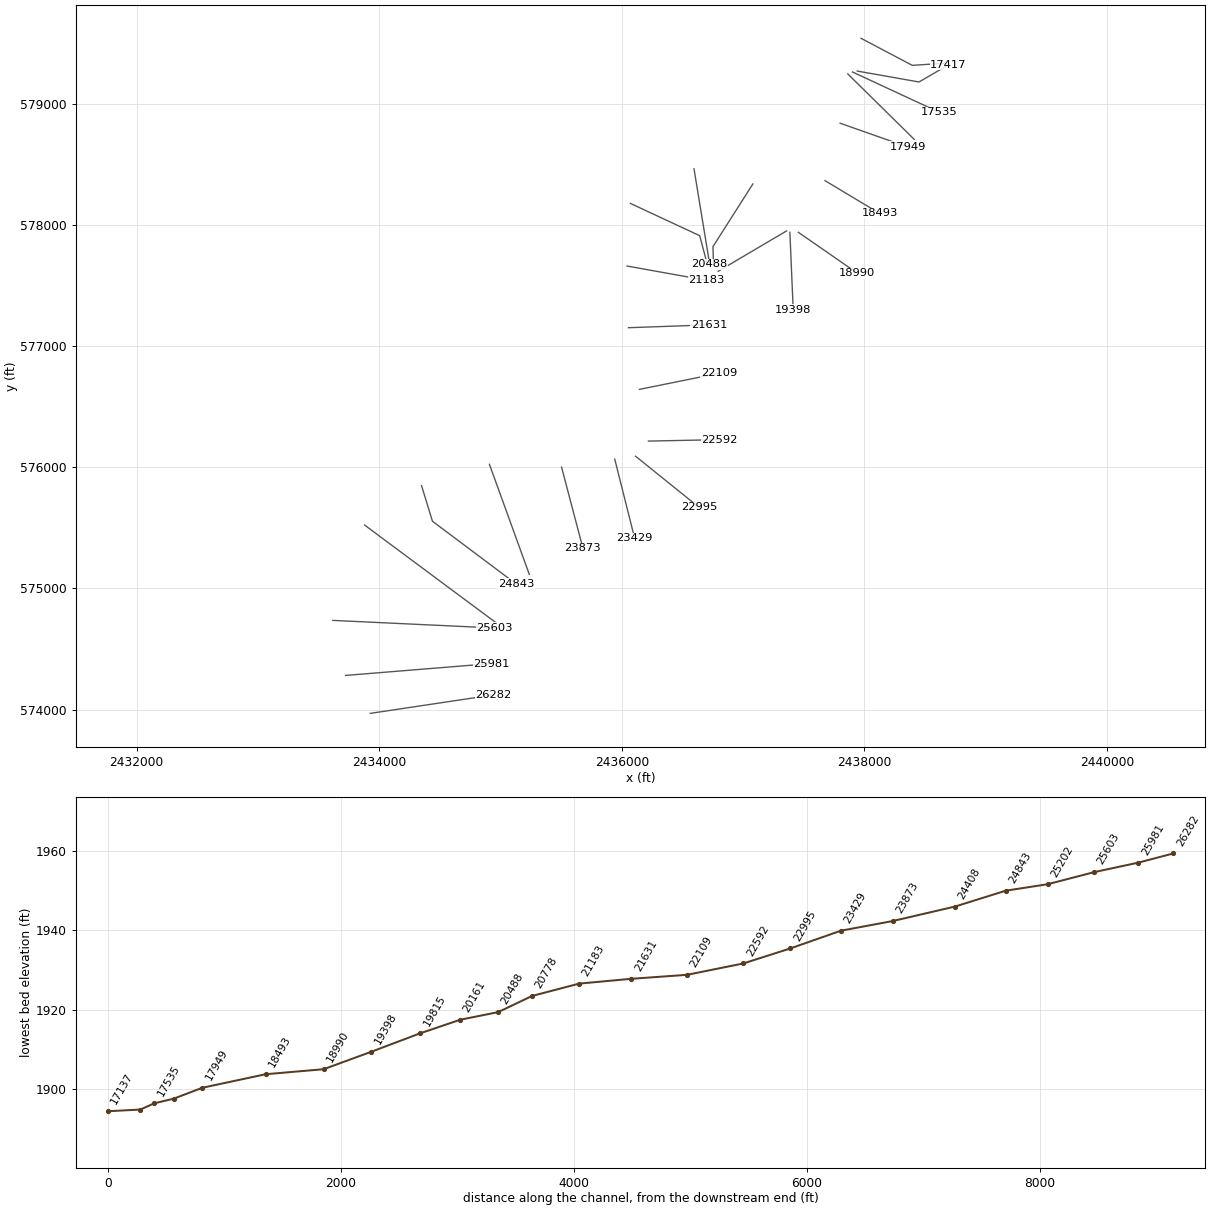
HEC-RAS study THORNCK.prj: THORNCK

--- THORNCK.g01 (geometry) --- (continued)

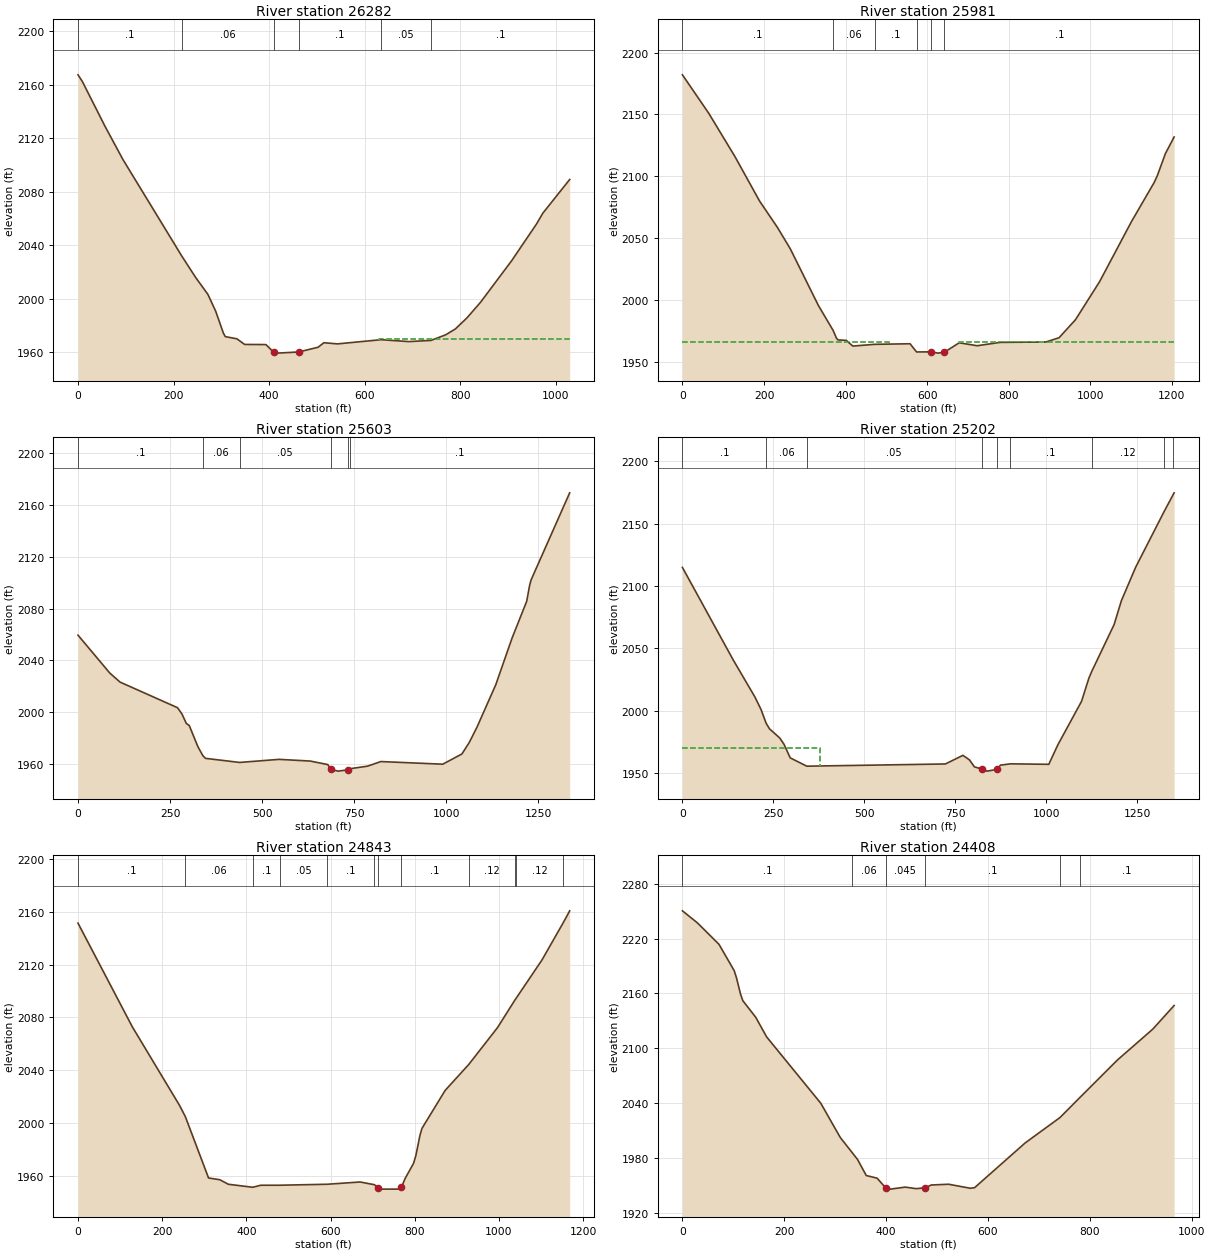
Type RM Length L Ch R = 1 ,26282   ,303.4,301.2,297.9
XS GIS Cut Line= 2
2433926.45642828573969.6234167722434943.91187177574122.241733295
#Sta/Elev= 30
       0 2167.23     8.9  2162.4    56.3 2128.94    93.9 2104.03  217.272031.775
   246.2 2015.84   271.8  2003.2     288 1990.72   304.2 1974.27   308.2 1971.65
   332.5    1970   348.7 1965.81   393.2  1965.7   409.3 1960.03   417.4 1959.31
   461.9 1960.18   502.4 1963.71   514.5 1967.08   542.8 1966.21  634.371969.343
   692.4 1967.92  738.651968.811   769.3 1972.99   789.5 1977.34   813.8 1985.62
   842.1 1997.23   907.4 2028.35   959.4 2055.78   972.6 2063.84  1028.8 2089.04
#Mann= 6 ,-1 , 0
       0      .1       0  217.27     .06       0   409.3    .045       0
   461.9      .1       0  634.37     .05       0  738.65      .1       0
#XS Ineff= 2 , 0
                          629.13         1969.52
Permanent Ineff=
       F       F
Bank Sta=409.3,461.9
XS Rating Curve= 0 ,0
Exp/Cntr(USF)=0,0
Exp/Cntr=0.3,0.1

Type RM Length L Ch R = 1 ,25981   ,379.5,378.1,372.4
XS GIS Cut Line= 2
2433722.96533958574282.6866301532434924.34542094574380.518884335
#Sta/Elev= 30
       0 2182.06    64.6 2150.91   128.8 2115.91     189 2080.04   233.1 2058.55
   264.6 2041.24   333.4 1995.46  369.361975.416   377.6 1969.04   381.6 1967.67
   401.6  1967.3   417.7 1962.71  471.66  1964.1   558.1 1964.57  573.95 1957.94
   610.3 1958.02   626.4 1956.99   642.4 1957.77   678.5 1965.34   722.7 1962.97
   778.8 1965.68   891.2    1966   923.3 1969.43   963.6 1984.01  1022.7 2014.78
  1100.6 2063.23  1156.3 2094.88  1164.1  2100.4  1184.1 2118.44  1205.4 2131.77
#Mann= 6 ,-1 , 0
       0      .1       0  369.36     .06       0  471.66      .1       0
  573.95      .1       0   610.3    .045       0   642.4      .1       0
#XS Ineff= 2 , 0
          507.22 1965.91  677.47         1965.76
Permanent Ineff=
       F       F
Bank Sta=610.3,642.4
XS Rating Curve= 0 ,0
Exp/Cntr(USF)=0,0
Exp/Cntr=0.3,0.1

Type RM Length L Ch R = 1 ,25603   ,417.3,401,383.8
XS GIS Cut Line= 2
2433617.30650507574736.6282895572434951.73845211574674.015646881
#Sta/Elev= 30
       0 2059.45    86.1 2030.32   114.1 2023.28   270.3 2003.53   282.3 1998.77
   294.3 1991.37   302.3 1989.79   325.7  1973.5  339.111966.606   346.4 1964.47
  439.071961.312   546.6 1963.68   630.7 1962.38   678.7 1959.66   686.7 1956.02
   706.7 1954.61   733.2 1955.58  738.971956.461   786.8 1958.45   822.8 1961.99
     991 1959.96  1043.1 1967.84  1063.1 1976.73  1084.2  1988.6  1135.2  2021.3
  1179.2 2057.07  1219.2 2085.64  1227.2 2098.07  1231.2 2102.12  1335.9 2169.19
#Mann= 6 ,-1 , 0
       0      .1       0  339.11     .06       0  439.07     .05       0
   686.7    .045       0   733.2     .05       0  738.97      .1       0
Bank Sta=686.7,733.2
XS Rating Curve= 0 ,0
Exp/Cntr(USF)=0,0
Exp/Cntr=0.3,0.1

Type RM Length L Ch R = 1 ,25202   ,358.5,358.9,358.9
XS GIS Cut Line= 2
2433879.49694628575523.1996131792434963.47832261574717.061838721
#Sta/Elev= 30
       0 2114.91   139.3 2040.85   198.9 2011.14   216.1 2000.91  229.841990.074
     239 1985.56   267.5 1978.09     279 1973.14   296.1 1962.21  341.73 1955.53
   722.5  1957.3   770.6 1964.22   788.4 1960.63   802.2    1955   822.1 1953.25
   837.1 1951.56     865 1952.99   873.5 1956.35  901.211957.404  1006.6 1957.02
  1031.5 1972.68  1096.5 2007.52  1116.8 2026.18 1124.992031.791    1186 2069.11
    1206 2088.25  1245.1 2115.04 1321.82 2158.86 1348.782173.647  1350.9 2174.79
#Mann= 9 ,-1 , 0
       0      .1       0  229.84     .06       0  341.73     .05       0
   822.1    .045       0     865     .05       0  901.21      .1       0
 1124.99     .12       0 1321.82      .1       0 1348.78      .1       0
#XS Ineff= 2 , 0
          378.52 1970.47
Permanent Ineff=
       F       F
Bank Sta=822.1,865
XS Rating Curve= 0 ,0
Exp/Cntr(USF)=0,0
Exp/Cntr=0.3,0.1

Type RM Length L Ch R = 1 ,24843   ,446.8,434.8,396.2
XS GIS Cut Line= 3
2434349.09176635575848.0026970622434439.09744019575554.505934517
2435127.83650963575037.951632437
#Sta/Elev= 30
       0 2151.43     129 2072.91   241.4 2013.26  255.012004.838   310.1 1958.39
   336.8 1957.05   357.2 1953.62  414.981951.356   434.1 1952.88  479.971952.898
   592.11953.635   670.1 1955.35  704.24 1953.28   712.1 1950.94   722.1 1949.94
   762.1 1949.96   768.4 1951.38   777.1 1958.05   797.1  1969.5   802.7 1975.62
   812.1 1990.45   817.1    1996   872.1 2024.72   928.5 2044.49   996.7  2072.4
 1037.39 2092.96 1040.632094.479  1102.1 2123.54 1152.762151.846  1167.9 2160.76
#Mann= 12 ,-1 , 0
       0      .1       0  255.01     .06       0  414.98      .1       0
  479.97     .05       0   592.1      .1       0  704.24      .1       0
   712.1    .045       0   768.4      .1       0   928.5     .12       0
 1037.39      .1       0 1040.63     .12       0 1152.76      .1       0
Bank Sta=712.1,768.4
XS Rating Curve= 0 ,0
Exp/Cntr(USF)=0,0
Exp/Cntr=0.3,0.1

Type RM Length L Ch R = 1 ,24408   ,536.4,535.5,526.7
XS GIS Cut Line= 2
2434908.69226027 576024.100754592435237.40863432575116.217435782
#Sta/Elev= 30
       0 2250.26    29.3 2237.14    71.8 2213.63   101.6 2184.91   105.8 2177.64
   114.3 2158.84   118.6 2152.01   144.1 2133.75   165.4 2112.37   271.7 2039.86
     310  2002.4  333.181986.015     344 1978.31     361 1960.84   382.3 1957.94
   399.3 1947.27   408.4 1945.96   437.6 1948.17   458.9 1946.47   476.3 1947.44
   488.7 1950.47   522.7 1951.31   565.2 1946.91   573.7 1947.54     673 1996.44
  741.432024.228  780.52 2046.13   854.1 2087.07   923.7  2120.9   965.6 2146.72
#Mann= 6 ,-1 , 0
       0      .1       0  333.18     .06       0   399.3    .045       0
   476.3      .1       0  741.43     .12       0  780.52      .1       0
Bank Sta=399.3,476.3
XS Rating Curve= 0 ,0
Exp/Cntr(USF)=0,0
Exp/Cntr=0.3,0.1

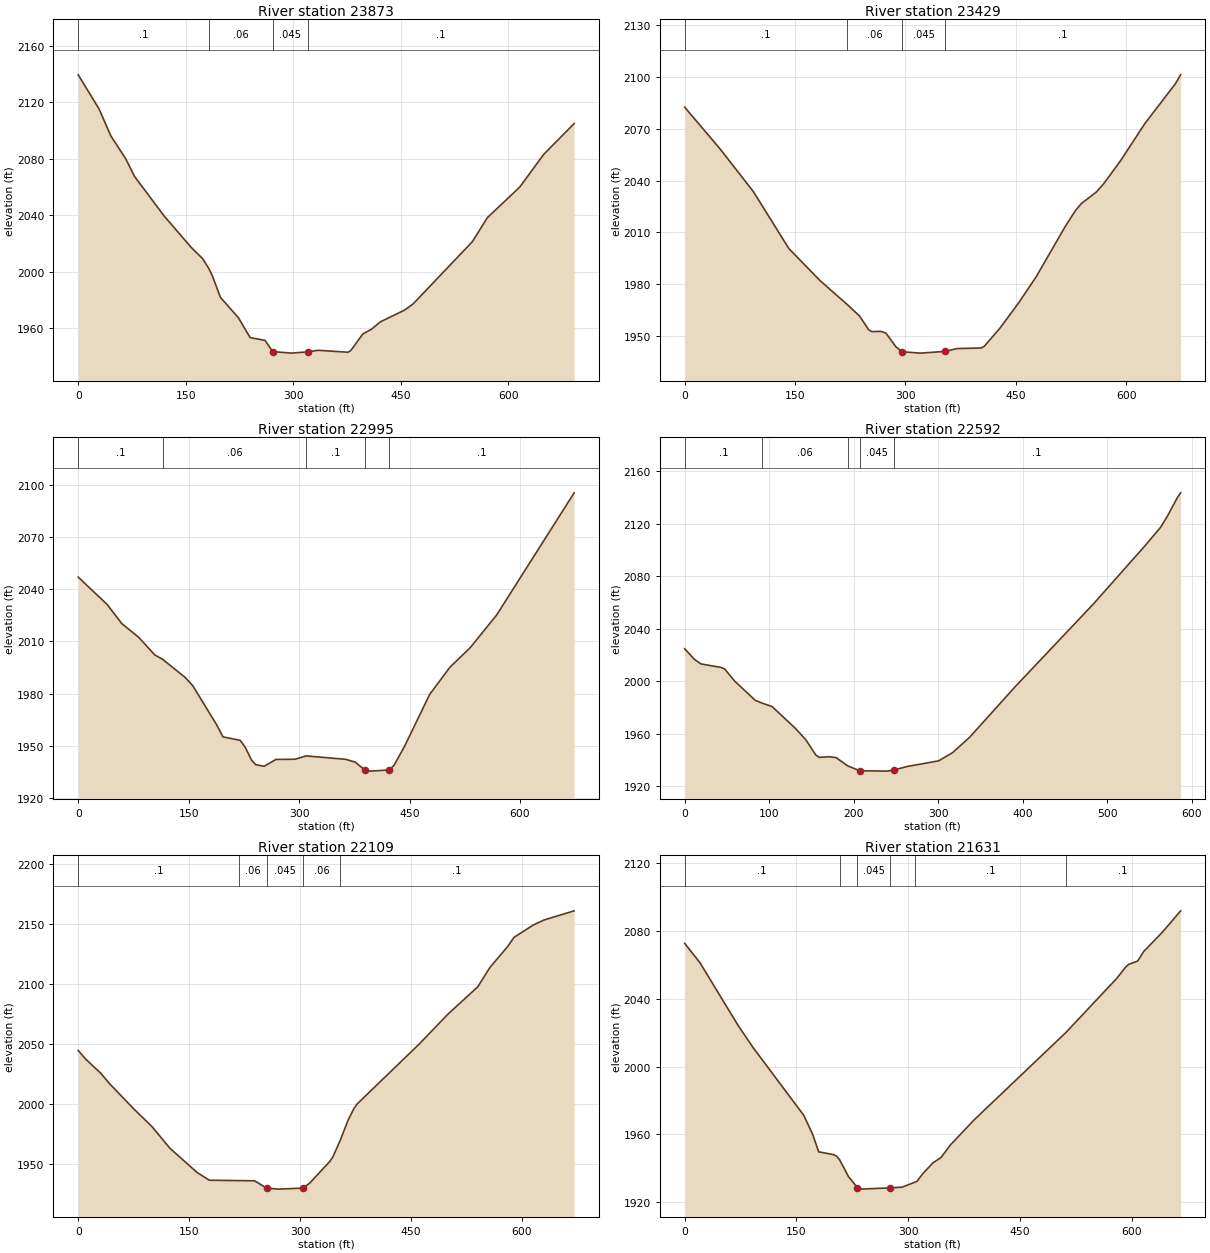
Type RM Length L Ch R = 1 ,23873   ,443.7,443.3,444.8
XS GIS Cut Line= 2
2435503.51236569576000.6210135862435679.61042322575331.448394982
#Sta/Elev= 30
       0 2139.45      29 2115.36    45.5 2096.22    66.2 2080.09    78.6 2067.48
     120  2039.4   157.7 2017.18   173.7  2009.2  182.592001.965   187.1 1997.19
   198.5 1981.79   223.4 1967.47   239.9 1953.33   260.6 1951.35   271.5 1943.39
   297.7 1942.31   320.6 1943.24     335 1944.31   376.4 1942.93   380.5 1944.24
   397.1 1955.87   409.5 1959.35   421.5 1964.46     455 1972.67   467.4 1977.21
   550.1 2021.35   570.8  2038.2   616.3 2060.06   649.3 2082.97     692 2104.94
#Mann= 4 ,-1 , 0
       0      .1       0  182.59     .06       0   271.5    .045       0
   320.6      .1       0
Bank Sta=271.5,320.6
XS Rating Curve= 0 ,0
Exp/Cntr(USF)=0,0
Exp/Cntr=0.3,0.1

Type RM Length L Ch R = 1 ,23429   ,425.2,434,450.5
XS GIS Cut Line= 2
2435941.80086443 576067.146946432436106.15905145575413.627488495
#Sta/Elev= 30
       0 2082.59      48 2058.43    93.4 2033.57   141.6 2000.53   184.1 1981.92
  220.271968.328   237.7 1961.39   250.1 1953.38   254.2 1952.37   266.6 1952.53
   273.4 1951.55   287.2 1943.49   295.5 1940.72   320.2 1939.89   354.4  1940.9
   369.7 1942.53   402.7 1942.86   406.8 1943.73   428.3 1954.32   453.6 1968.93
   477.7 1984.24   517.2 2013.43   530.5  2022.3   538.8 2026.61   559.4 2033.35
   569.3 2038.15   592.4 2051.58   625.4 2073.15   666.6 2096.06   673.9 2101.36
#Mann= 4 ,-1 , 0
       0      .1       0  220.27     .06       0   295.5    .045       0
   354.4      .1       0
Bank Sta=295.5,354.4
XS Rating Curve= 0 ,0
Exp/Cntr(USF)=0,0
Exp/Cntr=0.3,0.1

Type RM Length L Ch R = 1 ,22995   ,392.6,403.6,422.4
XS GIS Cut Line= 2
2436113.98563179576090.626687433 2436638.3665142575667.991349368
#Sta/Elev= 30
       0 2047.02    39.2 2031.34    59.1 2020.35    81.9  2012.5   104.1 2002.22
  114.691999.745   145.2 1989.34   155.5 1984.62   188.1 1962.04   196.6 1955.13
     220 1953.16   226.9 1949.12   235.5 1941.69   241.1 1939.14   252.5 1938.23
   268.5 1942.17   294.2 1942.26  309.531944.203   363.5 1942.22   376.4 1940.55
   389.1 1936.14   396.9 1935.44   422.6 1936.13   428.9 1938.78   443.2 1949.73
   477.2 1979.49   504.8  1995.2   532.3 2006.42   568.3 2025.26   673.5 2095.49
#Mann= 5 ,-1 , 0
       0      .1       0  114.69     .06       0  309.53      .1       0
   389.1    .045       0   422.6      .1       0
Bank Sta=389.1,422.6
XS Rating Curve= 0 ,0
Exp/Cntr(USF)=0,0
Exp/Cntr=0.3,0.1

Type RM Length L Ch R = 1 ,22592   ,478.4,483,488.7
XS GIS Cut Line= 2
 2436219.6444663576215.8519727862436806.63799139576227.591843288
#Sta/Elev= 30
       0 2024.77    11.4 2016.76    19.1 2013.23    43.4 2010.51    47.4 2009.36
    59.4 2000.02    83.4 1985.61   92.061983.309   103.4  1980.8   131.4 1964.01
   143.4 1955.53   155.4  1943.8   159.4 1942.12   171.4  1942.6   179.4 1941.91
  193.021935.637   207.4 1931.95   239.4 1931.66   247.4 1932.45   263.4 1935.19
   300.7 1939.49   317.1 1945.69   337.5 1957.54   391.4 1995.99   483.5 2058.56
   543.5 2102.04   563.5 2117.21   571.5 2125.65   583.5 2140.03   587.1 2143.36
#Mann= 5 ,-1 , 0
       0      .1       0   92.06     .06       0  193.02      .1       0
   207.4    .045       0   247.4      .1       0
Bank Sta=207.4,247.4
XS Rating Curve= 0 ,0
Exp/Cntr(USF)=0,0
Exp/Cntr=0.3,0.1

Type RM Length L Ch R = 1 ,22109   ,481.8,478.1,473.2
XS GIS Cut Line= 2
2436145.29195313576642.4006010192436802.72470123576775.452466706
#Sta/Elev= 30
       0 2044.59      10 2037.46    30.4 2025.64    42.6 2016.76    75.3 1995.72
    99.7 1981.07   124.2 1962.83     161 1942.61   177.3 1936.25  217.181935.918
   238.5 1935.76   254.8 1929.67   271.1  1928.8   303.8 1929.68   313.2 1933.88
   340.5 1952.06   344.6 1955.95  354.311969.372     365 1986.37   373.1  1996.3
   377.2 1999.87   461.5 2050.14   499.6 2074.65   540.5 2097.79   556.8 2113.86
   581.3 2131.74   589.4 2139.05   615.6  2149.4   630.2 2153.61   670.8 2161.22
#Mann= 5 ,-1 , 0
       0      .1       0  217.18     .06       0   254.8    .045       0
   303.8     .06       0  354.31      .1       0
Bank Sta=254.8,303.8
XS Rating Curve= 0 ,0
Exp/Cntr(USF)=0,0
Exp/Cntr=0.3,0.1

Type RM Length L Ch R = 1 ,21631   ,453.8,448.1,441.3
XS GIS Cut Line= 2
2436055.28627928577151.1283227642436720.54560771577174.608063768
#Sta/Elev= 30
       0 2072.59    20.4 2061.29    71.8 2024.19    91.8 2011.23   159.9 1971.28
   171.9 1959.94   179.9 1949.77   199.9 1948.12   203.9 1947.24  207.851945.196
   219.9 1935.17   231.9 1928.69   235.9  1927.8   275.5 1928.54   291.9 1928.96
   309.11931.895   311.9 1932.44   319.9 1937.08   333.5 1943.38     344 1946.36
   356.7 1953.83     388 1968.39  511.622020.043   580.1 2052.04   592.1 2058.73
   596.1 2060.26   608.1  2062.2   616.1  2067.8   641.4 2079.26   665.7 2091.78
#Mann= 6 ,-1 , 0
       0      .1       0  207.85     .06       0   231.9    .045       0
   275.5     .06       0   309.1      .1       0  511.62      .1       0
Bank Sta=231.9,275.5
XS Rating Curve= 0 ,0
Exp/Cntr(USF)=0,0
Exp/Cntr=0.3,0.1

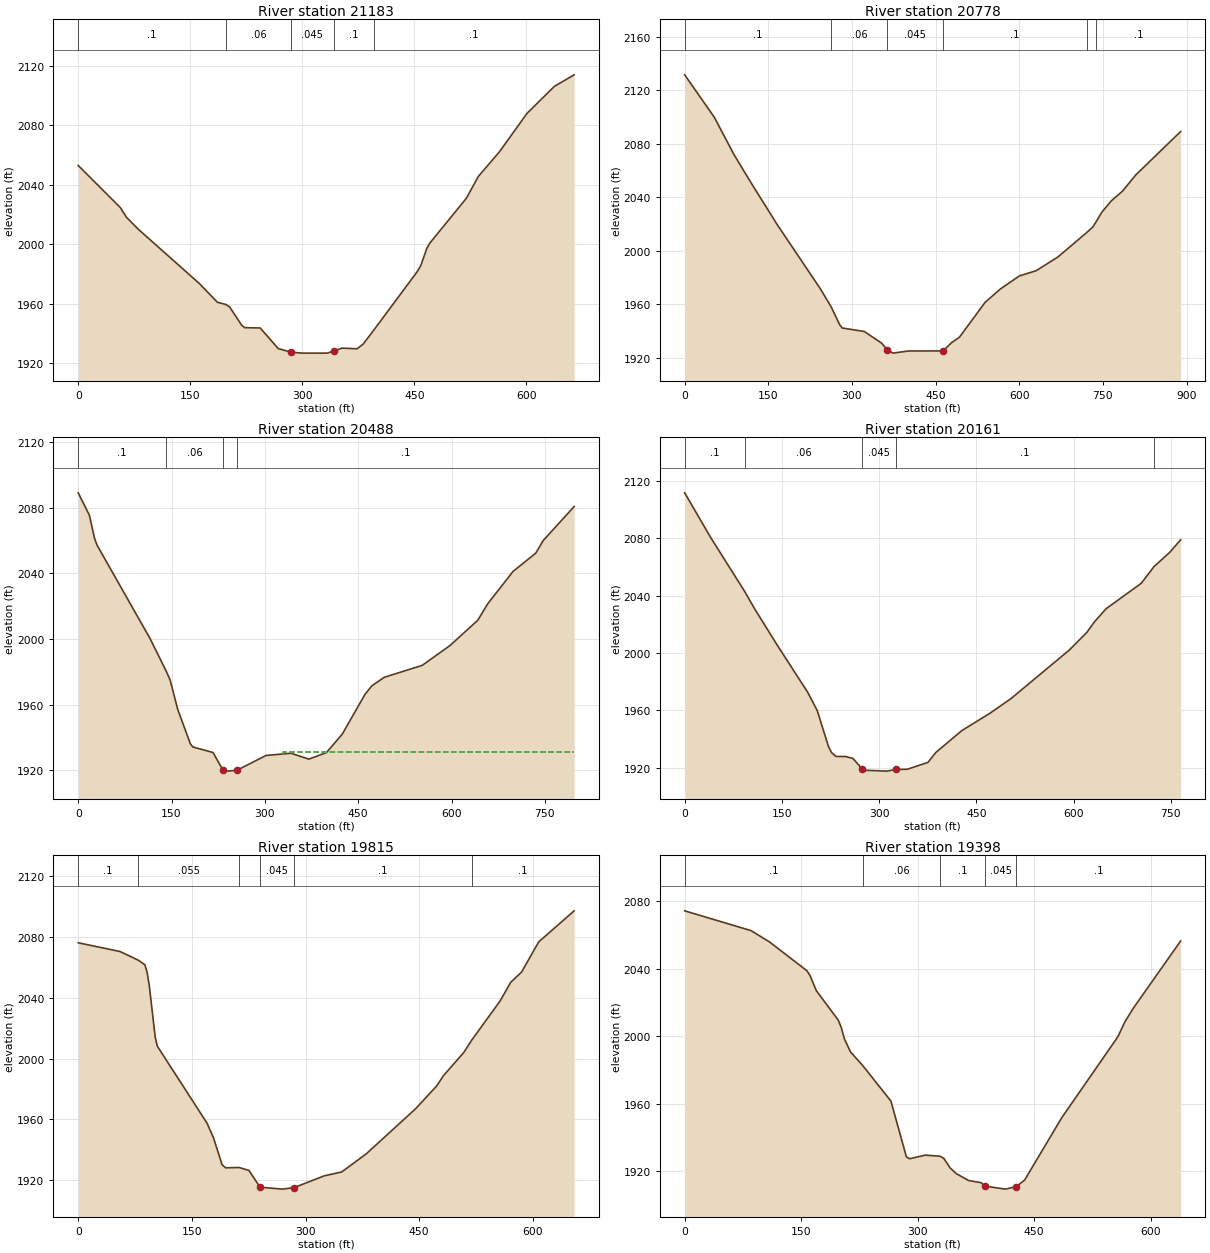
Type RM Length L Ch R = 1 ,21183   ,423.8,405,397.2
XS GIS Cut Line= 2
2436043.54640878577659.8560445092436697.06586671577542.457339491
#Sta/Elev= 30
       0 2053.01    56.4 2024.63    64.5 2018.16    80.8 2009.89   162.1 1973.53
   186.4 1960.84  197.591959.386   202.7 1957.72     219 1945.28     223 1943.75
   243.7 1943.53   267.7 1929.69     285 1927.19   300.2 1926.59   333.3  1926.6
   341.9 1927.92   353.1 1929.98   373.4 1929.53   381.5 1932.68  396.261942.427
   454.6 1981.96   458.7 1985.63   466.8 1997.22     471 2000.86   519.7 2030.95
   535.9 2045.74   564.1 2062.29   600.9 2088.13   637.5 2106.29     664 2114.09
#Mann= 5 ,-1 , 0
       0      .1       0  197.59     .06       0     285    .045       0
   341.9      .1       0  396.26      .1       0
Bank Sta=285,341.9
XS Rating Curve= 0 ,0
Exp/Cntr(USF)=0,0
Exp/Cntr=0.3,0.1

Type RM Length L Ch R = 1 ,20778   ,326,289.6,276.4
XS GIS Cut Line= 3
2436070.93943995578176.4103465892436642.27980437577910.306615215
2436708.80573721577659.856044509
#Sta/Elev= 30
       0 2131.62    53.1 2099.93    88.4 2071.98   117.5 2051.92   165.3 2020.01
     244 1971.16   263.1 1957.77   278.1 1944.64   282.5 1942.28   322.2 1939.66
   353.1 1930.96   363.5 1925.93   373.4 1923.48   401.6 1925.09   463.4 1925.12
   478.7 1931.35   492.7 1935.36   538.9 1961.51     566 1971.41   600.2 1981.22
   630.3 1985.11   669.5 1995.44  721.562013.868   731.6 2017.65  737.862021.682
   748.1  2028.9   764.7  2037.2   785.4 2044.73     809 2056.76   889.4 2089.19
#Mann= 6 ,-1 , 0
       0      .1       0   263.1     .06       0   363.5    .045       0
   463.4      .1       0  721.56      .1       0  737.86      .1       0
Bank Sta=363.5,463.4
XS Rating Curve= 0 ,0
Exp/Cntr(USF)=0,0
Exp/Cntr=0.3,0.1

Type RM Length L Ch R = 1 ,20488   ,342.5,326.7,316.9
XS GIS Cut Line= 2
2436595.32032236  578462.08052882436724.45889788577675.509205178
#Sta/Elev= 30
       0 2089.12      18 2075.43    26.1 2061.62    30.1 2057.33   115.3 2000.38
  140.981980.787   147.7 1975.03   159.8 1957.25   180.1 1936.24   184.2 1934.17
   216.6  1930.8   232.8 1919.95   240.9 1919.43   255.4 1919.98   301.7 1928.96
   341.9 1930.34   370.6 1926.74     399 1930.72   424.4 1941.98   460.8 1966.16
   471.9 1971.41   491.8 1976.63     553 1983.93   597.6 1996.03   642.2 2011.43
   658.4 2021.59   698.9 2041.18   735.4 2052.34   747.5 2060.08   797.1 2080.76
#Mann= 4 ,-1 , 0
       0      .1       0  140.98     .06       0   232.8    .045       0
   255.4      .1       0
#XS Ineff= 2 , 0
                           329.8         1931.27
Permanent Ineff=
       F       F
Bank Sta=232.8,255.4
XS Rating Curve= 0 ,0
Exp/Cntr(USF)=0,0
Exp/Cntr=0.3,0.1

Type RM Length L Ch R = 1 ,20161   ,358.9,346.1,330.6
XS GIS Cut Line= 3
 2437080.5683031578336.8552434472436751.85192905577820.300941368
2436755.76521922577667.682624844
#Sta/Elev= 30
       0  2111.7    40.2 2080.46   92.472042.923   107.3  2031.2   142.8  2005.4
   189.9 1972.43   204.5 1959.71   221.7 1934.79   226.5 1930.48   233.3 1927.76
   247.8 1927.74   259.4  1926.4   273.9 1919.03   278.6 1918.12   311.5 1917.51
     326 1918.65   343.4 1918.81   375.3 1923.64   387.5 1930.58   427.6 1945.82
   470.9 1957.92   503.1 1968.05   593.2 2001.98   620.2 2014.25   632.2  2021.8
     650 2030.85   704.2 2048.58  723.762060.173   747.9 2070.07   764.9 2078.91
#Mann= 5 ,-1 , 0
       0      .1       0   92.47     .06       0   273.9    .045       0
     326      .1       0  723.76      .1       0
Bank Sta=273.9,326
XS Rating Curve= 0 ,0
Exp/Cntr(USF)=0,0
Exp/Cntr=0.3,0.1

Type RM Length L Ch R = 1 ,19815   ,386.3,417.7,441.4
XS GIS Cut Line= 2
2437358.41190498577949.4395168872436794.89812089577616.809852669
#Sta/Elev= 30
       0 2076.31    55.1 2070.56   79.132064.877      88 2061.79    90.9 2056.87
    93.8 2048.05   101.6 2014.15   104.4  2008.2   169.8 1957.66   178.5 1947.88
   189.8 1930.17   194.5  1928.1  212.22 1928.32   225.3 1926.38   239.9 1915.34
   269.6 1914.07   285.3 1915.14   324.5  1922.8   347.7 1925.38   380.1  1937.3
   445.3 1967.06   473.1 1982.06     482 1988.83   508.6 2003.94  519.642012.477
   556.7 2037.98   570.7 2050.26     585    2057   607.6 2076.85   654.4 2097.34
#Mann= 6 ,-1 , 0
       0      .1       0   79.13    .055       0  212.22      .1       0
   239.9    .045       0   285.3      .1       0  519.64      .1       0
Bank Sta=239.9,285.3
XS Rating Curve= 0 ,0
Exp/Cntr(USF)=0,0
Exp/Cntr=0.3,0.1

Type RM Length L Ch R = 1 ,19398   ,380.9,407.9,427.2
XS GIS Cut Line= 2
2437385.80493615577937.6996463862437413.19796732 577299.83334912
#Sta/Elev= 30
       0 2074.18    85.4 2062.47   109.4  2055.7   157.4 2038.72   161.4 2035.88
   169.5 2026.91   197.5 2009.64   201.5  2005.3   205.8 1998.22   213.5 1990.66
  229.221982.598   265.5  1961.6   285.5 1928.49   289.6 1927.43   309.7 1929.57
  328.671928.938   333.6 1927.69   341.6 1922.07   349.6 1918.65   365.6 1914.54
   381.6  1913.3   386.2 1911.26     413 1909.45   426.9 1910.93   437.7 1914.84
   485.4 1951.67   557.8  1999.7   566.6 2008.36   577.4 2016.41   638.5 2056.31
#Mann= 5 ,-1 , 0
       0      .1       0  229.22     .06       0  328.67      .1       0
   386.2    .045       0   426.9      .1       0
Bank Sta=386.2,426.9
XS Rating Curve= 0 ,0
Exp/Cntr(USF)=0,0
Exp/Cntr=0.3,0.1

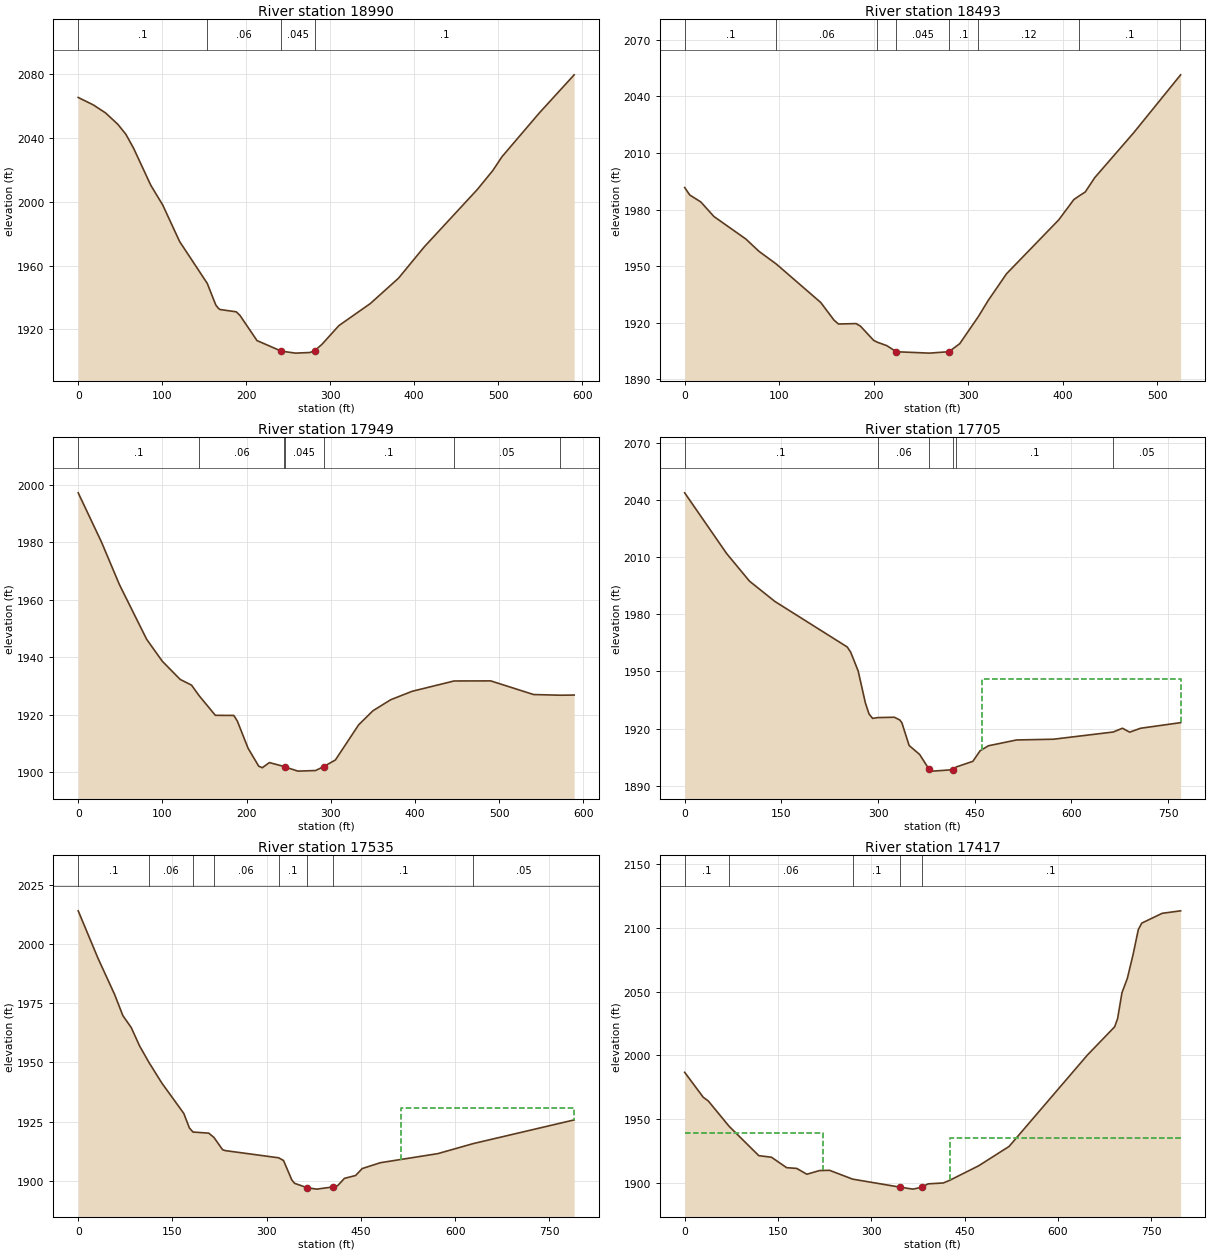
Type RM Length L Ch R = 1 ,18990   ,496.7,496.7,498.7
XS GIS Cut Line= 2
2437456.24415916577937.699646386 2437941.4921399   577601.156692
#Sta/Elev= 30
       0 2065.41    17.9 2060.78    32.5 2055.75    47.1 2048.63    56.8  2042.3
    66.1  2033.4    86.5 2010.28   100.6 1998.02   120.7 1975.13  153.691948.784
   163.8 1935.29   166.7 1933.31   168.7 1932.44   188.2 1930.99   192.6 1928.74
   212.9 1912.95   241.8 1906.33   258.7 1905.08   275.8 1905.46   281.7 1906.64
   290.3 1910.64   310.4 1922.35   347.8 1936.17   381.3 1952.04   412.1 1971.76
   475.4 2007.81   493.6 2019.56   504.6 2028.27   548.9 2055.62   590.5 2079.61
#Mann= 4 ,-1 , 0
       0      .1       0  153.69     .06       0   241.8    .045       0
   281.7      .1       0
Bank Sta=241.8,281.7
XS Rating Curve= 0 ,0
Exp/Cntr(USF)=0,0
Exp/Cntr=0.3,0.1

Type RM Length L Ch R = 1 ,18493   ,534.7,544,548.4
XS GIS Cut Line= 2
2437675.38840853578364.2482746182438125.41677776578094.231253077
#Sta/Elev= 30
       0 1991.65     5.4 1987.71    17.1 1984.01    30.9 1976.31    64.7 1964.37
    78.7 1957.79   96.851951.125     144 1930.68     158 1921.34   162.7 1919.27
   181.3 1919.49     186 1918.14     200 1910.57  203.781909.634     214 1907.76
     224 1904.55     259 1903.82   279.7 1904.58   291.1 1908.86  310.711923.166
   321.3 1931.85   340.6 1945.93   395.9 1974.55   411.8 1985.28  417.641987.284
   423.9 1989.31   433.9 1996.89   475.2 2020.76  524.582051.313   524.8 2051.45
#Mann= 8 ,-1 , 0
       0      .1       0   96.85     .06       0  203.78      .1       0
     224    .045       0   279.7      .1       0  310.71     .12       0
  417.64      .1       0  524.58     .12       0
Bank Sta=224,279.7
XS Rating Curve= 0 ,0
Exp/Cntr(USF)=0,0
Exp/Cntr=0.3,0.1

Type RM Length L Ch R = 1 ,17949   ,253.7,244.2,232.3
XS GIS Cut Line= 2
2437800.61369388578837.7563848582438356.30089763578642.091876495
#Sta/Elev= 30
       0 1997.22    27.8    1980      49 1965.27    81.3 1946.28    99.9 1938.64
   121.1 1932.32   134.6 1930.34  143.711926.627   162.9 1919.83   184.8 1919.79
     189 1917.86   201.7 1908.43   214.4 1902.15   218.7 1901.61   227.1 1903.39
  244.621902.026   245.3 1901.89   261.1 1900.42     282 1900.63   291.4 1901.97
   305.5  1904.3   333.1 1916.52   350.1 1921.42   371.3 1925.27   396.7 1928.19
  446.441931.779     490 1931.81   540.9 1927.06   572.71926.823   589.1 1926.88
#Mann= 7 ,-1 , 0
       0      .1       0  143.71     .06       0  244.62      .1       0
   245.3    .045       0   291.4      .1       0  446.44     .05       0
   572.7      .1       0
Bank Sta=245.3,291.4
XS Rating Curve= 0 ,0
Exp/Cntr(USF)=0,0
Exp/Cntr=0.3,0.1

Type RM Length L Ch R = 1 ,17705   ,161.2,169.2,178.4
XS GIS Cut Line= 2
2437863.22633656579244.7385622552438411.08695998578704.704519171
#Sta/Elev= 30
       0 2043.74    65.2 2011.83   100.6 1997.37   139.9 1986.75   252.2 1962.83
   257.5 1960.13   269.1 1950.27   280.3 1933.51   285.9 1927.74   291.5 1925.37
  299.381925.782   325.3 1925.97   333.8  1924.5   336.9  1923.1   348.2 1911.13
   364.5 1906.43   379.1 1898.68   384.7 1897.69   416.6 1898.45  421.191899.862
     447 1902.83   458.3 1908.39   471.2    1911   514.8 1914.04   572.3 1914.44
  664.811918.224     679  1920.2   690.3 1918.14   707.2 1920.19   769.3 1923.13
#Mann= 6 ,-1 , 0
       0      .1       0  299.38     .06       0   379.1    .045       0
   416.6     .06       0  421.19      .1       0  664.81     .05       0
#XS Ineff= 2 , 0
                          461.22         1946.03
Permanent Ineff=
       F       F
Bank Sta=379.1,416.6
XS Rating Curve= 0 ,0
Exp/Cntr(USF)=0,0
Exp/Cntr=0.3,0.1

Type RM Length L Ch R = 1 ,17535   ,112.3,118.6,123.1
XS GIS Cut Line= 2
2437902.35923823579260.3917229242438618.49133884578927.762058706
#Sta/Elev= 30
       0 2014.08    31.4  1994.1    57.9 1978.78    71.1 1969.81    84.4 1964.77
    97.6 1957.07  112.871949.922   133.3 1941.26   168.1 1928.49     177 1922.34
  182.771920.623   207.8 1920.16  216.041918.352   229.9 1913.16   234.3 1912.77
  319.211909.732   326.9 1908.59   340.1 1900.38   344.5 1898.96   364.9 1897.05
   379.8  1896.5   406.3 1897.45     413 1897.95   423.9 1901.05   441.6 1902.25
   452.2 1905.19   481.2 1907.67   572.6  1911.5  628.711915.722   789.6 1925.74
#Mann= 8 ,-1 , 0
       0      .1       0  112.87     .06       0  182.77      .1       0
  216.04     .06       0  319.21      .1       0   364.9    .045       0
   406.3      .1       0  628.71     .05       0
#XS Ineff= 2 , 0
                          513.19         1930.68
Permanent Ineff=
       F       F
Bank Sta=364.9,406.3
XS Rating Curve= 0 ,0
Exp/Cntr(USF)=0,0
Exp/Cntr=0.3,0.1

Type RM Length L Ch R = 1 ,17417   ,275.5,279.5,268.6
XS GIS Cut Line= 3
 2437941.4921399579268.2183032582438450.21986165579178.212629411
2438692.84385202579319.091075433
#Sta/Elev= 30
       0 1986.65    29.8 1967.09      38 1964.13   71.291944.345   119.2 1921.21
   139.5 1919.99   163.9 1911.79   180.1  1911.2   196.4 1906.63   216.7  1909.5
   232.9 1909.71  269.951902.785   346.3 1896.48   366.9 1894.94   380.8 1896.37
   391.3 1899.08   415.7 1899.78   425.7 1901.79   472.6 1913.27   521.5 1928.47
   647.3 2000.17   691.2  2022.4   695.9 2028.83   702.9 2049.09   711.6 2060.45
   720.8 2079.13   729.2 2098.68   734.7 2103.77   767.6 2111.49   797.2 2113.43
#Mann= 5 ,-1 , 0
       0      .1       0   71.29     .06       0  269.95      .1       0
   346.3    .045       0   380.8      .1       0
#XS Ineff= 2 , 0
          222.34 1939.09   425.7          1935.2
Permanent Ineff=
       F       F
Bank Sta=346.3,380.8
XS Rating Curve= 0 ,0
Exp/Cntr(USF)=0,0
Exp/Cntr=0.3,0.1

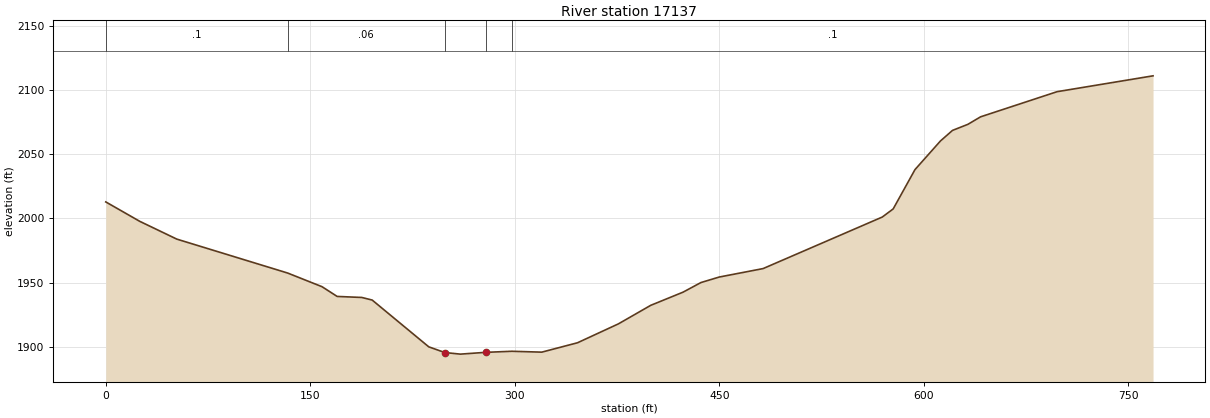
Type RM Length L Ch R = 1 ,17137   ,307.4,305.8,299
XS GIS Cut Line= 3
2437972.79846124  579538.23532482438395.43379931579315.177785265
2438685.01727169579334.744236102
#Sta/Elev= 30
       0 2012.88    24.9 1997.79    52.1 1983.95  133.391957.574   158.6 1946.95
   169.7 1939.38   187.8 1938.58   195.4 1936.56   236.9 1900.18   248.7 1895.74
   260.1 1894.52   278.5  1895.9  297.811896.735   319.8 1896.06     346 1903.36
     376 1918.06   399.7 1932.47   423.4 1942.71   436.5 1950.17   449.9 1954.46
   482.1 1961.04   569.5 2001.11   577.5 2007.43   593.5 2038.01   612.2  2060.3
     621 2068.48   632.3 2073.21   641.6 2079.04   697.7 2098.59   768.1 2110.93
#Mann= 5 ,-1 , 0
       0      .1       0  133.39     .06       0   248.7    .045       0
   278.5     .06       0  297.81      .1       0
Bank Sta=248.7,278.5
XS Rating Curve= 0 ,0
Exp/Cntr(USF)=0,0
Exp/Cntr=0.3,0.1