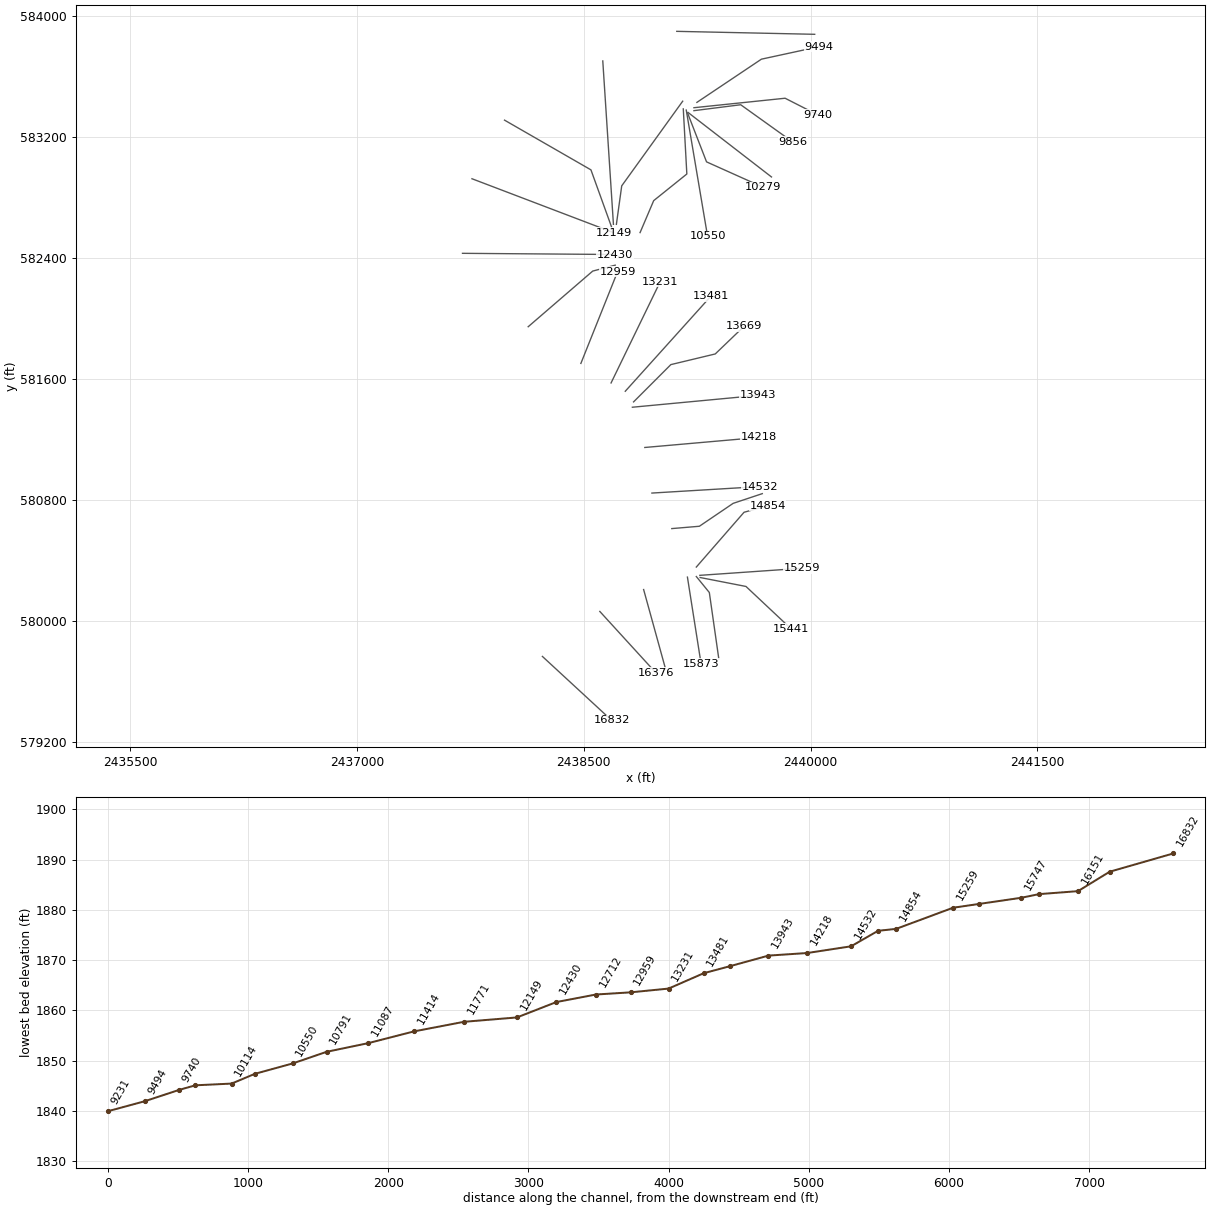
HEC-RAS study THORNCK.prj: THORNCK

--- THORNCK.g01 (geometry) --- (continued)

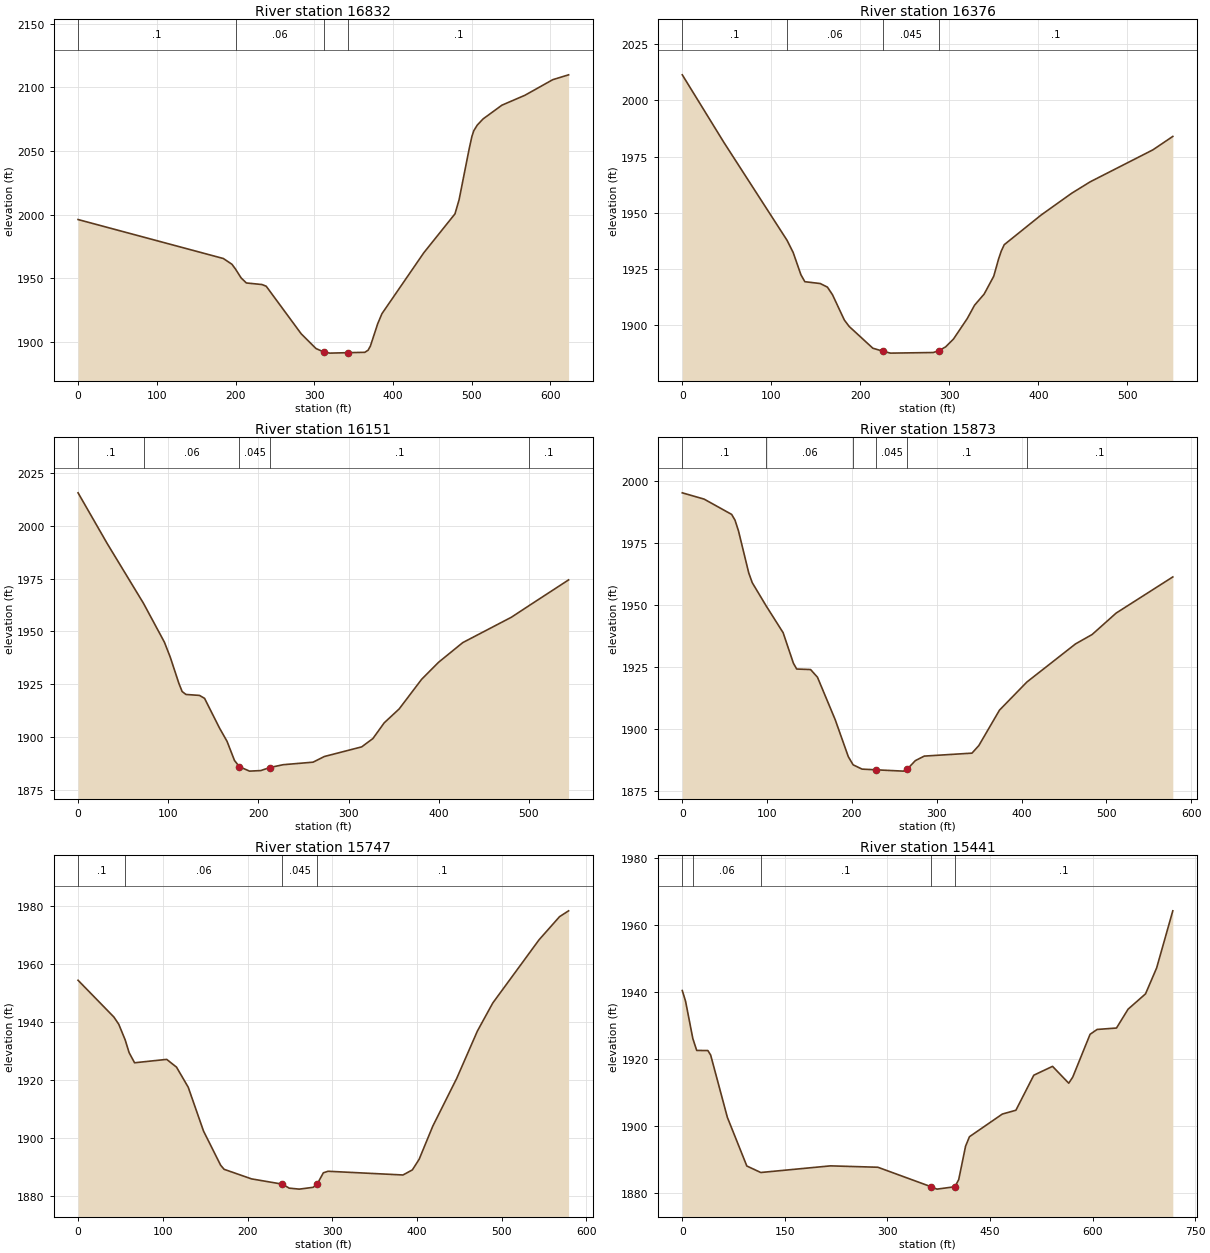
Type RM Length L Ch R = 1 ,16832   ,458,455.4,452.5
XS GIS Cut Line= 2
2438227.16232211579765.2061545022438685.01727169579342.570816436
#Sta/Elev= 30
       0 1996.17   184.5 1965.56   195.5 1961.01  200.021957.224   207.1 1950.33
   213.8 1946.34   233.6 1945.11     239 1943.78   283.5 1906.36   302.2 1894.86
   311.8 1892.17   319.9 1891.23   343.5  1891.6   364.2 1891.86   368.4 1893.51
   371.3 1896.72   380.6 1914.27     386 1922.21   439.2 1970.08   478.8 2000.64
     484  2011.7   496.8 2051.64   500.3 2061.49   502.7 2065.96   507.1 2070.36
   514.5 2075.21   538.4 2085.99   567.6 2093.77     603 2106.03   623.1 2109.84
#Mann= 4 ,-1 , 0
       0      .1       0  200.02     .06       0   311.8    .045       0
   343.5      .1       0
Bank Sta=311.8,343.5
XS Rating Curve= 0 ,0
Exp/Cntr(USF)=0,0
Exp/Cntr=0.3,0.1

Type RM Length L Ch R = 1 ,16376   ,235.8,225.5,215.1
XS GIS Cut Line= 2
2438606.75146834580062.6162072152438978.51403423579655.634029818
#Sta/Elev= 30
       0 2011.39    46.7 1981.36  117.751937.755   124.6 1932.36   133.3 1922.46
   137.7 1919.36     155 1918.54   163.1 1916.94   168.8 1913.55   182.1 1902.31
   187.5 1899.46   214.1 1889.77   225.4 1888.44   233.9 1887.58     282 1887.85
   288.3 1888.68   295.9 1890.36   304.7 1893.82   320.3 1903.01   328.4 1908.88
   339.2 1913.85     350  1921.8   355.4 1929.44   358.5 1933.04   361.8 1935.83
   403.3 1949.04   437.7 1958.74   458.4  1963.8   528.8 1978.01   551.2 1983.99
#Mann= 4 ,-1 , 0
       0      .1       0  117.75     .06       0   225.4    .045       0
   288.3      .1       0
Bank Sta=225.4,288.3
XS Rating Curve= 0 ,0
Exp/Cntr(USF)=0,0
Exp/Cntr=0.3,0.1

Type RM Length L Ch R = 1 ,16151   ,279.9,277.6,275.1
XS GIS Cut Line= 2
2438896.33494072580207.4079434042439041.12667691579683.027060989
#Sta/Elev= 30
       0 2015.79    32.4 1991.66    72.61963.323    95.7 1944.96   102.2 1937.85
   111.9 1925.26   115.4 1921.51   119.6 1920.11   134.7 1919.65   140.3 1918.25
   156.9 1904.13   165.2 1897.88   173.5 1888.76   178.9 1885.84   190.1 1883.72
   202.6 1883.98   212.7 1885.43   227.5 1886.77   260.6 1887.97   273.1 1890.65
   314.6 1895.24     327 1899.19   339.5 1906.63   356.1 1913.23     381 1927.29
   399.8 1935.37   426.6  1944.7   480.6 1956.76  500.531962.359     544 1974.47
#Mann= 5 ,-1 , 0
       0      .1       0    72.6     .06       0   178.9    .045       0
   212.7      .1       0  500.53      .1       0
Bank Sta=178.9,212.7
XS Rating Curve= 0 ,0
Exp/Cntr(USF)=0,0
Exp/Cntr=0.3,0.1

Type RM Length L Ch R = 1 ,15873   ,125.9,125.6,125.2
XS GIS Cut Line= 2
 2439185.9184131580289.5870369162439275.92408694579718.246672495
#Sta/Elev= 30
       0 1995.17    25.8 1992.63    58.2 1986.48    62.2 1984.15    66.3  1979.8
    78.4 1962.88    82.5 1958.99   99.051949.569   118.9 1938.87     131  1926.6
   134.9 1924.23   151.3 1924.02   159.4 1920.94   180.4 1903.76   195.8 1888.92
  201.471885.663     212 1883.94   228.2 1883.66   260.6 1883.13   265.1 1883.87
   274.8 1887.36   285.3 1889.18   341.6 1890.37   349.7 1893.44     374 1907.67
  406.321918.999   463.7 1934.35   483.3 1938.14   511.6 1946.76   578.4 1961.31
#Mann= 6 ,-1 , 0
       0      .1       0   99.05     .06       0  201.47      .1       0
   228.2    .045       0   265.1      .1       0  406.32      .1       0
Bank Sta=228.2,265.1
XS Rating Curve= 0 ,0
Exp/Cntr(USF)=0,0
Exp/Cntr=0.3,0.1

Type RM Length L Ch R = 1 ,15747   ,287.6,306.4,319.7
XS GIS Cut Line= 3
2439244.61776561580293.5003270842439330.71014928580187.841492567
2439393.32279196579749.552993833
#Sta/Elev= 30
       0 1954.31    42.3 1941.65      48 1939.19   55.591933.803    60.3 1929.37
    66.7 1925.91   104.6 1927.08   116.2 1924.41     130 1917.51   148.1 1902.39
   168.3 1890.64   172.4 1889.23   204.7 1885.94     241 1884.13   249.2 1882.75
   261.2 1882.41   277.4 1883.03   282.1 1884.05   289.5 1888.03   295.1 1888.56
   383.5 1887.28   394.6 1889.03   402.6 1892.69   418.7 1904.09   447.1 1920.63
   471.3  1936.8   489.5 1946.48   544.1 1968.23   568.3  1976.2     579 1978.22
#Mann= 4 ,-1 , 0
       0      .1       0   55.59     .06       0     241    .045       0
   282.1      .1       0
Bank Sta=241,282.1
XS Rating Curve= 0 ,0
Exp/Cntr(USF)=0,0
Exp/Cntr=0.3,0.1

Type RM Length L Ch R = 1 ,15441   ,149.4,181.6,209.1
XS GIS Cut Line= 3
2439270.03174723580286.8815471472439572.99788932580227.828824536
2439870.82901206579947.970269552
#Sta/Elev= 30
       0 1940.41     4.8 1937.21   15.42 1926.09    21.1 1922.53    37.4 1922.51
    41.5 1921.16    65.9  1902.6    94.4 1888.06  114.79 1886.12   216.7  1888.1
     286 1887.69   363.4 1881.91   372.5 1881.16   398.8 1881.88   404.3 1884.02
   414.3 1893.96     420  1896.8   468.1 1903.56   487.9 1904.69   514.1 1915.15
   541.5 1917.79   565.2 1912.76   571.1  1914.6   596.4 1927.35   606.7  1928.8
     635 1929.22     652 1934.85   677.5 1939.42   693.7 1947.12   717.4 1964.19
#Mann= 5 ,-1 , 0
       0      .1       0   15.42     .06       0  114.79      .1       0
   363.4    .045       0   398.8      .1       0
Bank Sta=363.4,398.8
XS Rating Curve= 0 ,0
Exp/Cntr(USF)=0,0
Exp/Cntr=0.3,0.1

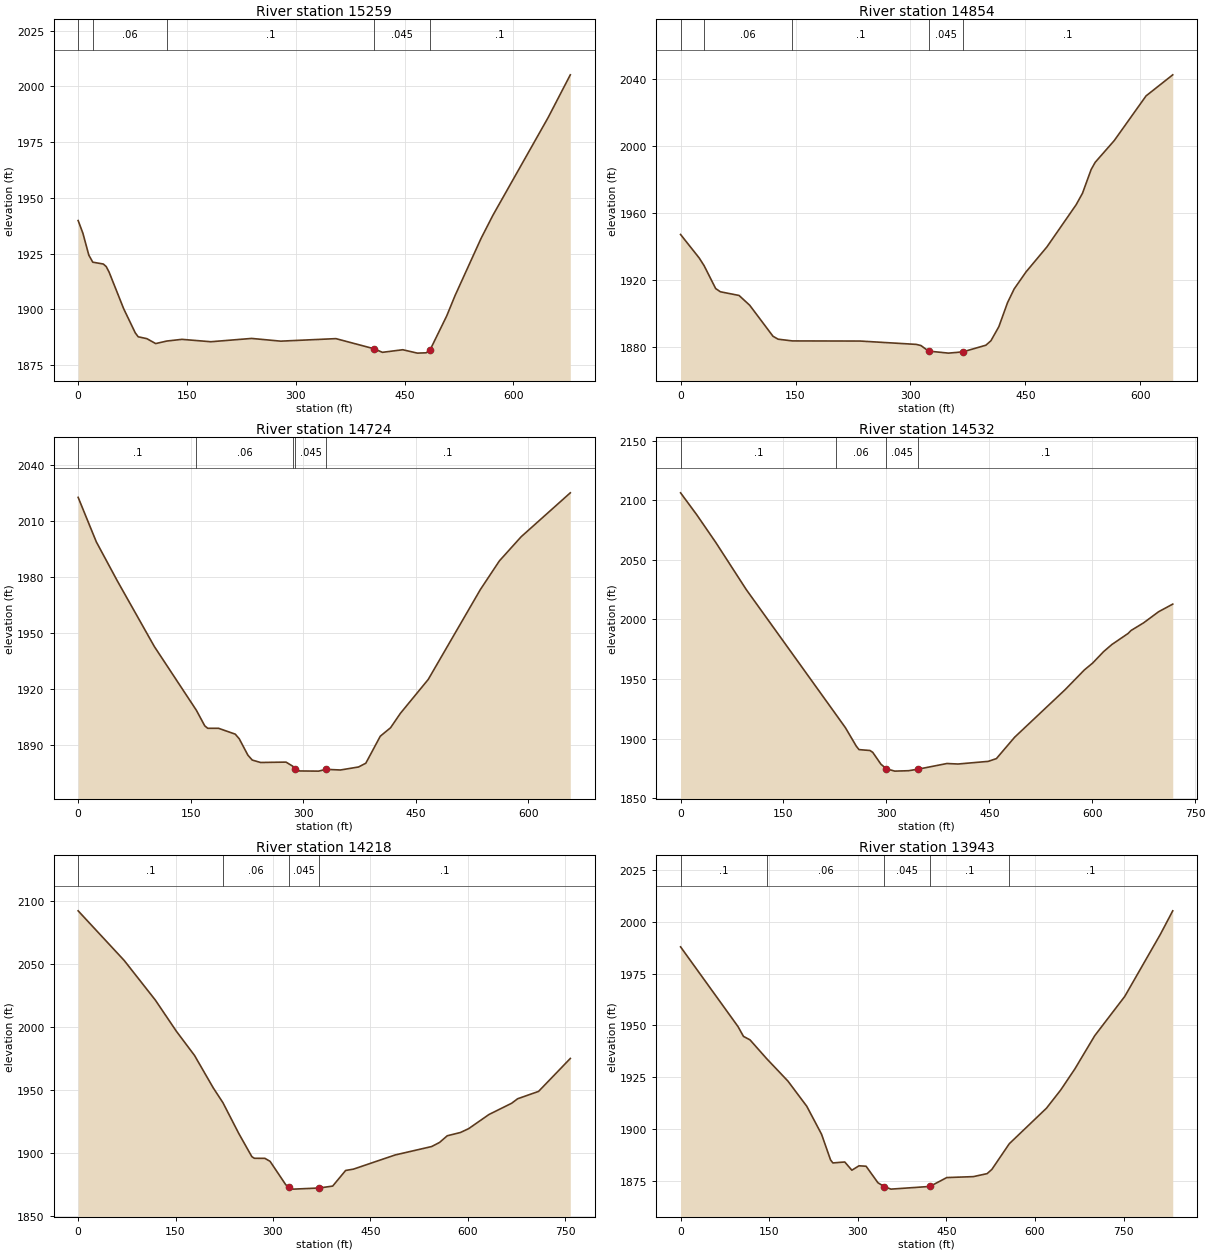
Type RM Length L Ch R = 1 ,15259   ,371.6,405.5,433.9
XS GIS Cut Line= 2
2439268.09750661580301.3269074182439945.09670555580348.286389426
#Sta/Elev= 30
       0 1939.87     6.6 1934.15    14.7 1924.38   20.161921.202    34.7 1920.38
    38.7 1919.23    42.7 1916.74    62.8 1900.31    78.8 1889.49    82.8 1887.75
    94.8  1886.9   106.9  1884.7  122.171885.836     143  1886.6     183 1885.53
   239.2 1887.01   279.3 1885.79   355.4 1886.92   407.6 1882.41   419.6 1880.78
   447.6 1881.94   467.7 1880.42   479.7 1880.56     485 1881.69   508.2 1897.12
   519.8 1906.31   555.5 1931.83   571.9 1942.25   648.1  1986.1   678.6 2005.22
#Mann= 5 ,-1 , 0
       0      .1       0   20.16     .06       0  122.17      .1       0
   407.6    .045       0     485      .1       0
Bank Sta=407.6,485
XS Rating Curve= 0 ,0
Exp/Cntr(USF)=0,0
Exp/Cntr=0.3,0.1

Type RM Length L Ch R = 1 ,14854   ,136.4,129.5,123.7
XS GIS Cut Line= 3
2439244.61776561 580356.112969762439560.16034093580718.223173177
2439716.15983887580761.892201759
#Sta/Elev= 30
       0 1947.17    24.2 1933.19   30.731928.508    45.8 1914.84    51.9 1912.92
    76.3 1910.71    90.2 1904.87   120.6 1886.32   127.3 1884.55  146.04 1883.52
   234.5 1883.44   307.7 1881.44   313.7 1880.75   323.6 1877.44   349.6 1876.22
   368.5 1876.98   398.4 1880.95     405 1883.59   415.4 1892.07   426.7 1906.42
   435.4 1914.65   450.9 1924.83   478.1 1939.75   516.2 1964.94   524.5 1971.82
   535.8 1986.02   541.1 1990.34     566 2003.37   607.5 2030.08   642.3 2042.67
#Mann= 5 ,-1 , 0
       0      .1       0   30.73     .06       0  146.04      .1       0
   323.6    .045       0   368.5      .1       0
Bank Sta=323.6,368.5
XS Rating Curve= 0 ,0
Exp/Cntr(USF)=0,0
Exp/Cntr=0.3,0.1

Type RM Length L Ch R = 1 ,14724   ,209.2,192.2,180
XS GIS Cut Line= 4
2439082.60354068 580610.387766672439264.89672787580625.792824742
2439488.27006992580777.2758957892439680.83329583580841.463637757
#Sta/Elev= 30
       0 2022.78    24.2  1998.9    52.3 1977.87   101.6 1942.67  157.591908.466
   168.7 1900.14   172.7 1898.83     187 1898.83   209.3 1895.69   214.7 1893.17
   226.2 1884.39     232 1881.77   243.1 1880.47     277 1880.67  285.711878.528
   289.6 1877.18   295.3 1875.92   320.5 1875.83   330.1 1876.79   349.5 1876.44
   373.6 1878.05   383.3 1880.07   402.6 1894.57   416.3 1899.12   429.3  1906.8
   466.5 1925.05     536 1973.32   561.3 1988.67   590.3 2001.63   655.8 2025.21
#Mann= 5 ,-1 , 0
       0      .1       0  157.59     .06       0  285.71      .1       0
   289.6    .045       0   330.1      .1       0
Bank Sta=289.6,330.1
XS Rating Curve= 0 ,0
Exp/Cntr(USF)=0,0
Exp/Cntr=0.3,0.1

Type RM Length L Ch R = 1 ,14532   ,313.1,314.1,314.7
XS GIS Cut Line= 2
2438951.12100306580845.2742406692439667.25310367580888.320432509
#Sta/Elev= 30
       0 2106.26    23.7 2087.75    51.7  2064.3    95.8 2025.04  226.451920.308
   240.4 1909.07   256.1 1893.72   260.1  1890.8   276.1 1890.06   280.1 1888.51
   292.1 1878.53   300.1 1874.71   312.2 1872.75   332.2 1873.09   346.2 1874.38
   388.3 1879.14   404.3 1878.71   448.5 1880.94   460.4 1883.27   486.9 1901.17
   560.6 1941.13   588.6 1957.67   600.7 1963.44   616.7 1973.07   628.7 1978.99
   652.4 1988.29   656.7 1990.77   675.1 1997.24   696.8 2006.48   717.4 2012.88
#Mann= 4 ,-1 , 0
       0      .1       0  226.45     .06       0   300.1    .045       0
   346.2      .1       0
Bank Sta=300.1,346.2
XS Rating Curve= 0 ,0
Exp/Cntr(USF)=0,0
Exp/Cntr=0.3,0.1

Type RM Length L Ch R = 1 ,14218   ,277.7,275,275.2
XS GIS Cut Line= 2
2438904.16152105581146.5975835492439659.42652334581213.123516393
#Sta/Elev= 30
       0 2092.14    70.9  2052.8     119  2021.3   151.3 1996.65   179.3 1977.43
   208.2 1951.66  223.081939.944   247.5 1915.51   267.6 1897.16   271.6 1895.86
   287.7 1895.82   295.7 1893.44   319.8 1874.93   324.8 1872.77   331.8 1871.41
   371.1 1872.29   392.1 1873.82   412.1 1886.22     424 1887.25   488.4 1898.51
   544.6 1905.19   556.7 1908.41   568.7 1913.74   588.8  1916.3   601.5 1919.35
     633 1930.62   667.9 1939.54   677.1 1943.09   709.3 1948.92   758.2 1975.04
#Mann= 4 ,-1 , 0
       0      .1       0  223.08     .06       0   324.8    .045       0
   371.1      .1       0
Bank Sta=324.8,371.1
XS Rating Curve= 0 ,0
Exp/Cntr(USF)=0,0
Exp/Cntr=0.3,0.1

Type RM Length L Ch R = 1 ,13943   ,273.5,274,278.8
XS GIS Cut Line= 2
2438821.98242754581412.701314923  2439651.599943581490.967118269
#Sta/Elev= 30
       0 1988.01    97.2  1949.5   106.5 1944.74   117.6 1943.04  146.011933.888
   181.6 1923.18   213.7 1910.94   238.7 1897.43   253.9 1885.05   257.9 1883.56
     278 1884.02     290 1880.04   302.1 1882.18   314.1 1881.97   334.2 1873.97
   345.2 1872.08   356.2  1870.9   422.2  1872.2   450.7 1876.49   495.7 1876.94
     519 1878.39   527.1 1880.45  556.541892.841   619.5 1910.02   643.6 1918.81
   667.7 1929.06   701.2 1945.06     752 1964.03   812.3 1994.04   833.3 2005.43
#Mann= 5 ,-1 , 0
       0      .1       0  146.01     .06       0   345.2    .045       0
   422.2      .1       0  556.54      .1       0
Bank Sta=345.2,422.2
XS Rating Curve= 0 ,0
Exp/Cntr(USF)=0,0
Exp/Cntr=0.3,0.1

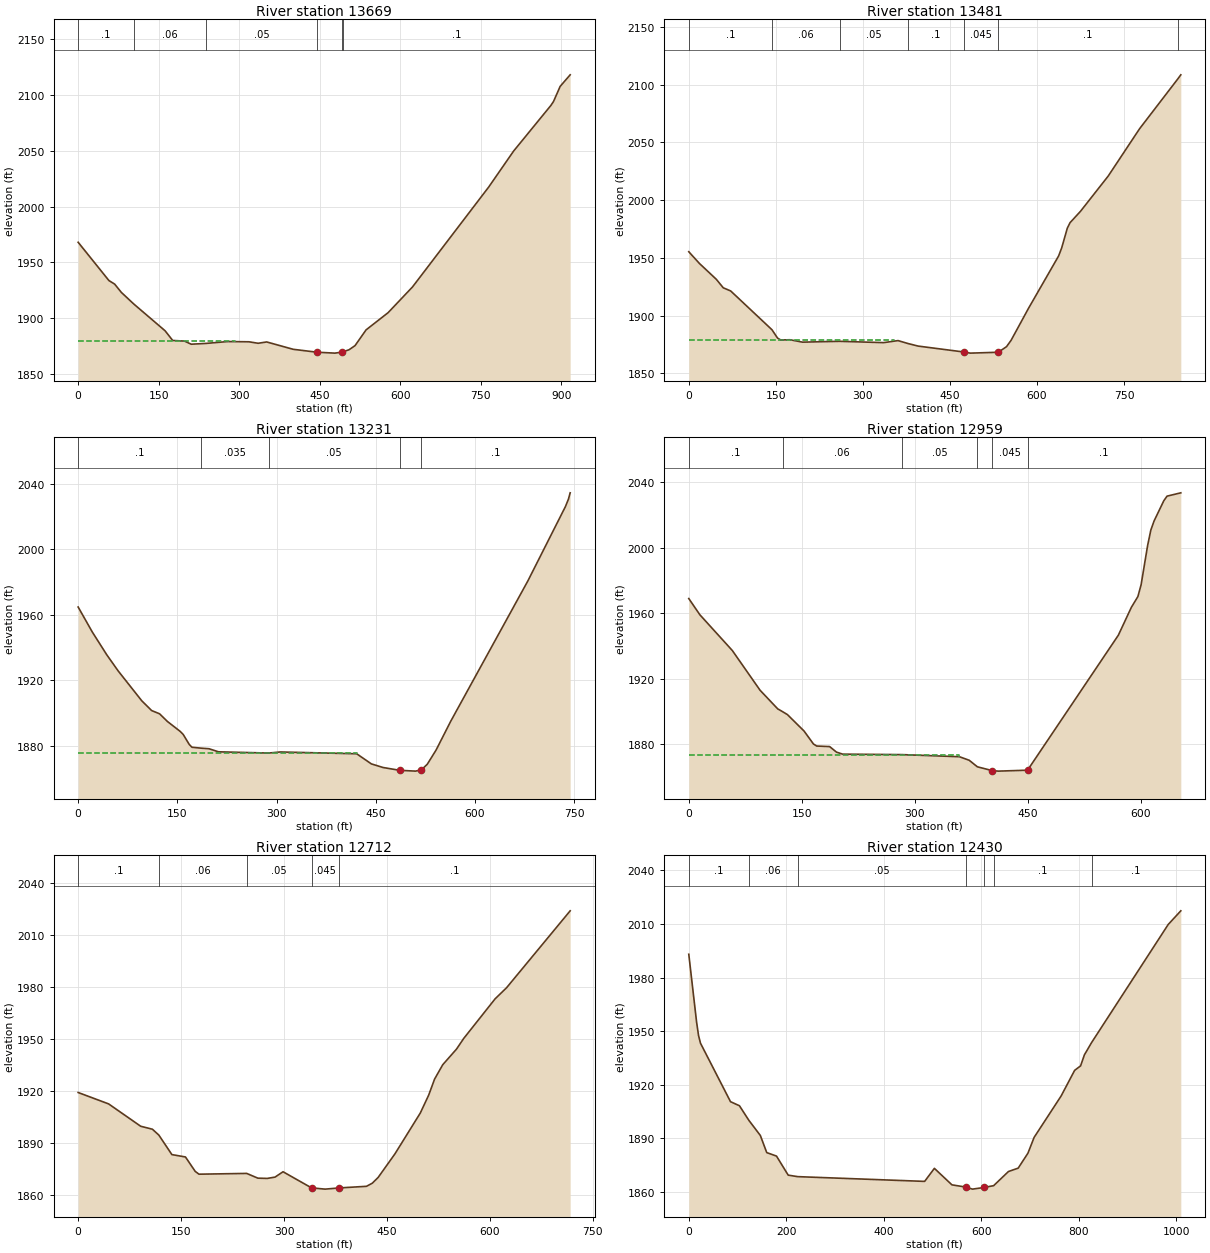
Type RM Length L Ch R = 1 ,13669   ,171.5,187.6,210.6
XS GIS Cut Line= 4
2438829.80900787581447.9209264292439076.34628841581694.458206967
2439369.84305096581764.8974299782439561.59426915 581948.82206784
#Sta/Elev= 30
       0 1968.01    57.3 1933.76      68 1930.56    80.5 1923.12  103.581912.771
   161.9  1888.8   176.1 1880.13   198.1 1879.56   210.6 1876.78  238.041877.491
   278.5 1879.15   318.1 1878.94   335.1 1877.62   351.1  1878.8   400.5 1872.22
   444.8 1869.62   477.9  1868.8   491.2 1869.66  493.851870.042   504.5 1871.83
   515.6  1875.5   536.2 1889.62   577.2 1905.01   622.6 1928.02   764.7 2017.55
   810.9 2049.62   880.3 2090.45   885.2 2093.97   897.6 2107.53   916.2 2117.84
#Mann= 6 ,-1 , 0
       0      .1       0  103.58     .06       0  238.04     .05       0
   444.8    .045       0   491.2     .05       0  493.85      .1       0
#XS Ineff= 2 , 0
          292.66 1879.59
Permanent Ineff=
       F       F
Bank Sta=444.8,491.2
XS Rating Curve= 0 ,0
Exp/Cntr(USF)=0,0
Exp/Cntr=0.3,0.1

Type RM Length L Ch R = 1 ,13481   ,243.4,250.9,260.8
XS GIS Cut Line= 2
2438775.02294553 581518.360149442439342.45001979582148.399866371
#Sta/Elev= 30
       0 1955.29    18.3 1945.14    47.4 1931.42    59.4 1924.03    72.2  1921.3
  143.31 1887.69   152.9 1880.49   158.3 1878.82   174.4 1878.98     196 1876.92
  259.831877.638   335.9  1876.5   360.6 1878.26  377.661875.732   395.1 1873.52
   473.9 1868.38   485.3  1867.4   533.4 1868.16   547.6 1873.02   555.4  1878.5
   585.3 1906.11   637.3 1951.61   642.7 1958.73   652.3 1975.68     657 1980.45
     675 1990.31   722.8 2020.89   776.9 2061.94  842.452104.906   847.9 2108.63
#Mann= 7 ,-1 , 0
       0      .1       0  143.31     .06       0  259.83     .05       0
  377.66      .1       0   473.9    .045       0   533.4      .1       0
  842.45      .1       0
#XS Ineff= 2 , 0
          352.83  1878.4
Permanent Ineff=
       F       F
Bank Sta=473.9,533.4
XS Rating Curve= 0 ,0
Exp/Cntr(USF)=0,0
Exp/Cntr=0.3,0.1

Type RM Length L Ch R = 1 ,13231   ,270.2,271.5,271.6
XS GIS Cut Line= 2
2438681.10398152581573.146211782 2439005.9070654582242.318830385
#Sta/Elev= 30
       0 1964.73    21.3 1949.51    43.2 1935.55    60.3 1925.74    96.2 1907.36
   111.1 1901.39   123.1 1899.41   135.1 1894.67   154.3 1888.64   158.8 1886.78
     168 1880.64   172.1 1878.94  185.941878.389   197.9 1878.03   212.1 1876.16
  287.961875.387   305.5 1876.06   421.1 1874.95   443.3 1868.76   461.1 1866.54
   486.3 1864.83     510 1864.34   518.9 1865.12   527.8 1868.57   541.1 1877.22
   563.3 1894.89   679.8 1980.64   736.7 2026.21   741.2 2030.71   743.8 2034.57
#Mann= 5 ,-1 , 0
       0      .1       0  185.94    .035       0  287.96     .05       0
   486.3    .045       0   518.9      .1       0
#XS Ineff= 2 , 0
          421.29 1875.45
Permanent Ineff=
       F       F
Bank Sta=486.3,518.9
XS Rating Curve= 0 ,0
Exp/Cntr(USF)=0,0
Exp/Cntr=0.3,0.1

Type RM Length L Ch R = 1 ,12959   ,259.6,246.6,236.3
XS GIS Cut Line= 2
2438481.52618299581702.2847873022438724.15017336582308.844763229
#Sta/Elev= 30
       0 1968.98    14.7 1959.08    57.8 1937.24    94.6 1913.01   118.1  1901.6
  124.441899.928     131  1898.1   153.1 1888.05   165.5 1880.17   169.8 1878.91
     187 1878.58   196.1  1875.2   204.3 1873.96  283.061873.674   359.4 1872.38
   372.3 1870.23  383.151866.238   402.8 1863.91     411 1863.59   449.8 1864.16
   570.4 1946.62   587.7 1963.66   596.3 1970.17   600.6 1977.44   609.2 2001.29
   613.5 2010.78   617.8 2016.34   630.7 2028.68     635  2031.5   653.3 2033.53
#Mann= 6 ,-1 , 0
       0      .1       0  124.44     .06       0  283.06     .05       0
  383.15      .1       0   402.8    .045       0   449.8      .1       0
#XS Ineff= 2 , 0
          358.58 1873.55
Permanent Ineff=
       F       F
Bank Sta=402.8,449.8
XS Rating Curve= 0 ,0
Exp/Cntr(USF)=0,0
Exp/Cntr=0.3,0.1

Type RM Length L Ch R = 1 ,12712   ,300.9,282.4,269.6
XS GIS Cut Line= 3
 2438133.2433581581944.9087776732438559.79198633582312.758053396
2438708.49701269582351.890955069
#Sta/Elev= 30
       0 1919.04    44.4 1912.45    91.2 1899.51   108.2 1897.81  117.591894.428
   136.6 1883.13   156.4 1881.76   170.6 1873.42   176.1  1871.8  245.651872.245
   261.9  1869.5   275.5 1869.35   286.9 1870.11   298.6 1873.21   340.1 1863.89
   359.9 1863.16   380.5 1863.85   420.2 1864.79   428.7  1866.6   437.2 1869.92
   461.6 1883.52   498.6 1907.16   510.9 1917.59   519.4 1926.77   531.3 1935.09
   551.4 1944.15   561.9 1950.31   607.7 1973.24   624.3 1979.61     717  2024.1
#Mann= 5 ,-1 , 0
       0      .1       0  117.59     .06       0  245.65     .05       0
   340.1    .045       0   380.5      .1       0
#XS Ineff= 2 , 0
          302.34 1869.72
Permanent Ineff=
       F       F
Bank Sta=340.1,380.5
XS Rating Curve= 0 ,0
Exp/Cntr(USF)=0,0
Exp/Cntr=0.3,0.1

Type RM Length L Ch R = 1 ,12430   ,291.8,281.1,275.1
XS GIS Cut Line= 2
2437698.86814953582430.1567584142438708.49701269 582422.33017808
#Sta/Elev= 30
       0 1993.08      16 1955.17      20 1947.64      24 1943.33    85.6  1910.6
     104 1908.31   123.11900.235   146.9 1891.66     160 1882.09     180 1880.15
     204 1869.49  223.591868.646     484 1865.99     504 1873.28     540 1864.06
     568 1862.82   582.2 1861.66   605.5 1862.58  625.551863.589     656 1871.51
     676 1873.41     696 1881.79   708.7 1890.63     764 1913.74   791.8 1928.12
     804 1930.62   811.9 1936.82  826.531943.642   983.9 2009.77  1009.7 2017.39
#Mann= 7 ,-1 , 0
       0      .1       0   123.1     .06       0  223.59     .05       0
     568    .045       0   605.5     .05       0  625.55      .1       0
  826.53      .1       0
#XS Ineff= 2 , 0
          502.33 1867.74
Permanent Ineff=
       F       F
Bank Sta=568,605.5
XS Rating Curve= 0 ,0
Exp/Cntr(USF)=0,0
Exp/Cntr=0.3,0.1

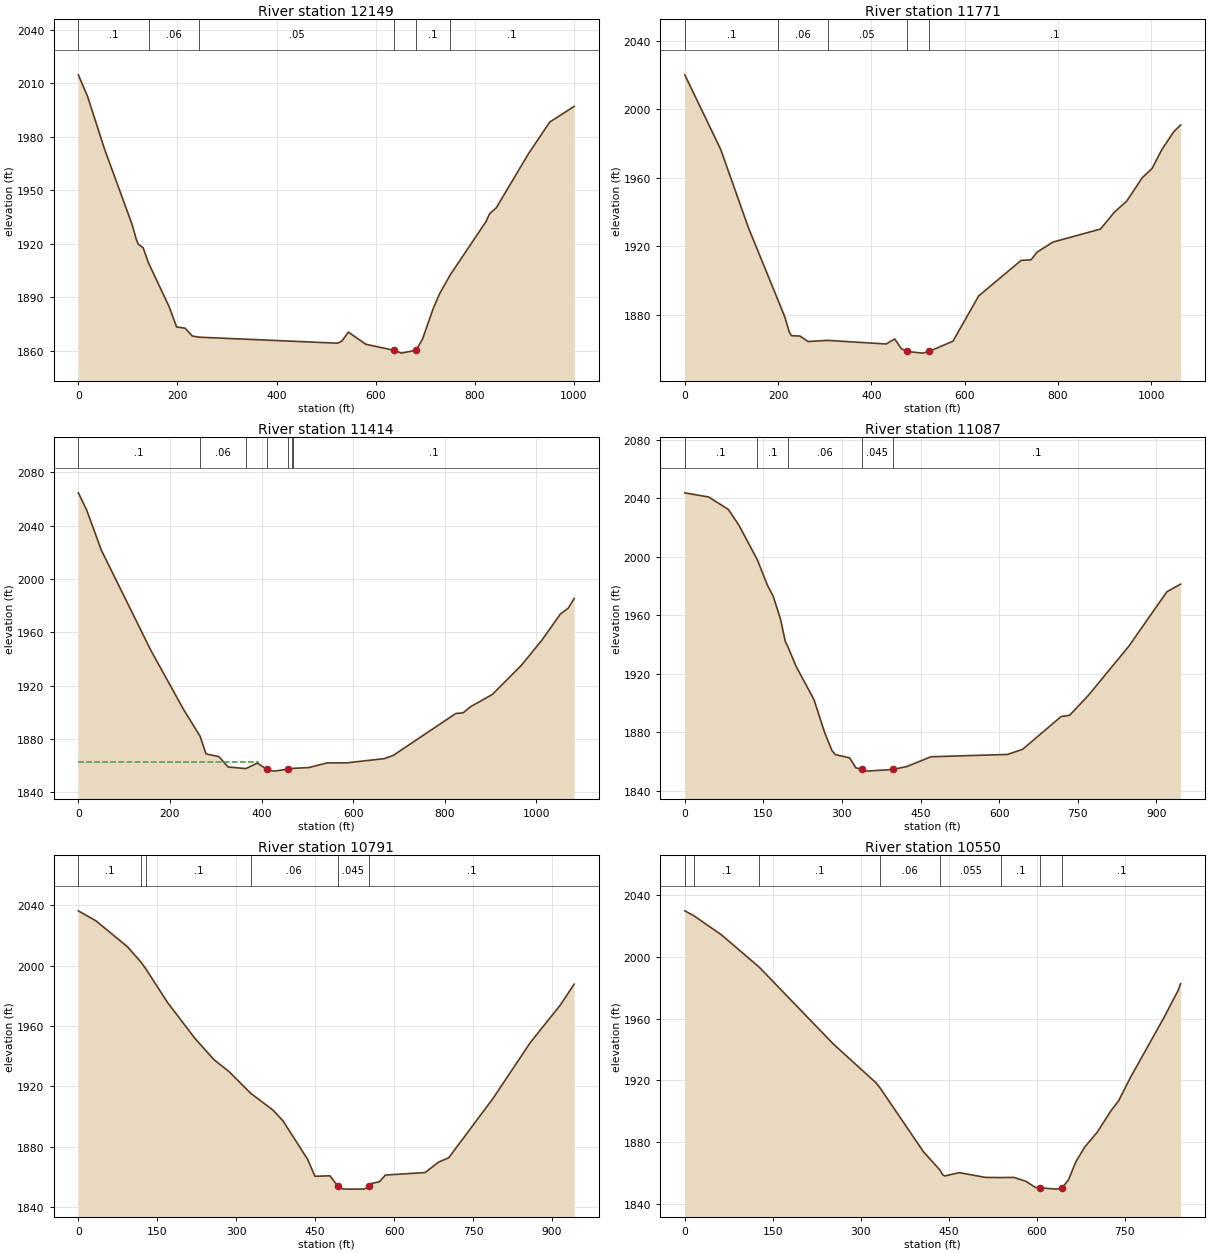
Type RM Length L Ch R = 1 ,12149   ,383,377.6,373.2
XS GIS Cut Line= 2
2437761.48079221582923.2313194912438696.75714219582567.121914269
#Sta/Elev= 30
       0 2014.85    18.6 2002.76    52.9 1973.16   108.5 1930.87   117.1 1922.38
   121.3 1919.65   130.8 1917.78  141.681909.242   183.2 1884.71   198.4 1873.29
   215.5 1872.61     230 1868.21  243.081867.565   523.6 1864.18   532.2 1865.45
     545 1870.41   580.2  1863.6   637.91860.124     652  1858.6     682 1860.25
   694.8 1866.53   716.2 1883.59     729 1891.82  750.091902.276   823.2 1932.62
     830 1936.81   843.7 1940.21   908.8 1970.65   951.6 1988.34  1000.8 1997.14
#Mann= 6 ,-1 , 0
       0      .1       0  141.68     .06       0  243.08     .05       0
   637.9    .045       0     682      .1       0  750.09      .1       0
#XS Ineff= 2 , 0
          539.55 1867.11
Permanent Ineff=
       F       F
Bank Sta=637.9,682
XS Rating Curve= 0 ,0
Exp/Cntr(USF)=0,0
Exp/Cntr=0.3,0.1

Type RM Length L Ch R = 1 ,11771   ,377.7,357.3,321.4
XS GIS Cut Line= 3
2437976.71175141583310.6470460512438548.05211583   582981.930672
2438685.01727168582602.341525774
#Sta/Elev= 30
       0 2020.09    76.9 1976.63   136.3 1930.95  199.871888.581   214.6 1878.67
     224 1869.98   228.6 1867.91   246.8 1867.69   264.3 1864.49  306.041865.172
   431.6 1863.07   450.1 1865.97   463.9 1860.38   476.2 1858.69   510.1 1857.73
   523.9 1858.79   574.7 1864.69     630 1891.14   720.9 1911.85   742.2 1912.16
   754.9 1916.64   788.9  1922.5     891 1930.12   920.8    1940   947.3 1946.45
   980.3 1960.01  1001.5 1965.45  1022.8 1976.63  1048.3 1986.99  1062.7 1990.82
#Mann= 5 ,-1 , 0
       0      .1       0  199.87     .06       0  306.04     .05       0
   476.2    .045       0   523.9      .1       0
#XS Ineff= 2 , 0
           445.9 1864.25
Permanent Ineff=
       F       F
Bank Sta=476.2,523.9
XS Rating Curve= 0 ,0
Exp/Cntr(USF)=0,0
Exp/Cntr=0.3,0.1

Type RM Length L Ch R = 1 ,11414   ,341.4,326.5,300.2
XS GIS Cut Line= 2
2438626.31791918583701.9760627782438696.75714219582621.907976611
#Sta/Elev= 30
       0 2064.61    18.3 2051.62    50.3 2021.56   158.5  1946.3   230.7 1901.49
   265.81882.029   278.8 1868.75   306.8  1866.7   326.9 1858.93  365.731857.733
     391 1861.87     411 1857.14   427.1 1855.82   457.8 1857.29  465.651857.734
  468.621857.897   503.5 1858.51   543.3 1862.04   585.7 1862.01   667.6 1865.19
   687.6 1867.62   823.9 1899.05   839.9 1899.53   855.9 1904.07     904 1913.39
   968.2 1935.59  1012.3 1954.25  1052.3 1973.69  1069.5 1978.07  1082.4  1985.3
#Mann= 7 ,-1 , 0
       0      .1       0   265.8     .06       0  365.73     .05       0
     411    .045       0   457.8     .05       0  465.65    .025       0
  468.62      .1       0
#XS Ineff= 2 , 0
          392.21 1862.78
Permanent Ineff=
       F       F
Bank Sta=411,457.8
XS Rating Curve= 0 ,0
Exp/Cntr(USF)=0,0
Exp/Cntr=0.3,0.1

Type RM Length L Ch R = 1 ,11087   ,305.9,296.5,287.6
XS GIS Cut Line= 3
2439154.61209176583435.8723314032438751.54320453582876.271837483
2438716.32359302582621.907976611
#Sta/Elev= 30
       0 2043.63    45.8 2040.76    83.1 2032.28   103.6 2021.34  138.361997.957
   157.8 1980.47     169 1972.69   182.5 1957.58   191.9 1941.97  196.421938.739
   212.4 1925.13   246.6 1902.32   266.7 1880.11   280.8 1867.58   287.2 1864.81
   314.6 1862.53   326.6 1855.72   338.1 1854.66   346.7 1853.48   396.7 1854.61
   424.1 1856.66   469.9 1863.29     616 1864.88   644.7 1868.36   718.3 1890.78
   734.5 1891.62   770.8 1905.43   847.6 1938.86   920.2 1976.05   946.4 1981.26
#Mann= 5 ,-1 , 0
       0      .1       0  138.36      .1       0  196.42     .06       0
   338.1    .045       0   396.7      .1       0
Bank Sta=338.1,396.7
XS Rating Curve= 0 ,0
Exp/Cntr(USF)=0,0
Exp/Cntr=0.3,0.1

Type RM Length L Ch R = 1 ,10791   ,207.9,241.2,262.3
XS GIS Cut Line= 4
2439158.52538192583384.9995592292439182.00512293582954.537640829
2438962.86087356582778.4395833012438872.85519971582567.121914269
#Sta/Elev= 30
       0 2036.28    33.3 2029.69    93.3 2012.47  119.192002.225  128.231997.814
   169.4 1975.54   221.6 1951.66   257.6 1937.62   285.6 1929.89  327.611915.251
   369.8 1904.18   388.8 1897.03   435.4 1871.64   449.6 1860.27     478 1860.59
   492.9 1853.84     502 1851.88   517.4 1851.76   543.5 1851.82     552 1853.53
   557.7 1855.59   571.9 1856.64   583.3 1861.08   658.9 1862.77   684.4 1869.68
   703.6 1872.55   787.5 1911.77   858.5 1948.89   915.5 1973.77   941.9 1987.69
#Mann= 6 ,-1 , 0
       0      .1       0  119.19      .1       0  128.23      .1       0
  327.61     .06       0   492.9    .045       0     552      .1       0
Bank Sta=492.9,552
XS Rating Curve= 0 ,0
Exp/Cntr(USF)=0,0
Exp/Cntr=0.3,0.1

Type RM Length L Ch R = 1 ,10550   ,243.4,270.5,289
XS GIS Cut Line= 2
2439178.09183276583377.1729788942439318.97027878582543.642173265
#Sta/Elev= 30
       0 2030.02   15.172026.905    62.2 2014.54  127.24 1993.34   252.9 1943.75
   325.9 1918.48  332.831915.187     407 1873.67  435.631861.547   439.5 1858.86
   443.5 1857.99   467.9 1860.15   512.5 1857.06  538.431856.957   561.2 1857.06
   581.5 1854.54   597.7  1850.6   605.8  1850.3   634.2 1849.45   643.7 1850.47
   654.1  1855.4   666.6 1867.01   681.8 1876.73   702.7 1886.11   726.9 1900.45
   739.6 1906.73   759.9 1921.93   817.2  1960.9   841.1 1978.39   845.4 1982.74
#Mann= 8 ,-1 , 0
       0      .1       0   15.17      .1       0  127.24      .1       0
  332.83     .06       0  435.63    .055       0  538.43      .1       0
   605.8    .045       0   643.7      .1       0
Bank Sta=605.8,643.7
XS Rating Curve= 0 ,0
Exp/Cntr(USF)=0,0
Exp/Cntr=0.3,0.1

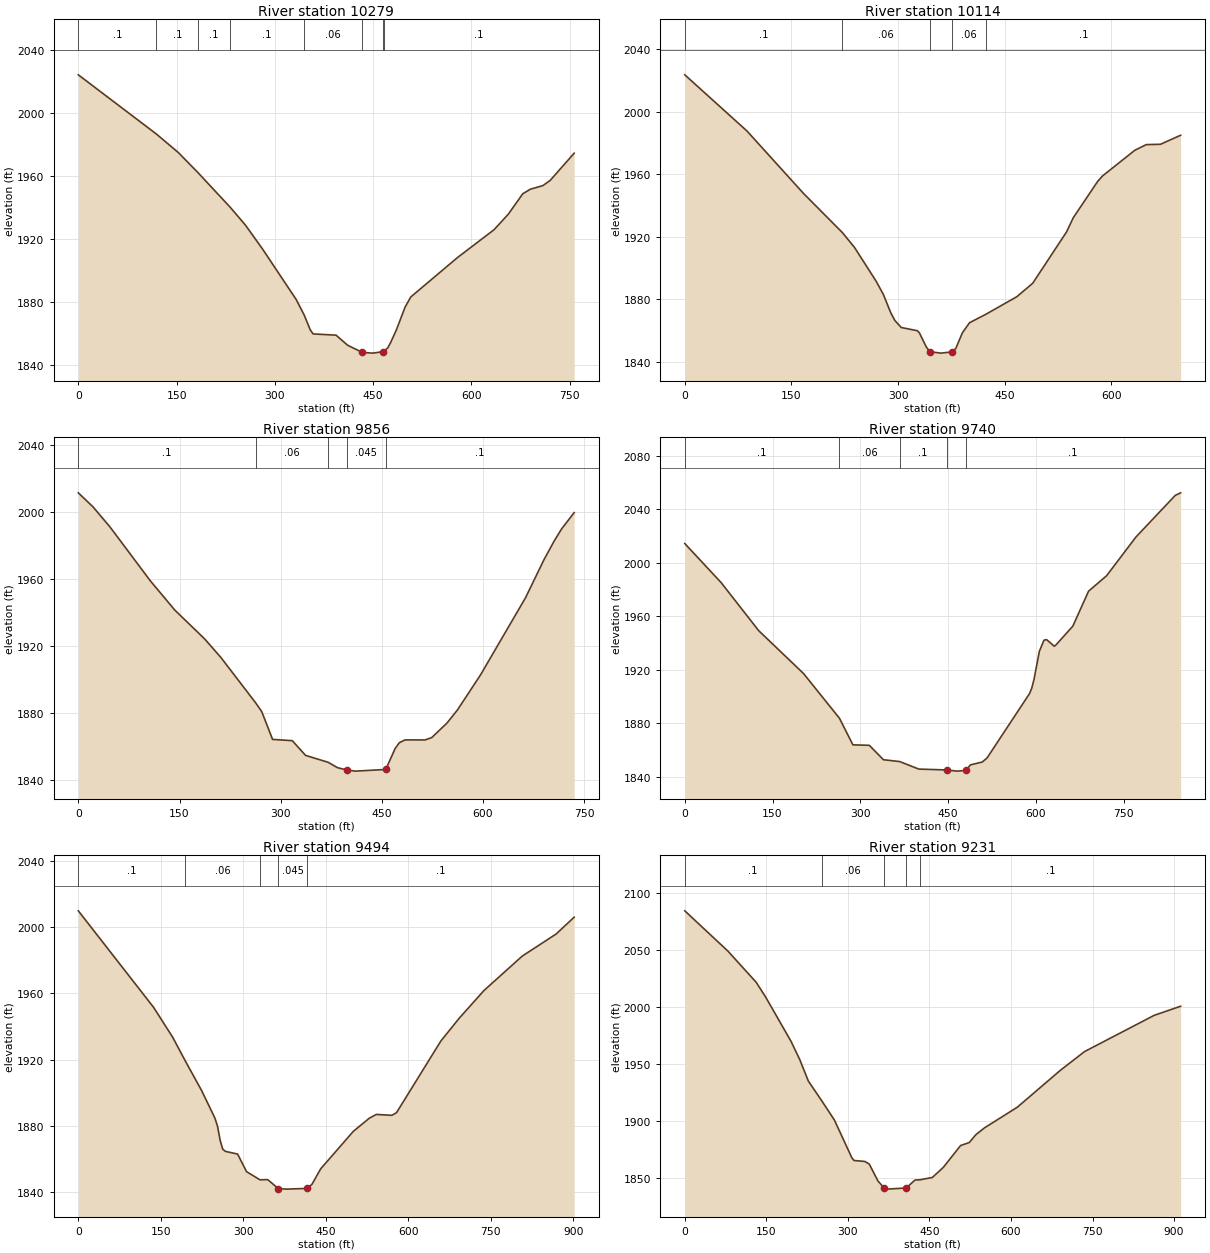
Type RM Length L Ch R = 1 ,10279   ,169.6,165.5,160
XS GIS Cut Line= 3
 2439186.7680739583358.1267773272439312.30022573583034.745038376
 2439686.1677214582866.914009301
#Sta/Elev= 30
       0 2023.99  119.251986.383   152.7 1974.65  182.841961.809  231.921939.891
   255.2 1928.53   281.4 1913.29   332.5  1881.4  344.591871.643   353.9 1862.21
   358.3 1859.57   393.3 1858.79   410.9 1852.41   433.4 1847.82   449.3 1847.38
   465.2 1848.31  466.511848.611   472.3 1850.75   476.7 1854.18   485.4 1862.12
   498.6  1876.5   507.4 1883.03   578.6 1908.01   634.5 1925.72   656.2 1935.55
   678.3 1948.52   689.8 1951.39     709  1953.7   720.1 1956.99   756.7 1974.24
#Mann= 8 ,-1 , 0
       0      .1       0  119.25      .1       0  182.84      .1       0
  231.92      .1       0  344.59     .06       0   433.4    .045       0
   465.2     .06       0  466.51      .1       0
Bank Sta=433.4,465.2
XS Rating Curve= 0 ,0
Exp/Cntr(USF)=0,0
Exp/Cntr=0.3,0.1

Type RM Length L Ch R = 1 ,10114   ,256.9,258.1,259.8
XS GIS Cut Line= 2
2439189.83170326583361.5198182252439741.60561685582934.971189992
#Sta/Elev= 30
       0 2023.77    87.4  1987.8   167.2 1947.66  221.671922.686   238.7 1913.18
   269.1 1891.54   279.2 1883.13   289.8 1871.22   295.5 1866.34   304.5 1861.86
   326.9 1859.82   329.8 1858.58   339.8 1849.28   344.9 1846.36   360.1 1845.44
   375.6 1846.21   381.1 1848.38   390.4 1858.41   400.5 1864.92  423.631870.368
   467.1 1881.61   489.4 1890.23     537 1923.13   546.4  1932.2   580.7 1955.46
   587.6 1958.99     633 1975.43   649.1 1979.05   669.1 1979.27   697.4 1985.05
#Mann= 5 ,-1 , 0
       0      .1       0  221.67     .06       0   344.9    .045       0
   375.6     .06       0  423.63      .1       0
Bank Sta=344.9,375.6
XS Rating Curve= 0 ,0
Exp/Cntr(USF)=0,0
Exp/Cntr=0.3,0.1

Type RM Length L Ch R = 1 ,9856    ,96.5,115.8,129.2
XS GIS Cut Line= 3
2439228.96460494583373.2596887272439538.11452815583412.392590399
2439882.48406287583165.855309861
#Sta/Elev= 30
       0 2011.28    21.7 2002.92    46.8 1990.99   106.6 1958.81   142.9 1941.32
   187.2 1924.08   211.4 1912.94  262.721885.974   271.9 1880.67     288 1864.04
   317.2 1863.29   336.9 1854.49  370.131850.413   384.1 1847.19   398.1 1845.78
   410.7  1845.1   455.8 1846.09   469.7 1858.62   475.9 1862.05   484.4 1863.75
     514 1863.72   523.8 1865.08   546.3 1873.69   561.9 1881.52   596.3 1902.58
   663.1  1948.7   690.5 1971.47   705.8 1982.73   716.7 1989.86   735.1 1999.45
#Mann= 5 ,-1 , 0
       0      .1       0  262.72     .06       0  370.13      .1       0
   398.1    .045       0   455.8      .1       0
Bank Sta=398.1,455.8
XS Rating Curve= 0 ,0
Exp/Cntr(USF)=0,0
Exp/Cntr=0.3,0.1

Type RM Length L Ch R = 1 ,9740    ,232.4,245.8,252.9
XS GIS Cut Line= 3
2439228.96460494583392.826139563 2439831.6112907 583455.43878224
 2440046.8422499583345.866657556
#Sta/Elev= 30
       0 2014.33    62.1 1985.15   126.4 1949.16   202.8 1917.22  264.311883.741
   287.3 1863.85   315.4 1863.48   339.5 1852.72   367.21851.348   399.9 1845.73
   447.4 1845.06   465.3 1844.19   480.3 1844.72   488.3 1848.87   508.4    1851
   516.5 1853.98   588.9 1901.96   592.9 1906.08   596.9 1912.89   605.9 1933.62
   613.8 1942.09   618.3 1942.52   631.6 1937.55   634.7  1938.7   663.2 1952.59
   690.1 1978.75   720.9 1990.27   770.9 2019.16   838.2 2050.34   847.4 2052.26
#Mann= 5 ,-1 , 0
       0      .1       0  264.31     .06       0   367.2      .1       0
   447.4    .045       0   480.3      .1       0
Bank Sta=447.4,480.3
XS Rating Curve= 0 ,0
Exp/Cntr(USF)=0,0
Exp/Cntr=0.3,0.1

Type RM Length L Ch R = 1 ,9494    ,279.6,263,244.8
XS GIS Cut Line= 3
2439248.53105577583428.045751069  2439675.079684583713.715933279
2440054.66883023583795.895026792
#Sta/Elev= 30
       0 2009.72   136.9 1951.52   171.5 1933.57  194.421919.301   224.1 1901.43
   248.1    1885     253 1880.13     258 1871.29   262.6 1866.07   267.4 1864.71
   289.7 1863.07   305.9 1852.49  330.261847.561   344.5 1847.65   363.7 1842.28
   378.1 1841.93   416.6 1842.36   425.2 1844.97   440.7 1854.13   500.1 1876.75
   529.3  1884.7   541.9 1886.96   570.3 1886.44   578.7 1888.02   659.4 1931.25
     693 1945.07     738 1961.75   807.4 1982.43     869 1995.74   901.8 2005.88
#Mann= 5 ,-1 , 0
       0      .1       0  194.42     .06       0  330.26      .1       0
   363.7    .045       0   416.6      .1       0
Bank Sta=363.7,416.6
XS Rating Curve= 0 ,0
Exp/Cntr(USF)=0,0
Exp/Cntr=0.3,0.1

Type RM Length L Ch R = 1 ,9231    ,420.1,405.2,386.5
XS GIS Cut Line= 2
2439115.47919008583897.6405711412440027.27579906583878.074120305
#Sta/Elev= 30
       0 2084.08    79.3 2048.76   131.3  2021.4   148.6 2008.55   195.3 1969.68
   211.3 1953.76   227.3 1934.71  251.761917.551   275.3 1900.46   307.3 1867.41
   311.3 1865.07   331.3 1864.21   339.3 1861.92   355.3  1847.1   367.3 1840.53
   371.3 1839.94   407.3 1840.94   423.3 1847.87  433.211848.173   455.3 1850.16
   475.3 1858.92   507.3 1878.17   523.3 1880.83   535.3 1887.68   551.3 1893.71
   611.3  1911.7   691.3 1944.36   735.3  1960.6   863.4  1992.4     912 2000.38
#Mann= 5 ,-1 , 0
       0      .1       0  251.76     .06       0   367.3    .045       0
   407.3     .06       0  433.21      .1       0
Bank Sta=367.3,407.3
XS Rating Curve= 0 ,0
Exp/Cntr(USF)=0,0
Exp/Cntr=0.3,0.1