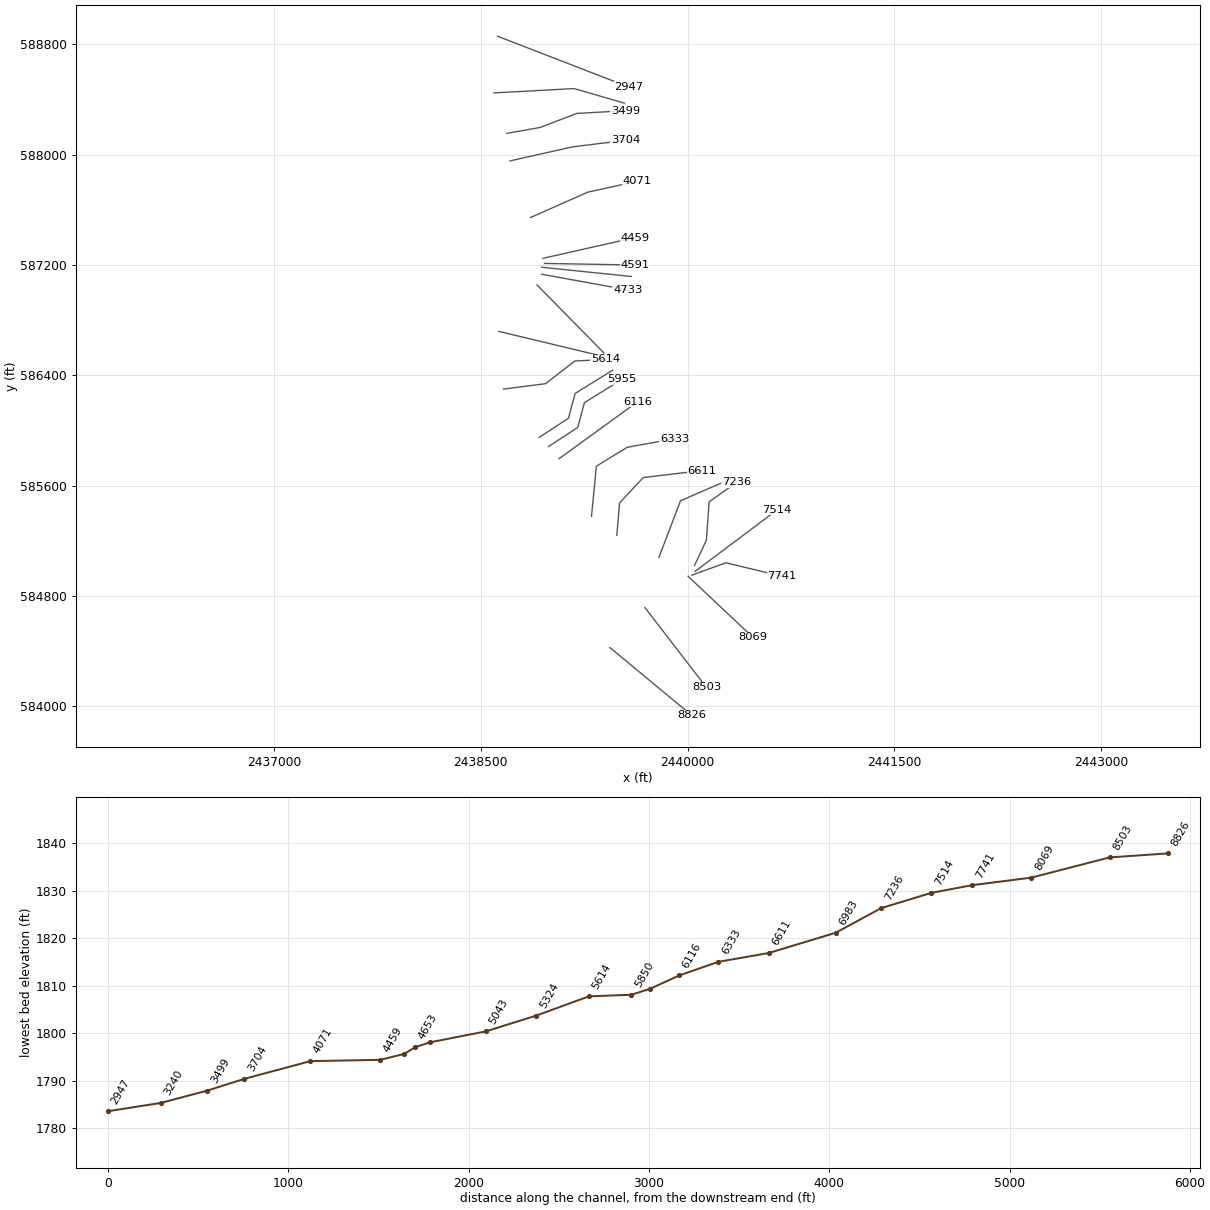
HEC-RAS study THORNCK.prj: THORNCK

--- THORNCK.g01 (geometry) --- (continued)

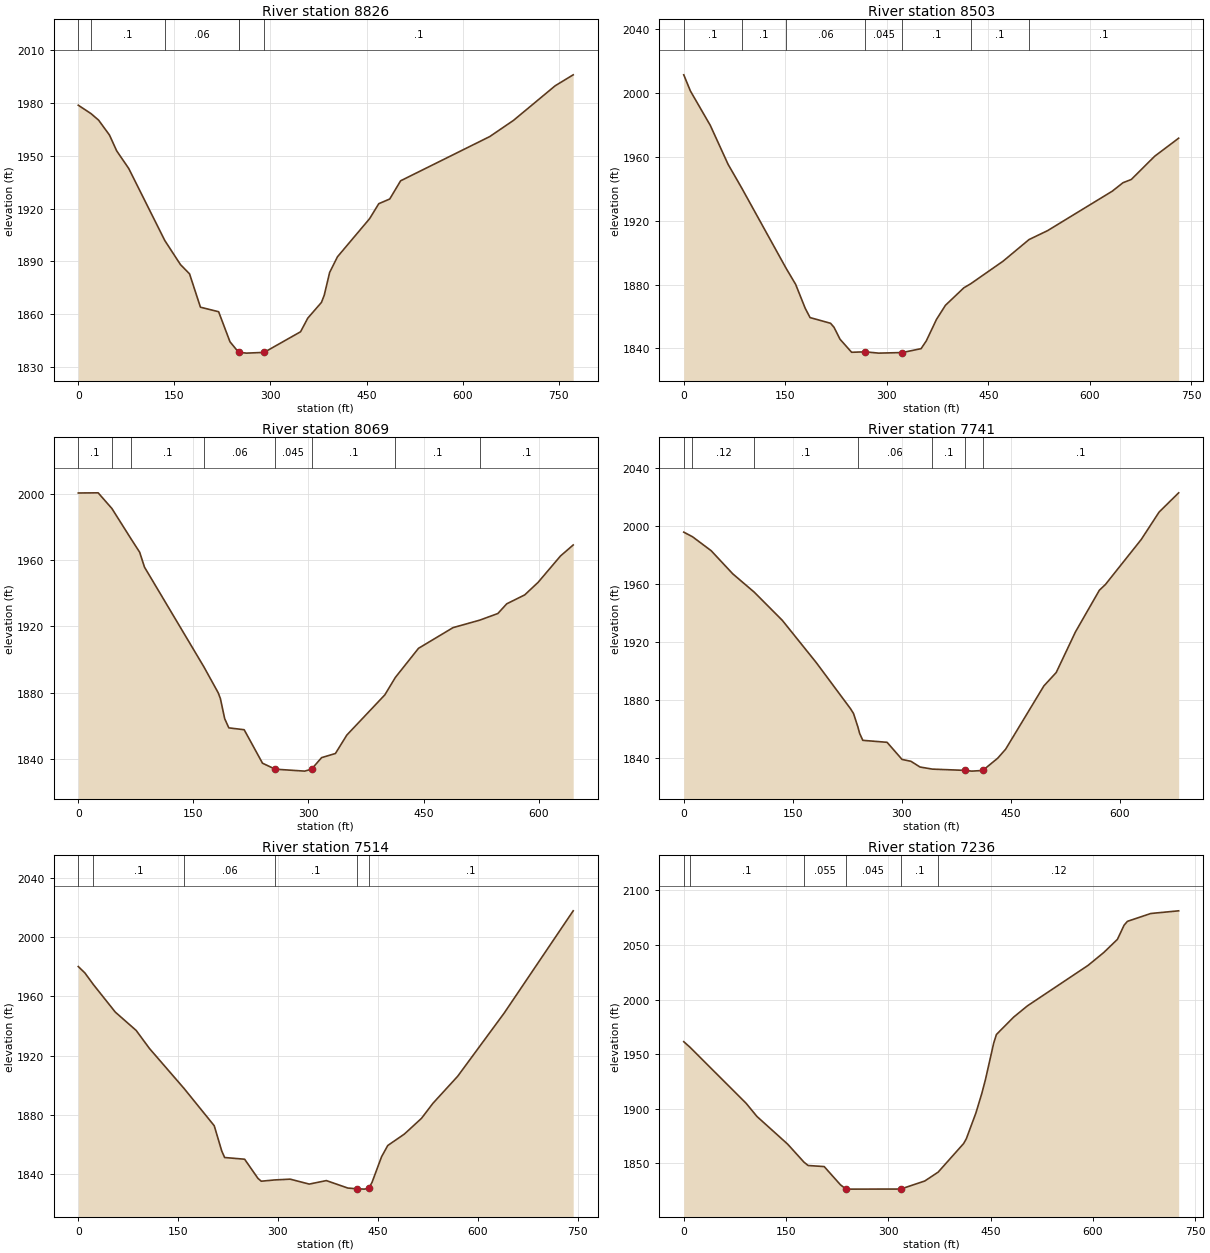
Type RM Length L Ch R = 1 ,8826    ,329.1,322.9,316
XS GIS Cut Line= 2
 2439436.3689838584425.9347437232440031.18908923583932.860182647
#Sta/Elev= 30
       0 1978.69   19.861973.921    31.7 1970.22    48.7 1961.76    59.9  1952.8
    78.7  1942.8  135.071901.851   159.5  1888.2   173.7 1882.92   190.7 1863.99
   219.1 1861.41   236.8 1844.37  250.271838.388   250.4 1838.36   262.8 1837.91
   290.1 1838.33     347 1850.04   358.3  1857.8   379.6 1866.71   383.9 1870.73
   392.4 1883.73   404.6 1892.61   454.8 1914.28   469.1 1922.77   486.2 1925.43
   503.2 1935.77   642.4  1960.9   679.3 1970.05   744.6 1989.77   772.6 1995.95
#Mann= 6 ,-1 , 0
       0      .1       0   19.86      .1       0  135.07     .06       0
  250.27      .1       0   250.4    .045       0   290.1      .1       0
Bank Sta=250.4,290.1
XS Rating Curve= 0 ,0
Exp/Cntr(USF)=0,0
Exp/Cntr=0.3,0.1

Type RM Length L Ch R = 1 ,8503    ,429.5,433.8,438.6
XS GIS Cut Line= 2
2439690.73284467584715.5182161012440136.84792374584136.351271345
#Sta/Elev= 30
       0 2011.44     9.9 2001.28    39.2 1979.78    65.5 1955.37   85.541940.604
  151.331890.138   165.3 1880.16   179.5 1865.11   186.6 1859.34   216.9 1855.77
     222 1853.24   230.9 1845.76     248 1837.59   267.9  1837.9   287.9 1837.07
   322.9 1837.43   350.6 1839.87   358.3 1844.73   373.4 1858.23   386.6 1867.04
   413.8    1878  423.741880.481   471.8  1894.7   510.1 1908.23   537.4 1913.79
     633 1938.53   648.8 1943.82   661.2 1945.89   695.7 1960.44   731.1 1971.74
#Mann= 7 ,-1 , 0
       0      .1       0   85.54      .1       0  151.33     .06       0
   267.9    .045       0   322.9      .1       0  423.74      .1       0
   510.1      .1       0
Bank Sta=267.9,322.9
XS Rating Curve= 0 ,0
Exp/Cntr(USF)=0,0
Exp/Cntr=0.3,0.1

Type RM Length L Ch R = 1 ,8069    ,320.9,328.2,340.2
XS GIS Cut Line= 2
2440003.79605806584942.4890458032440473.39087813584500.287256901
#Sta/Elev= 30
       0 2000.42    25.9 2000.52    43.81991.078   68.421973.025      80 1964.72
    86.3 1955.73  163.691895.659   182.3 1880.07   185.2 1876.56   190.8 1864.43
   196.2 1858.88   216.2 1857.76   240.1 1837.58   256.6 1833.99   295.1 1832.81
     304    1834   317.1 1840.94   335.1 1843.43     350 1854.55   399.5 1878.76
  413.241889.277   443.4 1906.82   488.4 1919.28  523.381923.818   546.8 1927.79
   558.4 1933.64   581.8    1939   599.3 1946.59   628.4 1962.44     645  1969.1
#Mann= 8 ,-1 , 0
       0      .1       0    43.8     .12       0   68.42      .1       0
  163.69     .06       0   256.6    .045       0     304      .1       0
  413.24      .1       0  523.38      .1       0
Bank Sta=256.6,304
XS Rating Curve= 0 ,0
Exp/Cntr(USF)=0,0
Exp/Cntr=0.3,0.1

Type RM Length L Ch R = 1 ,7741    ,217.4,226.8,243.7
XS GIS Cut Line= 3
2440031.18908923584950.3156261382440277.72636976585040.321299985
2440684.70854716584942.489045803
#Sta/Elev= 30
       0 1995.73   12.031992.577    37.7 1982.97    67.5 1967.01   97.061954.386
   135.7 1934.97   182.5 1905.83   229.3 1874.29   233.6 1870.92  239.721861.471
   242.1  1857.1   246.4 1852.41   279.8 1851.04   300.4 1839.26   312.7 1837.96
   325.1 1834.04  342.171832.592   386.4 1831.73   396.4 1831.21   411.4 1831.66
     432  1840.1   442.9  1846.3   495.5 1889.84   512.5 1899.08     539 1927.06
   571.9 1955.75   580.1 1959.61   629.5 1990.67   654.1 2009.56     681  2022.8
#Mann= 7 ,-1 , 0
       0      .1       0   12.03     .12       0   97.06      .1       0
  239.72     .06       0  342.17      .1       0   386.4    .045       0
   411.4      .1       0
Bank Sta=386.4,411.4
XS Rating Curve= 0 ,0
Exp/Cntr(USF)=0,0
Exp/Cntr=0.3,0.1

Type RM Length L Ch R = 1 ,7514    ,264.8,278.3,292.7
XS GIS Cut Line= 2
2440054.66883023584977.7086573082440649.48893566585423.823736377
#Sta/Elev= 30
       0 1980.27     9.9 1975.96   22.661968.088    55.6 1949.43      87    1937
     107 1924.76  158.931897.728   204.2 1872.53   215.6 1855.31   219.9 1850.99
   249.9 1849.84   269.9 1836.88   274.9 1834.95   295.21835.819   318.4 1836.33
     347    1833   372.7 1835.37   404.9 1830.32   418.4 1829.83   429.8 1829.59
   436.5 1830.26   441.3 1834.18   455.6  1851.5   464.9 1859.11   489.9 1866.87
   515.6 1877.51   532.7 1887.64   569.9 1905.96   639.9 1948.83   743.5 2017.99
#Mann= 6 ,-1 , 0
       0     .12       0   22.66      .1       0  158.93     .06       0
   295.2      .1       0   418.4    .045       0   436.5      .1       0
Bank Sta=418.4,436.5
XS Rating Curve= 0 ,0
Exp/Cntr(USF)=0,0
Exp/Cntr=0.3,0.1

Type RM Length L Ch R = 1 ,7236    ,270.9,253.4,248.1
XS GIS Cut Line= 4
2440050.75554006585020.7548491482440136.84792374 585204.67948701
2440156.41437458585482.5230888872440355.99217311585623.401534908
#Sta/Elev= 30
       0 1961.38    8.96 1956.42    91.5 1904.97   107.3 1892.95   152.5 1867.51
  176.391851.041   182.5    1848     206 1847.02   229.9 1830.29   237.4 1826.72
   242.1 1826.37   318.3 1826.44   353.6 1833.84  373.111841.913   410.5  1868.1
   414.5 1872.56   428.5 1896.07   437.2 1914.02   442.6 1926.89   454.6 1960.01
   458.6 1967.96   483.9 1983.88     504 1994.15     593 2031.24     616    2043
   636.1 2055.11   645.9  2068.1   650.8 2071.59     685 2078.77   725.9 2081.21
#Mann= 6 ,-1 , 0
       0     .12       0    8.96      .1       0  176.39    .055       0
   237.4    .045       0   318.3      .1       0  373.11     .12       0
Bank Sta=237.4,318.3
XS Rating Curve= 0 ,0
Exp/Cntr(USF)=0,0
Exp/Cntr=0.3,0.1

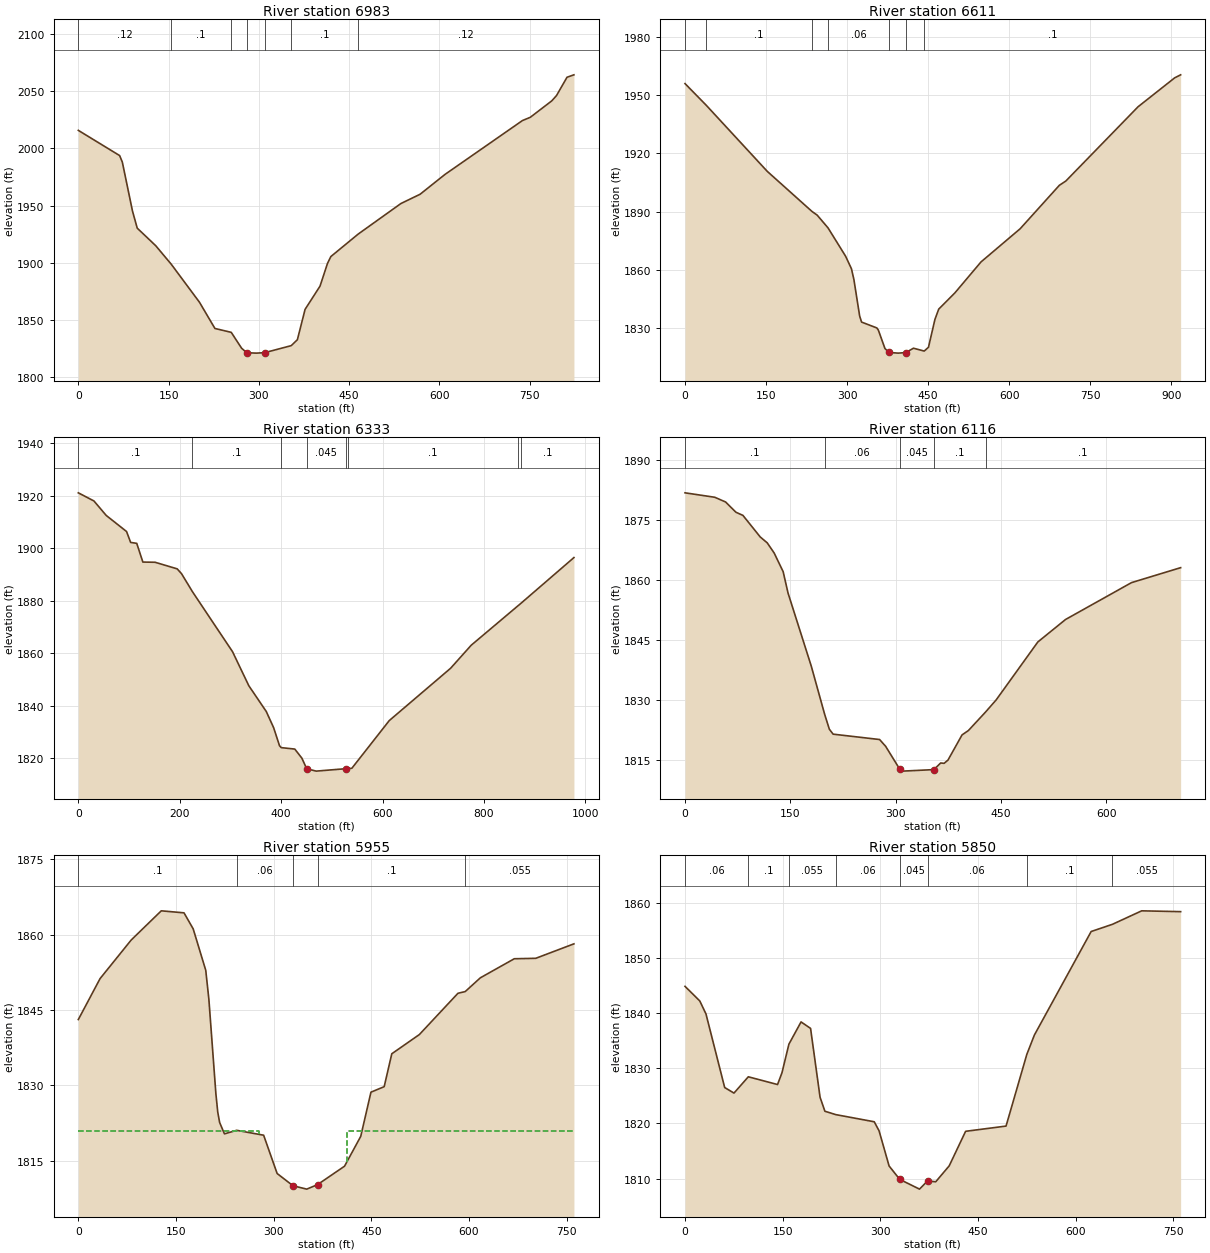
Type RM Length L Ch R = 1 ,6983    ,379.6,371.5,364.3
XS GIS Cut Line= 3
2439792.47838902585079.4542016582439949.00999571585490.349669221
2440301.20611077585642.967985745
#Sta/Elev= 30
       0 2015.75    68.6 1993.74    73.1 1988.07      90 1945.27    97.9 1930.33
   128.6    1915  154.371898.853   201.3 1865.61     227  1842.7  254.081839.314
   271.4 1825.38   279.9 1821.54   295.5 1821.16   309.5 1821.53   353.81827.709
     364 1832.89   376.8 1859.41   401.6 1879.67     414 1899.51   419.6 1905.52
  465.021925.146   536.1 1951.86   567.9 1959.94   609.1  1977.2   737.9  2024.3
     751 2027.16   786.7 2041.53   794.6 2046.18     812 2062.14   823.5 2064.26
#Mann= 7 ,-1 , 0
       0     .12       0  154.37      .1       0  254.08     .06       0
   279.9    .045       0   309.5     .06       0   353.8      .1       0
  465.02     .12       0
Bank Sta=279.9,309.5
XS Rating Curve= 0 ,0
Exp/Cntr(USF)=0,0
Exp/Cntr=0.3,0.1

Type RM Length L Ch R = 1 ,6611    ,285.9,278.2,268.7
XS GIS Cut Line= 4
2439487.24175598585239.8990985162439506.80820681585474.696508552
2439678.99297417585658.621146414 2440105.5416024585709.493918588
#Sta/Elev= 30
       0 1956.05   39.391944.831   152.2 1910.74  234.941890.045   244.6 1888.12
  264.551881.591   297.1 1866.95     308 1860.43   312.5 1854.91   323.2 1835.99
   326.7 1832.92     355 1829.89   357.8 1828.75     370 1819.25   377.6 1817.22
   394.6 1816.89   408.8 1817.18   422.7 1819.43  442.611817.952   450.5 1819.92
   462.5 1834.36   469.5 1839.62   499.3 1847.97   547.7 1863.97   620.2 1881.12
   692.7 1903.54   704.7 1905.75   838.3 1944.08   906.1 1959.02   917.1 1960.58
#Mann= 7 ,-1 , 0
       0      .1       0   39.39      .1       0  234.94      .1       0
  264.55     .06       0   377.6    .045       0   408.8     .06       0
  442.61      .1       0
Bank Sta=377.6,408.8
XS Rating Curve= 0 ,0
Exp/Cntr(USF)=0,0
Exp/Cntr=0.3,0.1

Type RM Length L Ch R = 1 ,6333    ,215.1,217,218.8
XS GIS Cut Line= 4
2439303.31711811 585376.864254372439338.53672962585740.800239927
2439561.59426915585877.7653957812439905.96380387585940.378038457
#Sta/Elev= 30
       0 1921.04    30.8 1917.94      55 1912.43    95.1 1906.31   103.2 1902.15
   115.2  1901.8   127.3 1894.67   151.4 1894.59     195 1892.08   203.6 1890.23
  225.141883.361   304.1 1860.54   336.2 1847.58   370.7 1837.74   385.2 1831.58
   396.8 1824.71  400.221823.989   426.9 1823.44   440.9 1819.97   450.3 1815.97
   469.1 1815.04   527.7 1815.97  531.351815.951   539.5 1816.14   613.2 1834.29
   734.2 1854.22   774.8 1862.99  866.321877.892  872.281878.853   977.4 1896.38
#Mann= 8 ,-1 , 0
       0      .1       0  225.14      .1       0  400.22     .06       0
   450.3    .045       0   527.7     .06       0  531.35      .1       0
  866.32     .12       0  872.28      .1       0
Bank Sta=450.3,527.7
XS Rating Curve= 0 ,0
Exp/Cntr(USF)=0,0
Exp/Cntr=0.3,0.1

Type RM Length L Ch R = 1 ,6116    ,147.7,160.9,181
XS GIS Cut Line= 2
2439067.99755777585795.0280714262439639.33792219586209.836829157
#Sta/Elev= 30
       0 1881.74    42.4 1880.63    57.8 1879.45    72.6 1876.88    82.5  1876.1
   107.2  1870.7   117.1 1869.24     127 1866.69   139.8 1862.03   146.7 1856.72
   179.9 1838.39  199.03  1826.3   205.6 1822.65     211 1821.41   277.2 1820.07
   285.8 1818.37   305.9 1812.65   309.8 1812.17   354.5 1812.55   364.2 1814.21
   369.1 1814.12   374.6 1814.93   394.6 1821.22   403.7 1822.32  428.421827.004
   443.3 1829.99   502.6 1844.46   542.1 1850.08     636 1859.29     706 1863.03
#Mann= 5 ,-1 , 0
       0      .1       0  199.03     .06       0   305.9    .045       0
   354.5      .1       0  428.42      .1       0
Bank Sta=305.9,354.5
XS Rating Curve= 0 ,0
Exp/Cntr(USF)=0,0
Exp/Cntr=0.5,0.3

Type RM Length L Ch R = 1 ,5955    ,95.2,104.9,97.9
XS GIS Cut Line= 4
 2438990.7725228  585883.1655174 2439203.3623242586021.811040052
2439251.88825713586202.0502195012439524.55778501586370.735605394
#Sta/Elev= 30
       0 1843.11    33.4 1851.26    81.2 1858.94   127.4 1864.75   162.3 1864.35
   176.4 1861.16   195.7 1852.91   200.5 1847.13   211.2 1828.43   214.1 1824.71
     217 1822.63   224.4 1820.36  243.221821.065   284.6 1820.09   305.3 1812.47
   329.7 1810.03   350.8 1809.36   367.4 1810.26   408.8 1813.92   433.7 1819.86
   449.4 1828.66   469.7 1829.75   481.4  1836.3   523.7 1840.12     583 1848.34
  594.15 1848.68   617.4 1851.42   669.5 1855.21   702.5  1855.3   761.1 1858.18
#Mann= 5 ,-1 , 0
       0      .1       0  243.22     .06       0   329.7    .045       0
   367.4      .1       0  594.15    .055       0
#XS Ineff= 2 , 0
           277.5    1821   412.5            1821
Permanent Ineff=
       F       F
Bank Sta=329.7,367.4
XS Rating Curve= 0 ,0
Exp/Cntr(USF)=0,0
Exp/Cntr=0.5,0.3

Type RM Length L Ch R = 1 ,5850    ,257.5,235.7,225.7
XS GIS Cut Line= 4
2438923.76052018585950.1775200152439136.35032158586088.823042668
2439184.87625451586269.0622221162439457.54578239 586437.74760801
#Sta/Elev= 30
       0 1844.86    22.7 1842.21    32.2 1839.85    60.9 1826.52    75.2 1825.51
    97.21828.464   142.1 1827.06   148.9  1829.2  159.541834.378   178.2 1838.41
   192.8 1837.24   207.4 1824.75   214.8 1822.22  231.531821.607   290.6 1820.31
     298 1818.67   313.4  1812.3   329.7 1809.87   360.1  1808.1   372.5 1809.59
     385 1809.43   405.7 1812.32   430.9 1818.58     493 1819.53  524.931832.537
   536.5 1836.03   623.7  1854.8  656.441856.107   701.3 1858.55   761.1  1858.4
#Mann= 8 ,-1 , 0
       0     .06       0    97.2      .1       0  159.54    .055       0
  231.53     .06       0   329.7    .045       0   372.5     .06       0
  524.93      .1       0  656.44    .055       0
Bank Sta=329.7,372.5
XS Rating Curve= 0 ,0
Exp/Cntr(USF)=0,0
Exp/Cntr=0.5,0.3

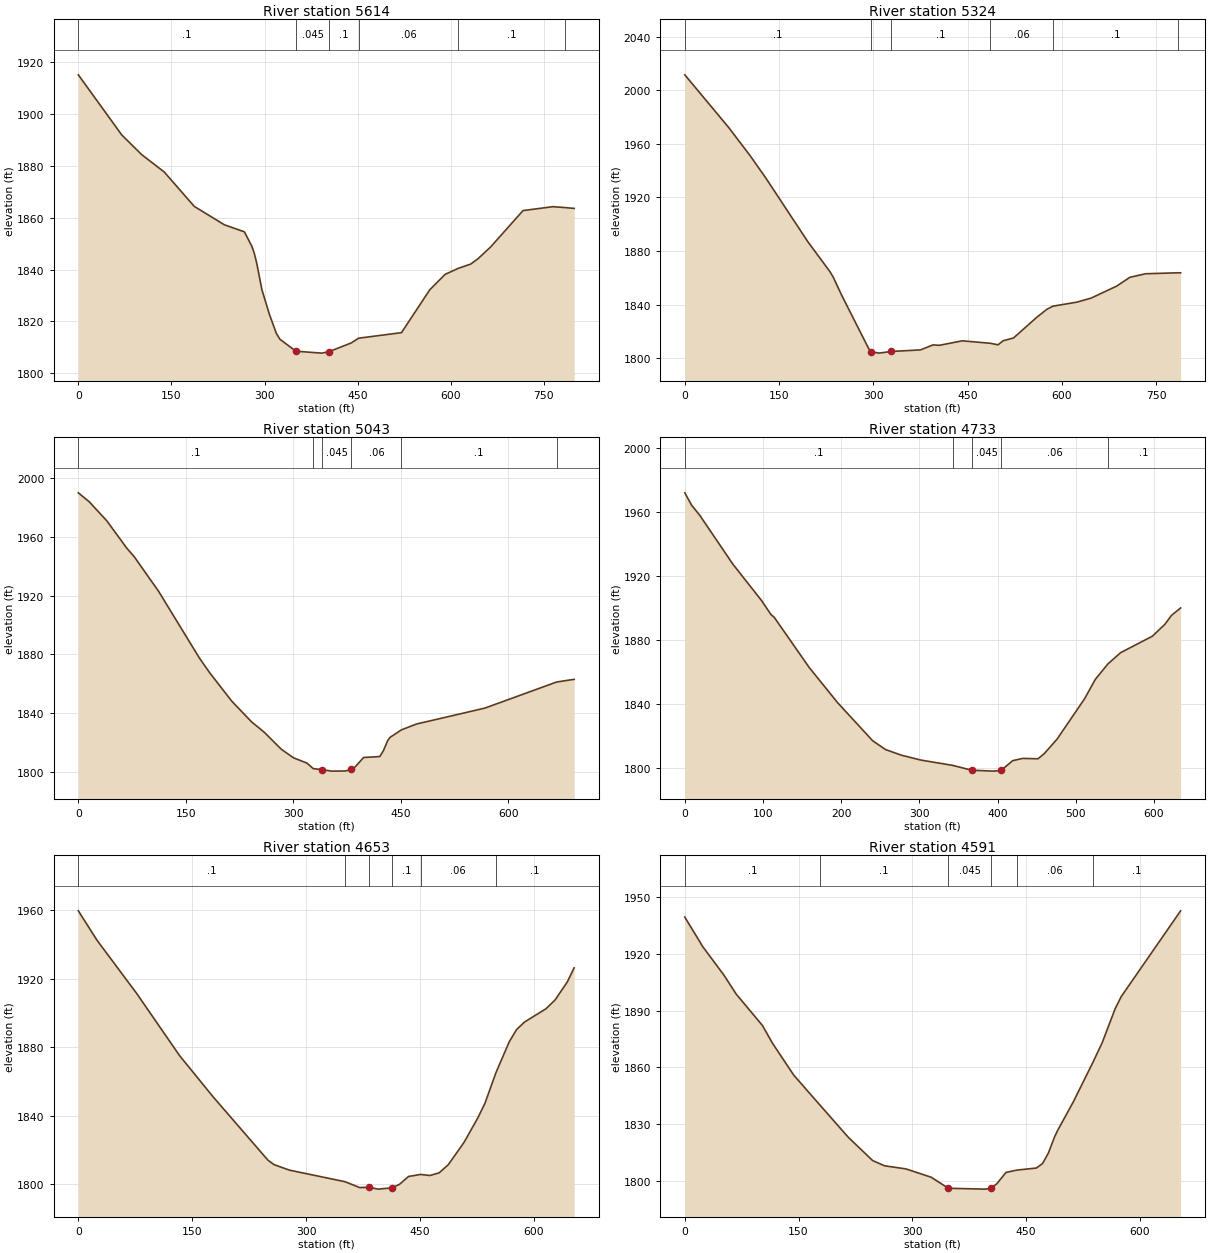
Type RM Length L Ch R = 1 ,5614    ,315.6,290.9,271.5
XS GIS Cut Line= 4
2438665.45082085586300.400733847 2438970.6874539586339.533635519
2439182.00512293586503.8918225452439405.06266246586515.631693047
#Sta/Elev= 30
       0  1915.2    69.9 1892.01   102.2 1884.37   138.4 1877.69   186.8  1864.4
   235.2 1857.31   267.5 1854.59   279.6 1848.97   283.6 1846.21   287.6 1842.27
   295.7 1832.29   307.7 1822.82   319.1 1815.32   324.8  1813.1   350.5 1808.49
   392.3 1807.75   404.1 1808.33   439.6 1811.68  451.731813.529   520.6 1815.65
   566.2 1832.21   590.9 1838.16   611.91840.462   632.2 1842.14   644.3 1844.28
   664.3 1848.76   716.4 1862.78   764.4 1864.29   783.71863.962   798.8 1863.62
#Mann= 6 ,-1 , 0
       0      .1       0   350.5    .045       0   404.1      .1       0
  451.73     .06       0   611.9      .1       0   783.7    .055       0
Bank Sta=350.5,404.1
XS Rating Curve= 0 ,0
Exp/Cntr(USF)=0,0
Exp/Cntr=0.3,0.1

Type RM Length L Ch R = 1 ,5324    ,292.6,280.2,271.7
XS GIS Cut Line= 2
2438630.23120934586719.1227817452439397.23608213586535.198143883
#Sta/Elev= 30
       0 2011.54    69.9 1972.16     104  1951.1   128.1 1935.01   195.9 1886.81
   230.9 1864.55   235.8  1860.7     250 1846.51   292.6 1807.03   296.7 1804.82
   308.7 1803.71   328.6 1804.96   374.9 1806.12     395 1809.87   404.9 1809.54
   441.4  1812.9  486.041811.069   498.2 1809.91   506.5 1812.98   522.9 1815.03
   559.9 1830.48   576.4 1836.58  585.641838.782   623.4 1841.76   646.3  1844.8
   686.9 1853.73     708 1860.33   732.7 1862.97  784.831863.713   788.7 1863.66
#Mann= 6 ,-1 , 0
       0      .1       0   296.7    .045       0   328.6      .1       0
  486.04     .06       0  585.64      .1       0  784.83    .055       0
Bank Sta=296.7,328.6
XS Rating Curve= 0 ,0
Exp/Cntr(USF)=0,0
Exp/Cntr=0.3,0.1

Type RM Length L Ch R = 1 ,5043    ,299.4,310,329.1
XS GIS Cut Line= 2
2438908.07481122 587055.665736132439393.32279196586562.591175054
#Sta/Elev= 30
       0 1990.13    15.2 1984.04    39.7 1971.06    67.7 1952.35      78 1946.58
   112.2 1922.82   168.7 1877.66   183.1 1867.57   214.2 1848.01   241.7 1833.97
   259.5 1826.85   283.2 1815.27   300.3 1809.43   318.9 1805.86  327.721802.107
   340.2 1801.31   353.9 1800.37   372.6 1800.47   381.1 1801.54   385.9 1803.07
     398 1809.66   420.7 1810.32   425.8 1814.47   431.5 1821.06   434.8 1823.34
  450.871828.536   471.8 1832.48   567.2 1843.34  667.381861.135   691.8 1862.96
#Mann= 6 ,-1 , 0
       0      .1       0  327.72     .06       0   340.2    .045       0
   381.1     .06       0  450.87      .1       0  667.38      .1       0
Bank Sta=340.2,381.1
XS Rating Curve= 0 ,0
Exp/Cntr(USF)=0,0
Exp/Cntr=0.3,0.1

Type RM Length L Ch R = 1 ,4733    ,79.2,80.7,82.1
XS GIS Cut Line= 2
2438942.24658987587133.285979983 2439566.1514418 587020.05880315
#Sta/Elev= 30
       0 1971.96     8.6 1964.33    19.3 1957.81    61.5 1927.38    98.1 1904.69
   110.3 1895.85   114.3 1894.23     159 1862.89   195.6 1840.74   240.3 1817.03
   256.7 1811.55   276.9 1808.03   301.8 1804.98  342.371801.669     3671798.627
   394.8 1798.06   404.6 1798.49   419.2 1804.57   432.1 1806.01   451.7 1805.77
   459.7 1808.98   476.1 1818.07   511.3  1843.3     525  1855.4  541.041865.011
   557.4 1872.09   598.1 1882.41   614.1 1889.87   622.4 1895.39   634.1 1900.02
#Mann= 5 ,-1 , 0
       0      .1       0  342.37     .06       0     367    .045       0
   404.6     .06       0  541.04      .1       0
Bank Sta=367,404.6
XS Rating Curve= 0 ,0
Exp/Cntr(USF)=0,0
Exp/Cntr=0.5,0.3

Type RM Length L Ch R = 1 ,4653    ,61.8,61.8,64.9
XS GIS Cut Line= 2
2438942.24658987587184.1226716222439591.56978762587117.110669007
#Sta/Elev= 30
       0 1959.63    24.6 1942.45    76.9 1911.32   133.2 1875.11   177.4    1851
   249.8  1813.9   257.8 1811.35   277.9 1808.16  351.031801.397   370.4 1797.98
   382.5 1798.12   394.8 1797.06     413 1797.79   422.7 1799.84   434.8 1804.46
  450.521805.634   462.9 1805.03     475 1806.56     487 1811.28   507.8 1824.36
     526 1838.71   535.3 1847.16     5501865.271   567.4 1883.18     577 1890.27
   587.6 1894.71   615.7 1902.42   627.8 1907.62   643.8 1918.12   652.8 1926.36
#Mann= 6 ,-1 , 0
       0      .1       0  351.03      .1       0   382.5    .045       0
     413      .1       0  450.52     .06       0     550      .1       0
#XS Ineff= 2 , 0
           342.5    1802   457.5            1802
Permanent Ineff=
       F       F
Bank Sta=382.5,413
XS Rating Curve= 0 ,0
Exp/Cntr(USF)=0,0
Exp/Cntr=0.5,0.3

Type RM Length L Ch R = 1 ,4591    ,127.2,131.5,139.4
XS GIS Cut Line= 2
2438963.04341827587211.8517761532439616.98813344587200.297982598
#Sta/Elev= 30
       0 1939.46    23.7  1923.8    51.7 1908.72    67.7 1898.79   102.4 1882.14
   115.7 1872.74   143.7 1855.89  178.121840.129   215.7 1823.01   247.7 1810.75
   263.5 1807.95   291.7 1806.31     325 1801.91   347.7 1796.07   395.7 1795.62
   403.7 1796.02   411.7 1798.52   423.7 1804.45  438.151805.689   463.7 1806.77
   471.9 1809.15   479.7 1814.81   487.7 1823.21   491.7 1826.58   512.3 1841.64
  538.491862.788   550.5    1873   567.7 1891.05   575.7 1897.44     654 1942.75
#Mann= 6 ,-1 , 0
       0      .1       0  178.12      .1       0   347.7    .045       0
   403.7      .1       0  438.15     .06       0  538.49      .1       0
Bank Sta=347.7,403.7
XS Rating Curve= 0 ,0
Exp/Cntr(USF)=0,0
Exp/Cntr=0.5,0.3

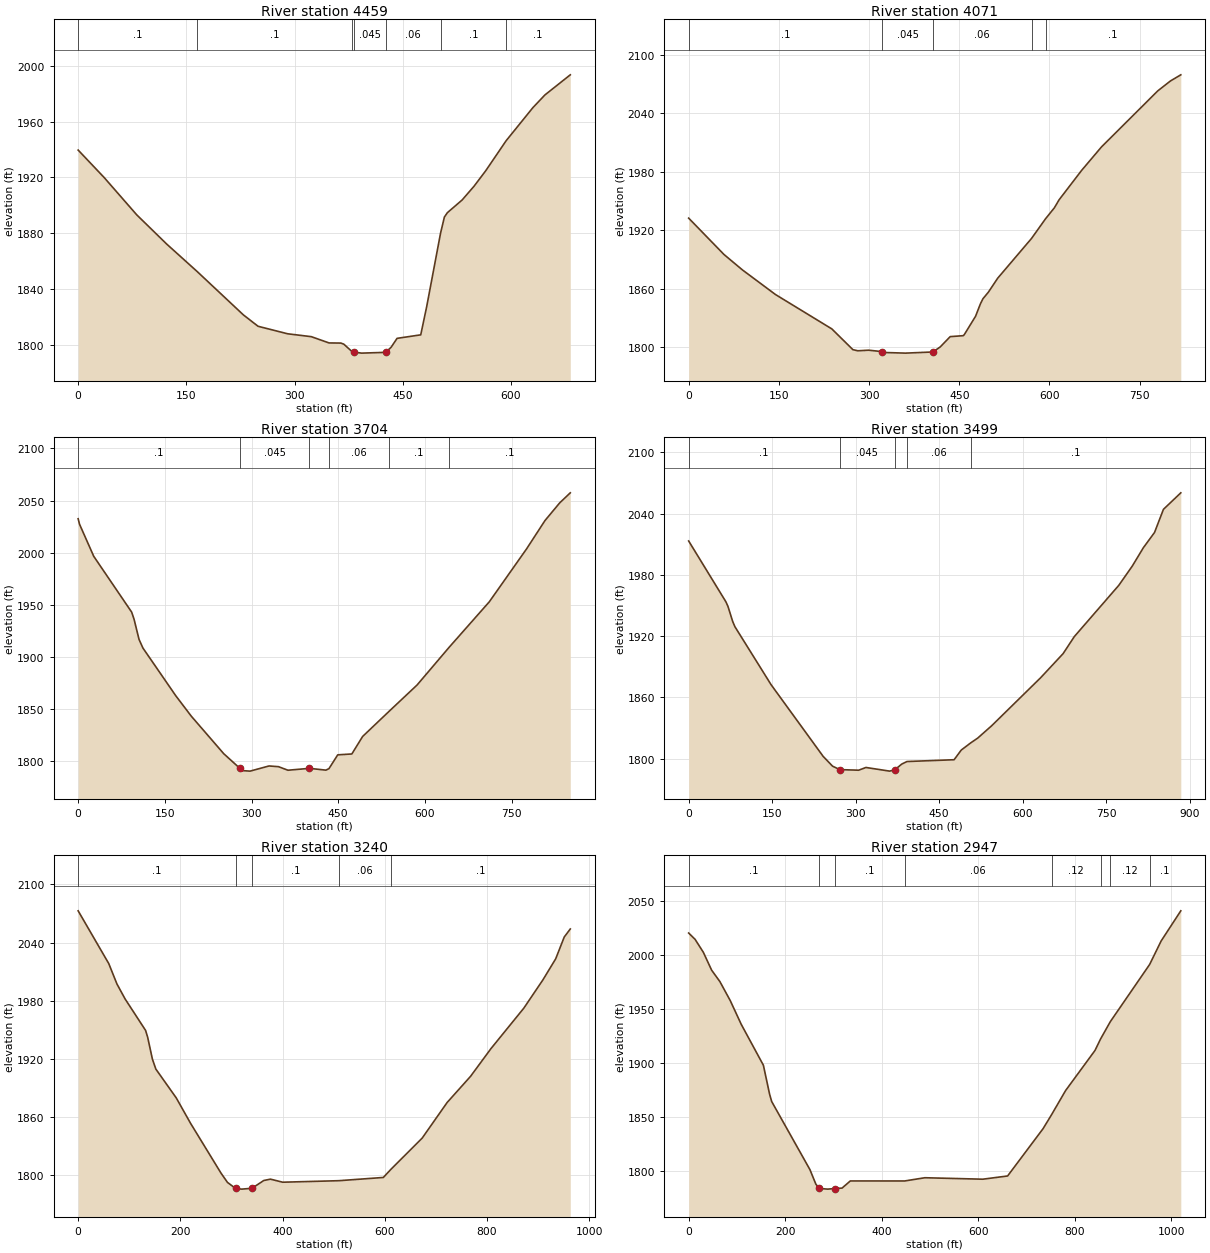
Type RM Length L Ch R = 1 ,4459    ,385.5,388.5,394.4
XS GIS Cut Line= 2
2438951.48962471587248.8239155272439616.98813344587399.023231733
#Sta/Elev= 30
       0 1939.58    36.1 1919.92    81.3 1893.22   122.7 1872.39  164.981852.724
     229 1821.74   249.4 1813.57   290.4  1808.2   323.2 1806.14   347.8 1801.66
   364.2 1801.56   368.3 1800.77   379.11795.735   382.9 1795.07   392.9 1794.37
   426.4 1794.92   433.9 1798.61   442.1 1804.94   474.9 1807.44   483.1 1827.49
  502.411880.246   507.7 1891.69   511.8 1894.79   532.3  1903.9   548.7 1913.67
   565.1 1924.87  593.231946.237   630.4 1969.94   647.1 1979.03   682.2 1993.39
#Mann= 7 ,-1 , 0
       0      .1       0  164.98      .1       0   379.1     .06       0
   382.9    .045       0   426.4     .06       0  502.41      .1       0
  593.23      .1       0
Bank Sta=382.9,426.4
XS Rating Curve= 0 ,0
Exp/Cntr(USF)=0,0
Exp/Cntr=0.3,0.1

Type RM Length L Ch R = 1 ,4071    ,385.4,366.5,359.7
XS GIS Cut Line= 3
2438861.11532921587544.8270070392439275.92408694587728.751644901
2439632.03349216587807.017448246
#Sta/Elev= 30
       0 1932.49    58.7 1895.24    89.3 1879.45   144.3  1854.2   238.1 1818.92
   273.1 1797.66   281.3  1796.5   299.3 1797.11   321.4 1795.66   325.6 1794.74
   360.6  1794.1   406.3 1795.28   418.4 1800.49   434.9 1811.01   456.6 1811.99
   458.3 1813.02   477.1  1831.9   485.1 1844.55   489.4 1849.87   498.5 1856.67
   513.9 1870.91  570.181911.684  593.531931.876   608.1 1943.04     616 1951.28
   653.5 1981.46   686.5 2005.49   780.1 2062.95   801.1 2073.08   818.4  2079.4
#Mann= 5 ,-1 , 0
       0      .1       0   321.4    .045       0   406.3     .06       0
  570.18      .1       0  593.53      .1       0
Bank Sta=321.4,406.3
XS Rating Curve= 0 ,0
Exp/Cntr(USF)=0,0
Exp/Cntr=0.3,0.1

Type RM Length L Ch R = 1 ,3704    ,192.2,205.5,208.3
XS GIS Cut Line= 3
2438712.41030286587955.7224746032439166.35196226588057.468018952
2439549.85439865588104.427500959
#Sta/Elev= 30
       0 2032.58     2.4 2027.33      27 1996.52    92.6 1942.97    96.7 1936.25
   105.4 1916.74   112.1 1908.49     169 1862.66   195.8 1843.09     252 1807.05
   279.5 1793.23   285.2 1790.81   297.5 1790.36   330.3 1795.31   346.7 1794.63
   363.1 1791.22   400.3 1793.03   428.7  1791.3  434.03 1792.76   449.2 1805.99
   473.6 1806.83   492.3 1823.64  538.491847.985   586.5 1873.02  641.91 1909.17
   711.4 1952.81   775.9 2003.59   807.9  2030.9   833.3 2047.81   851.6 2057.45
#Mann= 6 ,-1 , 0
       0      .1       0   279.5    .045       0   400.3      .1       0
  434.03     .06       0  538.49      .1       0  641.91      .1       0
Bank Sta=279.5,400.3
XS Rating Curve= 0 ,0
Exp/Cntr(USF)=0,0
Exp/Cntr=0.3,0.1

Type RM Length L Ch R = 1 ,3499    ,266.1,259.2,250.7
XS GIS Cut Line= 4
2438688.93056185588155.3002731332438931.55455222588198.346464973
 2439197.6582836588300.0920093222439549.85439865588319.658460159
#Sta/Elev= 30
       0  2013.3    66.9 1953.72    70.6  1949.2    79.1 1934.44    83.1 1929.32
   148.1  1872.5   241.5 1802.38   258.4 1792.77   271.3 1789.38   271.3 1789.37
   305.4 1788.78   318.4 1791.46     361 1787.88   370.4 1789.22   382.8 1794.81
  392.18 1797.28   476.8 1799.04   489.6 1808.51  507.021815.704   519.1 1820.18
   544.4  1832.4   632.5 1879.51   672.6 1902.97   692.6 1919.56   772.7 1969.92
   796.8 1988.69   816.8 2006.75   836.8 2021.63   852.8 2044.29     884 2060.47
#Mann= 5 ,-1 , 0
       0      .1       0   271.3    .045       0   370.4      .1       0
  392.18     .06       0  507.02      .1       0
Bank Sta=271.3,370.4
XS Rating Curve= 0 ,0
Exp/Cntr(USF)=0,0
Exp/Cntr=0.3,0.1

Type RM Length L Ch R = 1 ,3240    ,300.5,292.1,282.6
XS GIS Cut Line= 3
2438595.01159784588448.7970356792439178.09183276588480.103357017
2439542.02781832588374.444522501
#Sta/Elev= 30
       0 2072.77    59.9 2018.27    75.9 1997.22    91.9 1981.72     132 1949.18
     136  1942.2   145.3 1919.56     152 1909.32     192 1879.47   220.1 1853.12
   279.6 1801.75   292.2  1792.2   308.2 1785.93   320.2 1785.27   340.2 1786.16
   363.2 1794.18   376.3 1795.57   400.3 1792.42  510.031793.977   597.1 1797.32
  611.241805.329   673.1 1837.97     722 1874.79   767.8  1901.8   807.8  1930.5
     872 1972.23   909.4 2001.49   934.4 2023.25   951.1 2045.73   962.9 2054.02
#Mann= 5 ,-1 , 0
       0      .1       0   308.2    .045       0   340.2      .1       0
  510.03     .06       0  611.24      .1       0
Bank Sta=308.2,340.2
XS Rating Curve= 0 ,0
Exp/Cntr(USF)=0,0
Exp/Cntr=0.3,0.1

Type RM Length L Ch R = 1 ,2947    ,296.4,295.7,295.6
XS GIS Cut Line= 2
2438622.40462901588859.6925032422439573.33413966588491.843227519
#Sta/Elev= 30
       0 2020.32    13.3 2014.49    30.4 2002.51    47.6 1985.97    64.7 1975.42
    86.2  1957.8   108.9 1935.91   154.8  1898.1   167.7 1871.25     172 1864.51
   251.2  1801.6   263.5 1788.13   270.6  1784.2   287.7 1783.53   303.7  1784.1
   317.8 1784.49   334.9  1791.1  447.441791.069   489.3 1794.06   609.4 1792.71
   660.8  1795.7   734.2 1839.41  751.981852.453   780.9 1874.66   841.8 1911.73
  853.491922.465  873.641938.425     9551991.231   978.9 2013.01  1019.6 2040.85
#Mann= 8 ,-1 , 0
       0      .1       0   270.6    .045       0   303.7      .1       0
  447.44     .06       0  751.98     .12       0  853.49      .1       0
  873.64     .12       0     955      .1       0
Bank Sta=270.6,303.7
XS Rating Curve= 0 ,0
Exp/Cntr(USF)=0,0
Exp/Cntr=0.3,0.1