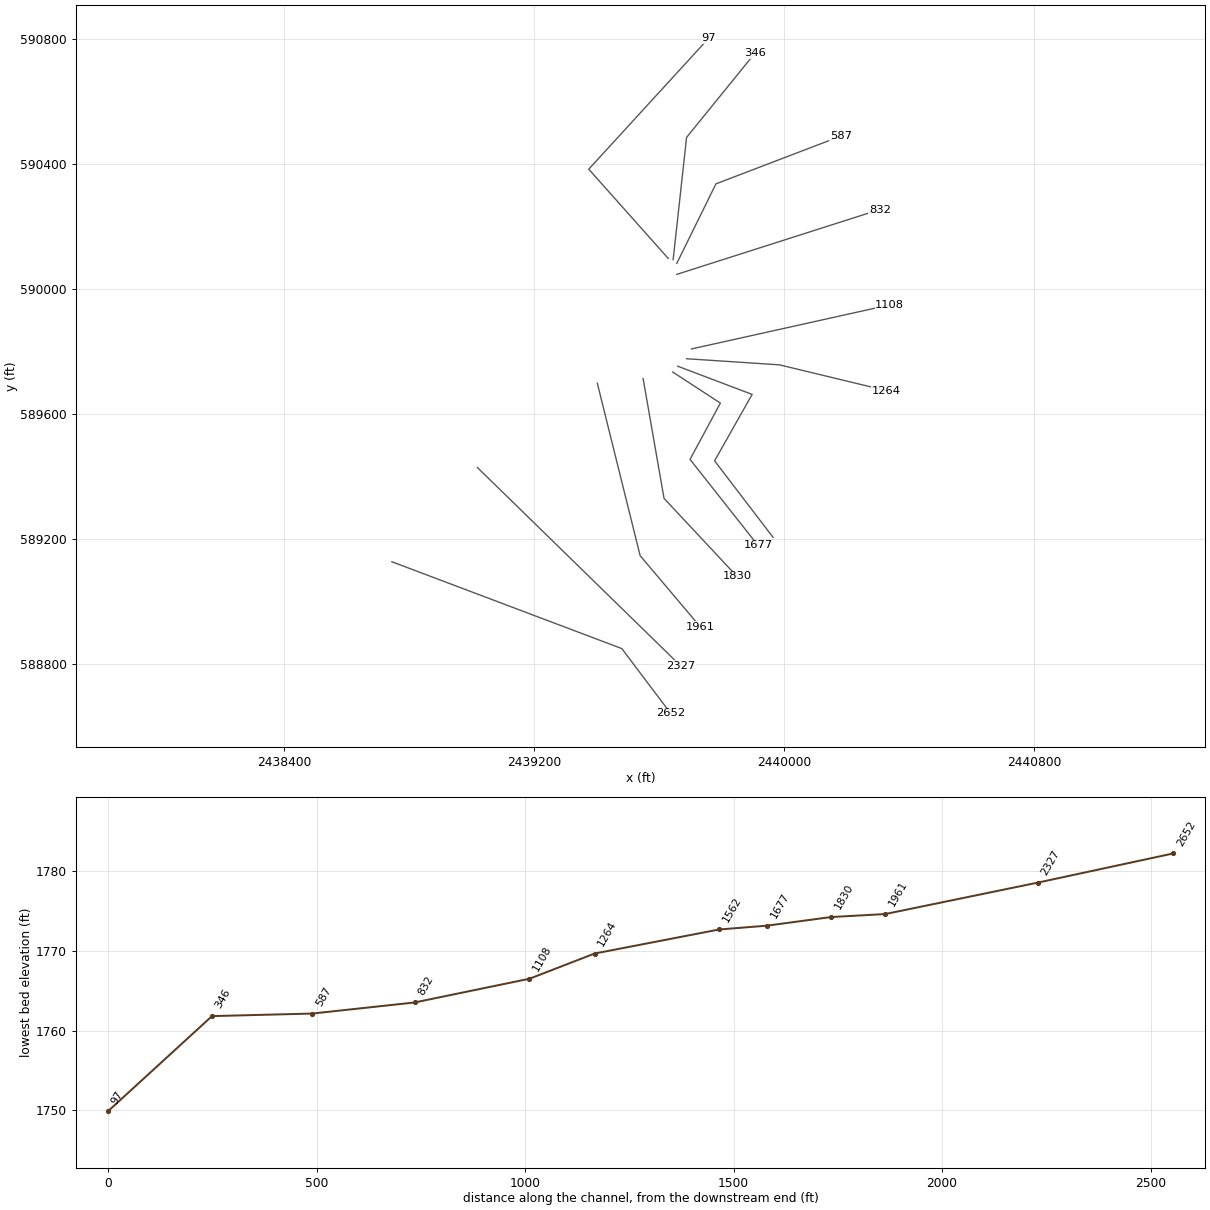
HEC-RAS study THORNCK.prj: THORNCK

--- THORNCK.g01 (geometry) --- (continued)

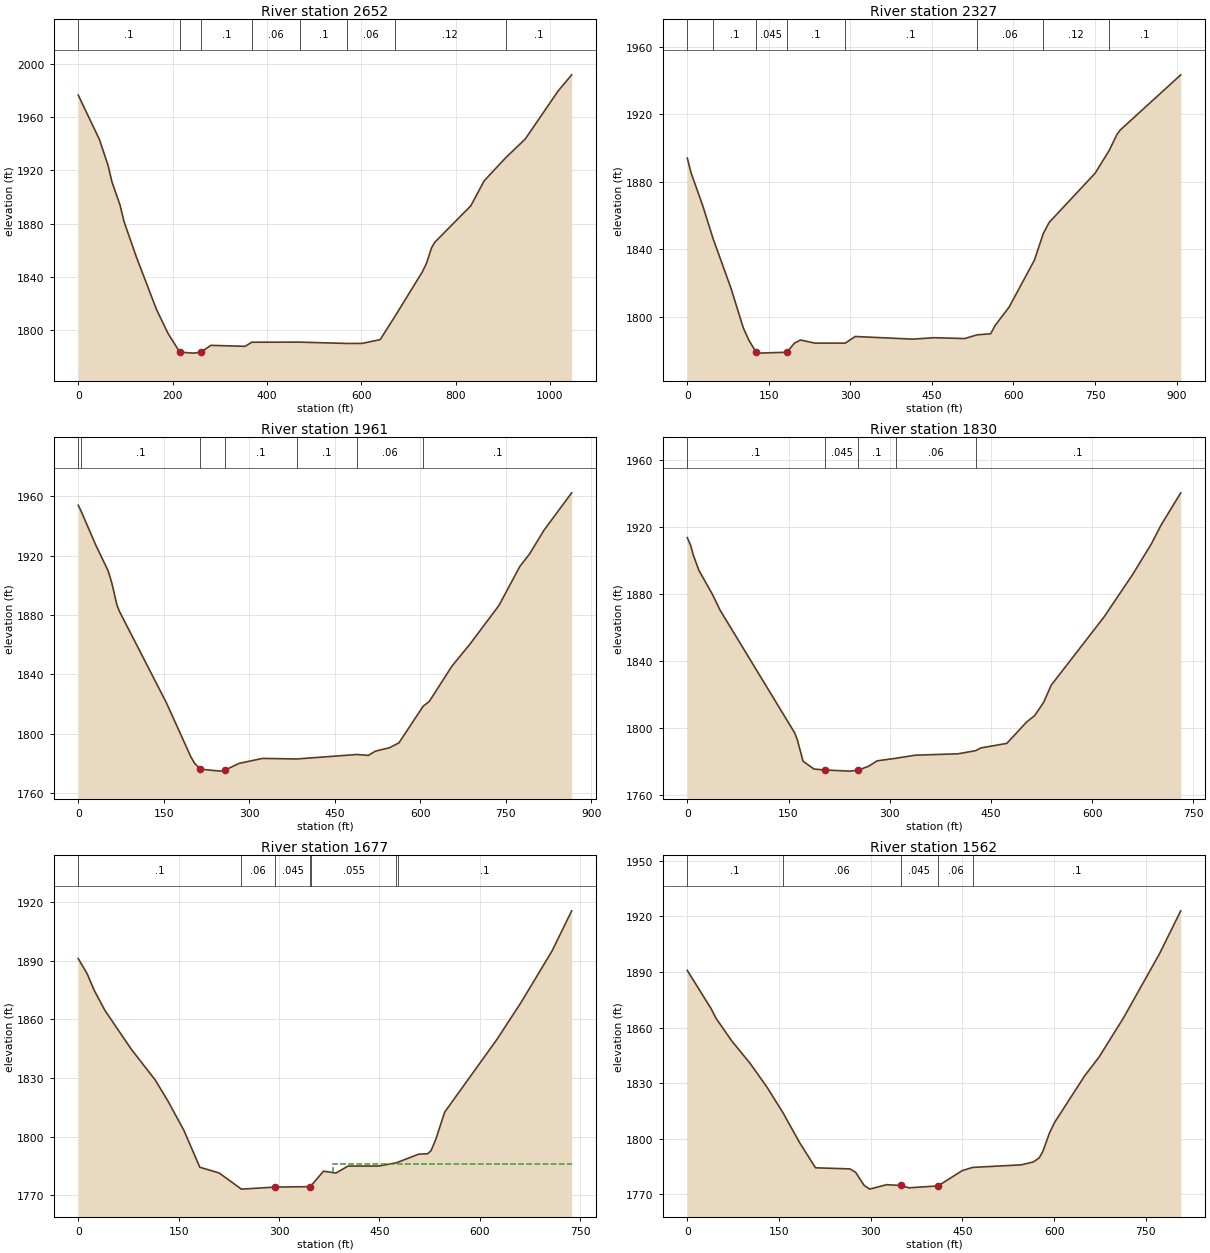
Type RM Length L Ch R = 1 ,2652    ,337.6,324.8,312
XS GIS Cut Line= 3
2438743.71662419589125.7962346172439479.41517564588847.952632741
2439635.94678233588640.548253875
#Sta/Elev= 30
       0 1976.89    44.8 1943.53    63.1 1924.07    71.7 1911.24    88.8 1893.76
    97.3 1881.31     123 1855.06   165.9 1815.23   190.6 1796.99   215.4    1783
   243.4 1782.23   259.8 1782.82   281.2  1788.1   353.8 1787.37  367.971790.459
  469.31 1790.52  570.661789.531   601.8 1789.55   640.3 1792.41     6721810.192
   730.1 1843.77   738.6 1850.14   749.2 1861.65   755.7 1865.74   832.5 1893.39
   860.7 1912.18  906.171929.537   947.7 1943.66  1017.7 1980.03  1046.3 1992.15
#Mann= 8 ,-1 , 0
       0      .1       0   215.4    .045       0   259.8      .1       0
  367.97     .06       0  469.31      .1       0  570.66     .06       0
     672     .12       0  906.17      .1       0
Bank Sta=215.4,259.8
XS Rating Curve= 0 ,0
Exp/Cntr(USF)=0,0
Exp/Cntr=0.3,0.1

Type RM Length L Ch R = 1 ,2327    ,383.8,366.2,348.5
XS GIS Cut Line= 2
 2439017.6469359589427.1195774972439667.25310367588793.166570399
#Sta/Elev= 30
       0 1894.08     7.1 1885.22    28.6 1865.74   47.421846.445    80.2 1817.17
   103.1 1793.49   113.3 1786.24     126 1779.43   131.7 1778.57   183.2  1779.1
   197.1 1784.48   208.3 1786.35   234.8  1784.5  290.571784.502   308.9 1788.42
   415.1 1786.86   454.2  1787.7   510.1  1787.2  533.331789.416     558 1790.02
   566.4 1795.02   591.9 1805.78   638.6 1833.68  654.71 1849.25   665.4 1855.87
   750.2 1885.12  776.091898.592   790.2 1907.96     796 1910.56   907.7 1943.38
#Mann= 8 ,-1 , 0
       0      .1       0   47.42      .1       0     126    .045       0
   183.2      .1       0  290.57      .1       0  533.33     .06       0
  654.71     .12       0  776.09      .1       0
Bank Sta=126,183.2
XS Rating Curve= 0 ,0
Exp/Cntr(USF)=0,0
Exp/Cntr=0.3,0.1

Type RM Length L Ch R = 1 ,1961    ,132.2,130.3,128.5
XS GIS Cut Line= 3
 2439401.1493723589697.1365990392439538.11452815589145.362685453
2439729.86574635588918.391855751
#Sta/Elev= 30
       0    1954    4.41 1950.68    30.9 1927.07    52.5  1909.8    59.1 1901.37
      68 1886.57    72.2 1882.52   154.6 1820.81   197.7  1784.2     204 1780.01
   214.4 1775.93   249.4 1774.62   258.3 1775.45   282.3 1779.85   323.5 1783.21
  383.061782.819  488.831785.842     509 1785.25   521.3  1788.1   546.1 1790.42
   562.5 1793.67   605.2 1818.48   615.9 1821.68   655.6  1845.5   687.2 1860.33
   737.9 1886.35   774.8 1912.82   791.9 1921.28   817.3 1937.36   865.6 1962.42
#Mann= 7 ,-1 , 0
       0      .1       0    4.41      .1       0   214.4    .045       0
   258.3      .1       0  383.06      .1       0  488.83     .06       0
   605.2      .1       0
Bank Sta=214.4,258.3
XS Rating Curve= 0 ,0
Exp/Cntr(USF)=0,0
Exp/Cntr=0.3,0.1

Type RM Length L Ch R = 1 ,1830    ,166.6,153.6,124.2
XS GIS Cut Line= 3
2439547.66537212589712.0927013182439614.67737473589328.506755313
2439848.06400453589078.944814539
#Sta/Elev= 30
       0 1913.73     5.1 1908.94     9.1  1903.1    17.2 1894.21    37.5 1879.66
    48.4 1870.53   159.4  1796.9   163.4 1792.52   171.5  1780.2   187.8 1775.48
   203.9 1774.91   240.6 1774.24   253.3 1774.78     269 1777.24   281.2 1780.38
  309.341781.933     338 1783.76   401.1 1784.59   427.2 1786.46   435.1 1788.11
   473.4 1790.81   502.5 1803.48   514.9  1807.5   528.2 1815.52   539.1 1825.52
   617.8 1866.52   659.6 1891.56   687.5 1909.93   701.6 1920.96   731.1 1940.48
#Mann= 5 ,-1 , 0
       0      .1       0   203.9    .045       0   253.3      .1       0
  309.34     .06       0   427.2      .1       0
Bank Sta=203.9,253.3
XS Rating Curve= 0 ,0
Exp/Cntr(USF)=0,0
Exp/Cntr=0.5,0.3

Type RM Length L Ch R = 1 ,1677    ,117,114.5,108.8
XS GIS Cut Line= 4
2439642.40647926589732.8895297162439794.91655418589633.526905148
2439697.86468832  589453.28772572439915.07600715589178.307439106
#Sta/Elev= 30
       0 1891.13    13.1 1883.53    24.2 1874.68    39.9  1864.6    79.5 1844.64
   114.9 1829.08   134.5 1817.97   157.9  1803.2   181.7 1784.34   210.6 1781.43
  243.761773.164   243.8 1773.16   293.8  1774.2   346.4 1774.44   347.21774.629
   366.5 1782.35     385 1781.39   403.1 1784.96   448.6 1784.96  475.321786.642
  477.691786.946   508.4 1791.03     522 1791.24   527.1 1792.86   534.1 1798.52
   547.5 1812.57   625.2 1849.59   661.8 1868.79   707.8 1894.97   737.2 1915.54
#Mann= 7 ,-1 , 0
       0      .1       0  243.76     .06       0   293.8    .045       0
   346.4     .06       0   347.2    .055       0  475.32     .06       0
  477.69      .1       0
#XS Ineff= 2 , 0
             170    1786     380            1786
Permanent Ineff=
       F       F
Bank Sta=293.8,346.4
XS Rating Curve= 0 ,0
Exp/Cntr(USF)=0,0
Exp/Cntr=0.5,0.3

Type RM Length L Ch R = 1 ,1562    ,262.5,298.7,380.7
XS GIS Cut Line= 4
2439658.58179024589751.3755994032439896.58993746589661.256009679
2439776.43048449589448.6662082792439963.60194007589203.725784926
#Sta/Elev= 30
       0 1890.86    38.6 1870.42    47.1 1864.96    72.8 1852.73   102.7 1840.66
   130.5 1827.73  156.731813.836     184 1797.65   209.7 1784.21   266.2  1783.6
   275.3 1781.77   289.1 1774.74   298.3 1772.68   325.9 1775.08   348.9 1774.66
   362.6 1773.39   410.1 1774.43   449.9 1782.73  466.881784.413   545.9 1785.79
   566.1 1787.37   575.6 1789.61   581.3 1792.91   592.7  1803.3   601.2 1808.99
   649.8 1833.85   673.6 1844.13   713.2  1865.1   772.5    1900     807 1923.05
#Mann= 5 ,-1 , 0
       0      .1       0  156.73     .06       0   348.9    .045       0
   410.1     .06       0  466.88      .1       0
Bank Sta=348.9,410.1
XS Rating Curve= 0 ,0
Exp/Cntr(USF)=0,0
Exp/Cntr=0.5,0.3

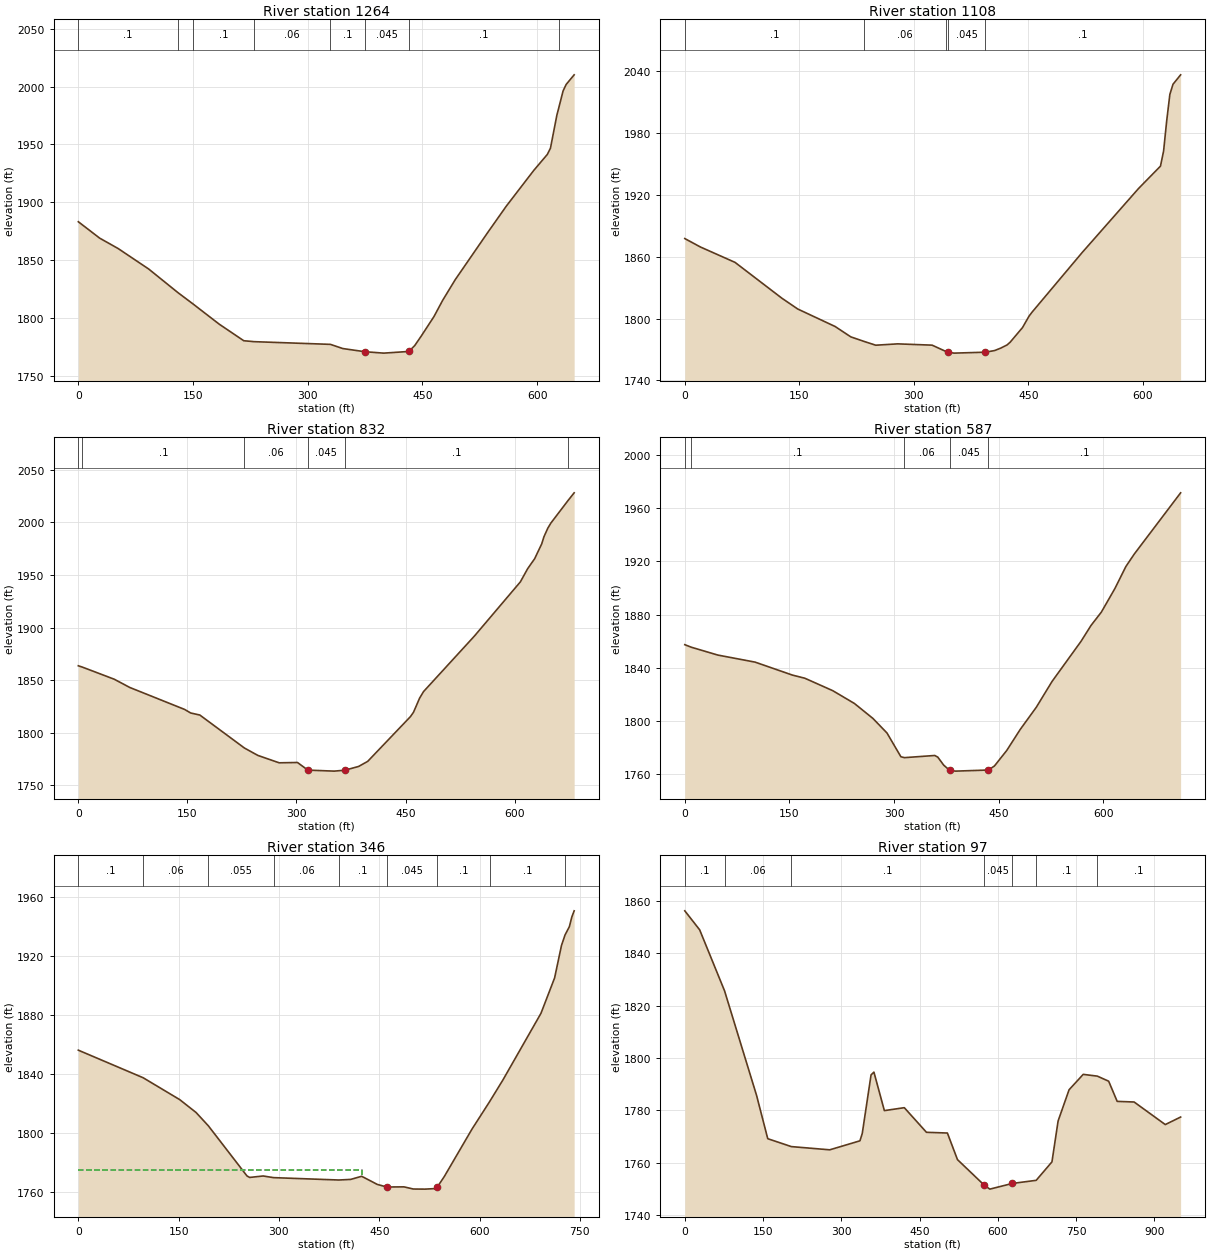
Type RM Length L Ch R = 1 ,1264    ,146.1,156,175.7
XS GIS Cut Line= 3
2439686.81955451589775.4024023842439984.22960722589755.835951548
2440324.68585177589673.656858035
#Sta/Elev= 30
       0 1883.22    27.9 1869.05      52 1860.09      92 1842.36  130.131822.013
   150.11812.101   184.2  1794.7   216.3 1780.37   229.91779.564  329.611777.234
   345.8 1773.62   374.61770.875   399.3 1769.66   432.2  1771.1   439.9 1776.23
   448.7 1784.75   465.1 1801.37   476.3 1815.21   492.9 1833.25     536 1874.59
   559.7 1896.81   595.6 1927.68   613.2 1941.39   617.3 1946.77   625.7 1975.35
  628.431982.298   633.8 1996.23   635.4 1998.51   637.9 2001.93   648.3 2010.21
#Mann= 8 ,-1 , 0
       0      .1       0  130.13     .06       0   150.1      .1       0
   229.9     .06       0  329.61      .1       0   374.6    .045       0
   432.2      .1       0  628.43     .12       0
Bank Sta=374.6,432.2
XS Rating Curve= 0 ,0
Exp/Cntr(USF)=0,0
Exp/Cntr=0.3,0.1

Type RM Length L Ch R = 1 ,1108    ,272.6,275.5,277.9
XS GIS Cut Line= 2
2439702.47271517589806.7087237222440336.42572227589947.587169744
#Sta/Elev= 30
       0 1877.71    20.7 1869.45    65.8  1854.6   127.2 1819.79     148  1809.3
   196.9 1792.35   217.4 1782.29  235.14 1777.78   250.1 1774.19   278.8 1775.49
   323.9 1774.24  342.061768.084   344.4 1767.67   352.5  1766.5   393.5  1767.4
   405.8 1768.99     414 1771.43   422.2 1774.49   426.3 1777.24   442.3 1791.29
   450.9 1802.43     455 1806.43   520.5  1864.2   594.3 1926.32     623 1948.01
   627.1  1962.7   631.2 1992.26   635.3 2017.62   639.4 2027.49   649.4 2036.67
#Mann= 5 ,-1 , 0
       0      .1       0  235.14     .06       0  342.06      .1       0
   344.4    .045       0   393.5      .1       0
Bank Sta=344.4,393.5
XS Rating Curve= 0 ,0
Exp/Cntr(USF)=0,0
Exp/Cntr=0.3,0.1

Type RM Length L Ch R = 1 ,832     ,243.6,245.4,247
XS GIS Cut Line= 2
2439655.51323317590045.4194239262440305.11940093590252.823802791
#Sta/Elev= 30
       0  1863.7    5.641862.413    49.5 1850.89    70.7 1843.09   146.1 1822.21
   154.5 1818.81   167.1 1816.86  228.411785.505   246.8 1778.49   276.2 1771.43
   301.4 1771.73   315.7 1764.48   351.8 1763.52   366.6  1764.4   385.4 1767.94
     398 1772.81   456.8 1815.39     461 1819.58   469.4    1833   474.8 1839.18
   544.6 1891.87   607.9 1943.47     618 1956.08   627.6 1965.54   637.3 1979.67
   640.3  1986.3   645.7 1994.58   649.9 1999.43  673.942021.247   681.9 2028.17
#Mann= 6 ,-1 , 0
       0      .1       0    5.64      .1       0  228.41     .06       0
   315.7    .045       0   366.6      .1       0  673.94      .1       0
Bank Sta=315.7,366.6
XS Rating Curve= 0 ,0
Exp/Cntr(USF)=0,0
Exp/Cntr=0.3,0.1

Type RM Length L Ch R = 1 ,587     ,218,240.3,256.6
XS GIS Cut Line= 3
2439655.51323317590080.6390354312439780.73851852590335.002896304
2440179.89411558590487.621212828
#Sta/Elev= 30
       0 1857.33    9.461855.404    47.3 1849.52   100.8  1844.2   154.3 1834.44
   172.1 1832.08   212.2 1822.69   243.2 1813.07   269.8 1801.77   289.9 1790.84
   309.8 1772.98  314.831772.277   358.4 1773.91   362.7 1772.69   371.2 1766.65
   379.8  1762.7   388.3 1762.13   435.4 1762.96     444 1766.03   461.6 1777.69
   480.9 1793.49     504 1810.24   526.6 1829.68   568.2 1859.93   582.4 1871.79
   597.2 1881.82   616.5 1899.46   632.4 1916.18   644.4 1925.54   710.9 1971.67
#Mann= 5 ,-1 , 0
       0      .1       0    9.46      .1       0  314.83     .06       0
   379.8    .045       0   435.4      .1       0
Bank Sta=379.8,435.4
XS Rating Curve= 0 ,0
Exp/Cntr(USF)=0,0
Exp/Cntr=0.3,0.1

Type RM Length L Ch R = 1 ,346     ,232.1,249.4,248.5
XS GIS Cut Line= 3
2439643.77336267590092.3789059332439686.81955451 590483.70792266
2439905.96380387590753.724944202
#Sta/Elev= 30
       0  1856.1   96.861837.408   151.6 1822.55   176.1 1813.79  194.481804.742
   252.2 1770.76   256.2 1769.74   276.3 1770.73  292.111769.606  389.731767.992
   407.3 1768.41   423.7 1770.53   447.1    1765   461.3 1763.25   486.9 1763.35
     501 1761.88   518.2 1761.81   531.9 1762.13     537 1763.36   547.3 1770.39
   588.5 1802.41  614.881821.076   634.8  1835.8   691.8  1881.1   712.2 1905.12
   722.5 1927.16  727.771934.256   734.3 1939.92   737.9 1946.38741.4442 1950.66
#Mann= 9 ,-1 , 0
       0      .1       0   96.86     .06       0  194.48    .055       0
  292.11     .06       0  389.73      .1       0   461.3    .045       0
     537      .1       0  614.88      .1       0  727.77     .12       0
#XS Ineff= 2 , 0
       0   423.7    1775               0
Permanent Ineff=
       F       F
Bank Sta=461.3,537
XS Rating Curve= 0 ,0
Exp/Cntr(USF)=0,0
Exp/Cntr=0.3,0.1

Type RM Length L Ch R = 1 ,97      ,,,
XS GIS Cut Line= 3
  2439628.120202  590096.29219612439373.75634112590381.962378311
2439757.25877752590800.684426209
#Sta/Elev= 30
       0 1856.21    28.5 1848.95   76.171825.657   137.6 1785.66     159 1769.14
  204.16 1766.12   277.8 1764.89   335.7 1768.33   340.1 1771.11     357 1793.53
   362.5 1794.57   382.5 1779.87   420.7 1780.99   463.2 1771.58   503.3 1771.31
   522.6 1761.15   573.6 1751.45   584.6 1749.87     628 1752.05  673.451753.226
   703.7 1760.28   715.5 1775.92   736.5 1787.83   763.6 1793.72  790.621793.048
   812.4 1791.11   828.7  1783.4   861.2 1783.16   920.9 1774.54950.3076 1777.41
#Mann= 7 ,-1 , 0
       0      .1       0   76.17     .06       0  204.16      .1       0
   573.6    .045       0     628      .1       0  673.45      .1       0
  790.62      .1       0
Bank Sta=573.6,628
XS Rating Curve= 0 ,0
Exp/Cntr(USF)=0,0
Exp/Cntr=0.3,0.1
LCMann Table=0

Chan Stop Cuts=-1
Use User Specified Reach Order=0
Composite Channel Slope=5